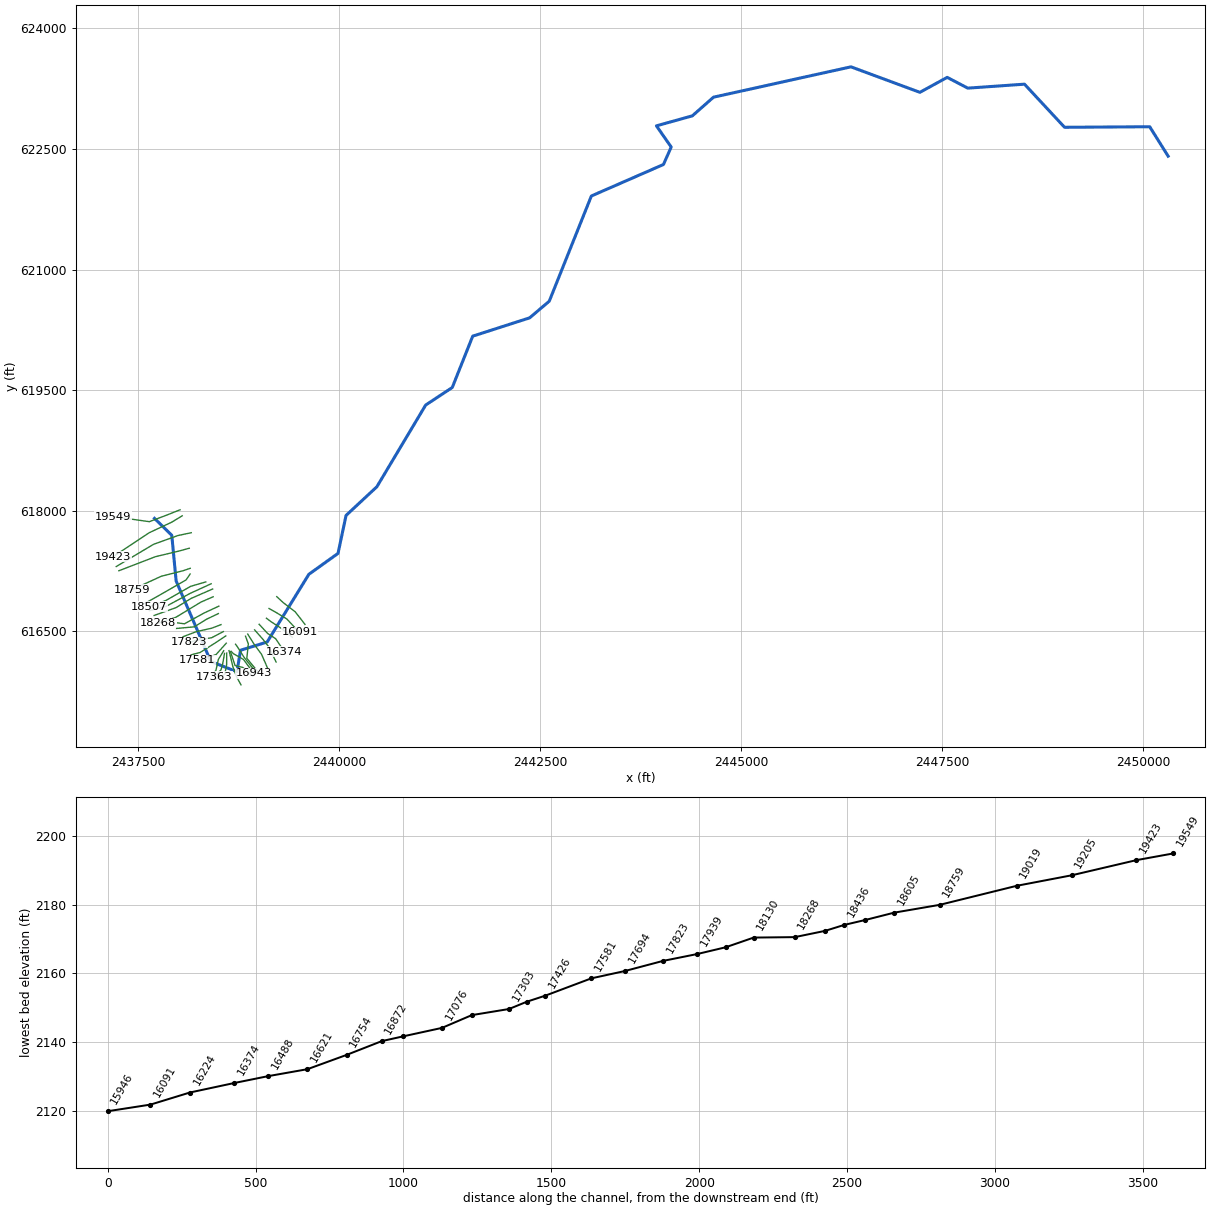
--- PETERSRN.prj (project) ---

Proj Title=PETERSRN
Current Plan=p01
Default Exp/Contr=0,0
English Units
Geom File=g01
Flow File=f01
Plan File=p01
Background Map Layer=QC
BEGIN DESCRIPTION:
Stream Name:Peters Run
Flood Zone: Zone A
Pendleton County, WV
WVDHSEM Flood Warning & Analysis Mapping
HEC-RAS Version: 5.0.7
Hydrology Method:
Regression
Model Notes:
Tie in with South Branch Potomac River at the downstream end.
END DESCRIPTION:
DSS Export Rating Curves= 0
DSS Export Rating Curve Sorted= 0
DSS Export Volume Flow Curves= 0
DXF OffsetX= 0
DXF OffsetY= 0
DXF ScaleX= 0
DXF ScaleY= 0

--- PETERSRN.p01 (plan) ---

Plan Title=Floodplain
Program Version=5.07
Short Identifier=Floodplain
Geom File=g01
Flow File=f01
Subcritical Flow
K Sum by GR= 0
Std Step Tol= 0.01
Critical Tol= 0.01
Num of Std Step Trials= 20
Max Error Tol= 0.3
Flow Tol Ratio= 0.001
Split Flow NTrial= 30
Split Flow Tol= 0.02
Split Flow Ratio= 0.02
Log Output Level= 0
Friction Slope Method= 1
Unsteady Friction Slope Method= 2
Unsteady Bridges Friction Slope Method= 1
Parabolic Critical Depth
Global Vel Dist= 0 , 0 , 0
Global Log Level= 0
CheckData=True
Encroach Param=-1 ,0,0, 0
Mapping Interval=1HOUR
Computation Time Step Use Courant=        0
Computation Time Step Use Time Series=    0
Computation Time Step Count To Double=0
Computation Time Step Max Doubling=0
Computation Time Step Max Halving=0
Computation Time Step Residence Courant=0
Run HTab= 0
Run UNet= 0
Run Sediment= 0
Run PostProcess= 0
Run WQNet= 0
Run RASMapper= 0
UNET Theta= 0
UNET Theta Warmup= 0
UNET ZTol= 0
UNET ZSATol= 0
UNET MxIter= 0
UNET Max Iter WO Improvement= 0
UNET MaxInSteps= 0
UNET DtIC= 0
UNET DtMin= 0
UNET MaxCRTS= 0
UNET WFStab= 0
UNET SFStab= 0
UNET WFX= 1
UNET SFX= 1
UNET 1D Methodology=Finite Difference
UNET DSS MLevel= 1
UNET Pardiso=0
UNET DZMax Abort= 0
UNET Use Existing IB Tables= 0
UNET Froude Reduction=False
UNET Froude Limit= 0
UNET Froude Power= 0
UNET D1 Cores= 0
UNET D2 Coriolis=0
UNET D2 Cores= 0
UNET D2 Theta= 1
UNET D2 Theta Warmup= 1
UNET D2 Z Tol= 0.01
UNET D2 Volume Tol= 0.01
UNET D2 Max Iterations= 20
UNET D2 Equation= 0
UNET D2 RampUpFraction=0.1
UNET D2 TimeSlices= 1
UNET D2 BCVolumeCheck=0
UNET D1D2 MaxIter= 0
UNET D1D2 ZTol=0.01
UNET D1D2 QTol=0.1
UNET D1D2 MinQTol=1
Write IC File= 0
Write IC File at Fixed DateTime=0
Write IC File at Sim End=0
Echo Input=False
Echo Parameters=False
Echo Output=False
Write Detailed= 0
HDF Write Warmup=0
HDF Write Time Slices=0
HDF Flush=0
HDF Face Node Velocities=0
HDF Compression= 1
HDF Chunk Size= 1
HDF Spatial Parts= 1
HDF Use Max Rows=0
HDF Fixed Rows= 1
Calibration Method= 0
Calibration Iterations= 20
Calibration Max Change=0.05
Calibration Tolerance=0.2
Calibration Maximum=1.5
Calibration Minimum=0.5
Calibration Optimization Method= 1
WQ AD Non Conservative
WQ ULTIMATE=-1
WQ Max Comp Step=1HOUR
WQ Output Interval=15MIN
WQ Output Selected Increments= 0
WQ Output face flow=0
WQ Output face velocity=0
WQ Output face area=0
WQ Output face dispersion=0
WQ Output cell volume=0
WQ Output cell surface area=0
WQ Output cell continuity=0
WQ Output cumulative cell continuity=0
WQ Output face conc=0
WQ Output face dconc_dx=0
WQ Output face courant=0
WQ Output face peclet=0
WQ Output face adv mass=0
WQ Output face disp mass=0
WQ Output cell mass=0
WQ Output cell source sink temp=0
WQ Output nsm pathways=0
WQ Output nsm derived pathways=0
WQ Output MaxMinRange=-1
WQ Daily Max Min Mean=-1
WQ Daily Range=0
WQ Daily Time=0
WQ Create Restart=0
WQ Fixed Restart=0
WQ System Summary=0
WQ Write To DSS=0
WQ Use Fixed Temperature=0
Sorting and Armoring Iterations= 10
XS Update Threshold= 0.02
Bed Roughness Predictor= 0
Hydraulics Update Threshold= 0.02
Energy Slope Method= 1
Volume Change Method= 1
Sediment Retention Method= 0
XS Weighting Method= 0
Number of US Weighted Cross Sections= 1
Number of DS Weighted Cross Sections= 1
Upstream XS Weight=0
Main XS Weight=1
Downstream XS Weight=0
Number of DS XS's Weighted with US Boundary= 1
Upstream Boundary Weight= 1
Weight of XSs Associated with US Boundary= 0
Number of US XS's Weighted with DS Boundary= 1
Downstream Boundary Weight= 0.5
Weight of XSs Associated with DS Boundary= 0.5
Percentile Method= 0
Sediment Output Level= 3
Mass or Volume Output= 0
Output Increment Type= 1
Profile and TS Output Increment= 1
XS Output Flag= 0
XS Output Increment= 10
Write Gradation File= 0
Read Gradation Hotstart= 0
Write HDF5 File= 1
Write Binary Output= 1
Write DSS Sediment File= 0
SV Curve= 0
Specific Gage Flag= 0

--- PETERSRN.f01 (steady flow) ---

Flow Title=Flows
Program Version=5.07
Number of Profiles= 6
Profile Names=P100yr,P10yr,P25yr,P50yr,P500yr,P101yr
River Rch & RM=PETERSRN,Main            ,19549
     533     249     352     440     780     648
River Rch & RM=PETERSRN,Main            ,18759
     646     301     426     533     947     786
River Rch & RM=PETERSRN,Main            ,17076
     829     386     546     683    1219    1009
River Rch & RM=PETERSRN,Main            ,15824
     926     430     610     763    1364    1127
River Rch & RM=PETERSRN,Main            ,11274
    1064     493     700     877    1570    1295
River Rch & RM=PETERSRN,Main            ,8027
    1184     548     778     975    1748    1440
Boundary for River Rch & Prof#=PETERSRN,Main            , 1
Up Type= 0
Dn Type= 3
Dn Slope=0.042956
Boundary for River Rch & Prof#=PETERSRN,Main            , 2
Up Type= 0
Dn Type= 3
Dn Slope=0.042956
Boundary for River Rch & Prof#=PETERSRN,Main            , 3
Up Type= 0
Dn Type= 3
Dn Slope=0.042956
Boundary for River Rch & Prof#=PETERSRN,Main            , 4
Up Type= 0
Dn Type= 3
Dn Slope=0.042956
Boundary for River Rch & Prof#=PETERSRN,Main            , 5
Up Type= 0
Dn Type= 3
Dn Slope=0.042956
Boundary for River Rch & Prof#=PETERSRN,Main            , 6
Up Type= 0
Dn Type= 3
Dn Slope=0.042956
DSS Import GetInterval= 0
DSS Import GetPeak= 0
DSS Import FillOption= 0

--- PETERSRN.g01 (geometry) ---

Geom Title=Geometry
Program Version=5.07

River Reach=PETERSRN        ,Main
Reach XY= 30
     2437701.474      617903.504     2437916.561      617693.082
      2437970.64      617124.908     2438401.117      616123.024
     2438727.606      615994.491     2438771.403      616262.297
      2439102.61      616364.588     2439621.673      617207.906
     2439984.098      617467.483     2440083.977      617940.141
     2440467.127      618296.795     2441074.235      619313.775
     2441404.709      619531.877     2441659.211      620170.959
     2442367.146      620398.818     2442611.402       620606.37
     2443134.803        621915.4     2444031.495      622307.169
     2444127.636       622524.75     2443943.985      622788.263
     2444390.575      622912.644     2444653.725      623144.809
     2446363.381        623522.7     2447220.484      623205.304
      2447560.41      623391.646     2447815.961      623257.521
     2448521.533      623306.878      2449020.12      622770.149
     2450078.946      622777.166     2450308.038      622410.978

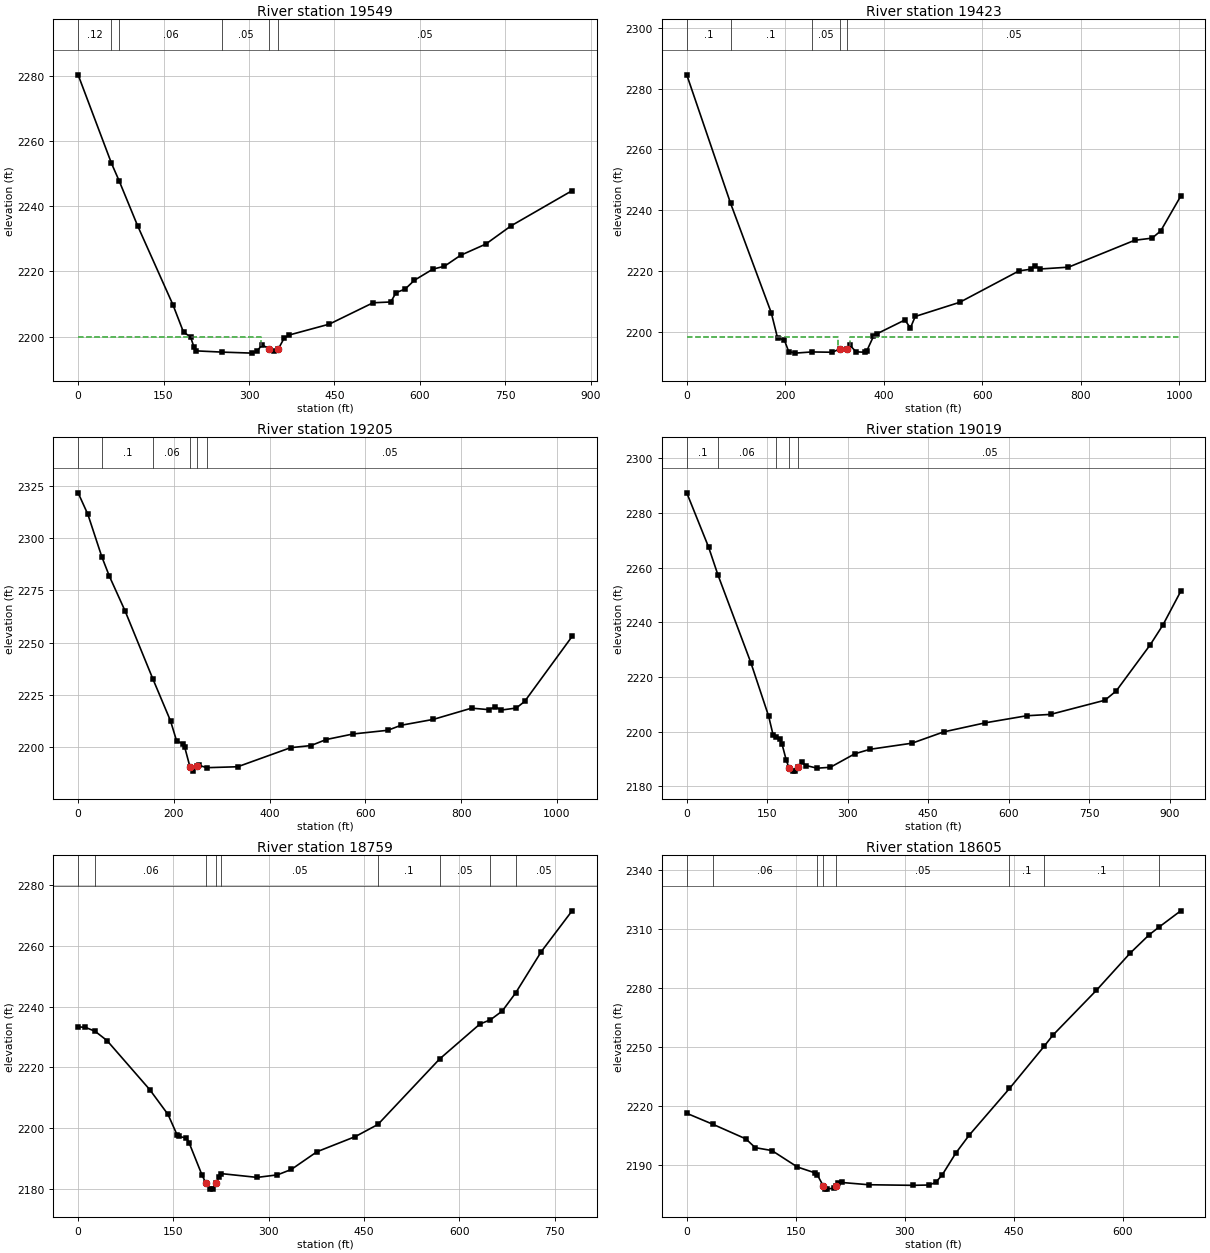
Type RM Length L Ch R = 1 ,19549   ,125.1,125.8,126.2
XS GIS Cut Line= 4
2438019.56382914618010.2913282082437867.95516293617949.647861725
2437637.86671656617862.2499247342437184.82434931617926.460653952
#Sta/Elev= 30
       0 2280.24   58.572253.113   72.17 2247.68   104.3 2234.03   166.4 2209.78
     185 2201.36   197.4 2199.91   203.1 2196.89   207.4 2195.63  252.642195.251
   305.9 2194.94   314.3 2195.62   322.9 2197.47   335.7 2196.22   344.3 2195.68
   351.3 2196.19   361.4 2199.45     370 2200.47   440.8 2203.82   517.6 2210.37
   548.8 2210.62     558 2213.46   574.2  2214.6   590.3 2217.28   622.6 2220.68
     643 2221.57   671.2 2224.91   715.6 2228.37     760 2233.96     867 2244.73
#Mann= 6 ,-1 , 0
       0     .12       0   58.57      .1       0   72.17     .06       0
  252.64     .05       0   335.7    .045       0   351.3     .05       0
#XS Ineff= 2 , 0
          320.39 2200.02
Permanent Ineff=
       F       F
Bank Sta=335.7,351.3
XS Rating Curve= 0 ,0
Exp/Cntr(USF)=0,0
Exp/Cntr=0.3,0.1

Type RM Length L Ch R = 1 ,19423   ,218,218,215.6
XS GIS Cut Line= 4
2438046.31829965617935.3788107872437914.32957848617855.115399265
 2437636.0830852617724.9103094622437184.82434931617425.260239779
#Sta/Elev= 30
       0 2284.57   89.14 2242.23   171.7 2206.24   184.4 2197.98   198.2 2197.29
     207  2193.5   220.3 2192.97  253.812193.359   295.7 2193.26   312.12194.443
   324.9 2194.47   331.8 2195.49   343.9  2193.4   361.6 2193.26     366 2193.83
   379.2 2198.47     386 2199.31   443.1 2203.88   454.3 2201.25   464.1 2205.04
   554.5  2209.7     675 2220.05   698.6 2220.57   706.5 2221.76   718.4 2220.67
   775.4 2221.26   909.8 2230.11   945.2 2230.82   962.7 2233.18  1003.4 2244.64
#Mann= 5 ,-1 , 0
       0      .1       0   89.14      .1       0  253.81     .05       0
   312.1    .045       0   324.9     .05       0
#XS Ineff= 2 , 0
          306.24 2198.21  330.64         2198.14
Permanent Ineff=
       F       F
Bank Sta=312.1,324.9
XS Rating Curve= 0 ,0
Exp/Cntr(USF)=0,0
Exp/Cntr=0.3,0.1

Type RM Length L Ch R = 1 ,19205   ,186.5,185.9,185.4
XS GIS Cut Line= 4
2438158.68707578617724.9103094622437991.02572726617689.237682119
2437689.59202621617580.4361687222437225.84787075617303.973306812
#Sta/Elev= 30
       0  2321.6    20.4 2311.29   49.59 2290.97    65.4 2281.69    98.1 2265.14
  156.13 2232.65     193 2212.61   205.7 2203.03   218.5 2201.68   222.7    2200
  233.762190.474   239.8 2188.57   248.3 2190.79   252.5 2191.35  268.732190.218
   333.3 2190.66   443.9 2199.78   486.4 2200.79   518.3 2203.68   574.4 2206.33
   646.8 2208.09   674.6 2210.49     742  2213.3   821.9 2218.67   858.4 2217.95
   871.5  2219.4   883.1 2217.74   915.2 2218.72   932.7 2221.87  1031.8 2252.93
#Mann= 6 ,-1 , 0
       0      .1       0   49.59      .1       0  156.13     .06       0
  233.76    .045       0   248.3     .06       0  268.73     .05       0
Bank Sta=233.76,248.3
XS Rating Curve= 0 ,0
Exp/Cntr(USF)=0,0
Exp/Cntr=0.3,0.1

Type RM Length L Ch R = 1 ,19019   ,259.6,260.3,259.5
XS GIS Cut Line= 4
2438134.04162451617531.8177249352438003.44278024617496.008364411
2437712.75503011617426.4960763352437258.81872464 617251.66213966
#Sta/Elev= 30
       0  2287.4    40.7 2267.52   58.052257.384   119.6 2225.15   152.6 2205.63
   160.8 2198.86  166.782198.111   173.2 2197.36   177.3  2195.6   185.5 2189.49
  190.322186.829   197.8 2185.51   201.9 2185.57  207.68 2186.93   214.3 2188.75
   222.5 2187.55   243.1 2186.59   267.7 2186.92   313.2 2191.86   341.8 2193.51
   419.9 2195.74   478.9 2199.87   556.2 2203.19   633.6 2205.78     678 2206.28
   779.4 2211.47   800.5 2214.87   863.8 2231.74   887.4 2238.97   920.7 2251.33
#Mann= 5 ,-1 , 0
       0      .1       0   58.05     .06       0  166.78     .05       0
  190.32    .045       0  207.68     .05       0
Bank Sta=190.32,207.68
XS Rating Curve= 0 ,0
Exp/Cntr(USF)=0,0
Exp/Cntr=0.3,0.1

Type RM Length L Ch R = 1 ,18759   ,151.5,153.7,156.1
XS GIS Cut Line= 4
2438145.62700585617282.2054177532438057.15682103 617251.66213966
2437786.48018413 617183.203068072437418.90763051 617014.68843031
#Sta/Elev= 30
       0 2233.37    11.5  2233.2   26.652231.921    45.4 2228.87   112.7 2212.71
   141.5 2204.53   155.5 2197.92     158 2197.34   170.3 2196.79   174.5 2195.29
   195.1 2184.52  201.142181.934   207.5 2180.14   211.5 2179.97  217.292181.931
   221.4 2183.98  225.51 2185.07   281.7 2183.83   313.6 2184.66   335.4 2186.44
   375.8 2192.27   436.2 2197.26  471.762201.259  568.782222.795   632.1 2234.28
  648.662235.686   667.3 2238.56  688.352244.509   728.8 2258.14   777.2 2271.55
#Mann= 9 ,-1 , 0
       0      .1       0   26.65     .06       0  201.14    .045       0
  217.29     .06       0  225.51     .05       0  471.76      .1       0
  568.78     .05       0  648.66      .1       0  688.35     .05       0
Bank Sta=201.14,217.29
XS Rating Curve= 0 ,0
Exp/Cntr(USF)=0,0
Exp/Cntr=0.3,0.1

Type RM Length L Ch R = 1 ,18605   ,97.5,97.6,97.5
XS GIS Cut Line= 4
2438144.72982144 617211.001337492438094.16387218617137.319525712
2437754.64964144616942.2794357132437581.28067255616845.481761417
#Sta/Elev= 30
       0 2216.21   36.072210.621    81.3 2203.22    94.2 2198.76   117.1  2197.3
   152.2 2188.94   176.3 2185.97  179.652184.899  187.872179.295   190.3 2177.94
   193.3  2177.7   202.1 2178.24  205.352179.295   208.6 2180.58   213.2 2181.08
   250.2 2179.93   311.1 2179.63   333.2 2179.79   342.4 2181.08   351.5 2184.98
   370.1    2196   388.5  2205.1  443.932228.821  491.752250.311   503.7 2255.92
   563.3 2278.61   609.7 2297.49   636.2 2306.94  650.152310.937   679.5 2319.07
#Mann= 8 ,-1 , 0
       0     .05       0   36.07     .06       0  179.65     .05       0
  187.87    .045       0  205.35     .05       0  443.93      .1       0
  491.75      .1       0  650.15      .1       0
Bank Sta=187.87,205.35
XS Rating Curve= 0 ,0
Exp/Cntr(USF)=0,0
Exp/Cntr=0.3,0.1

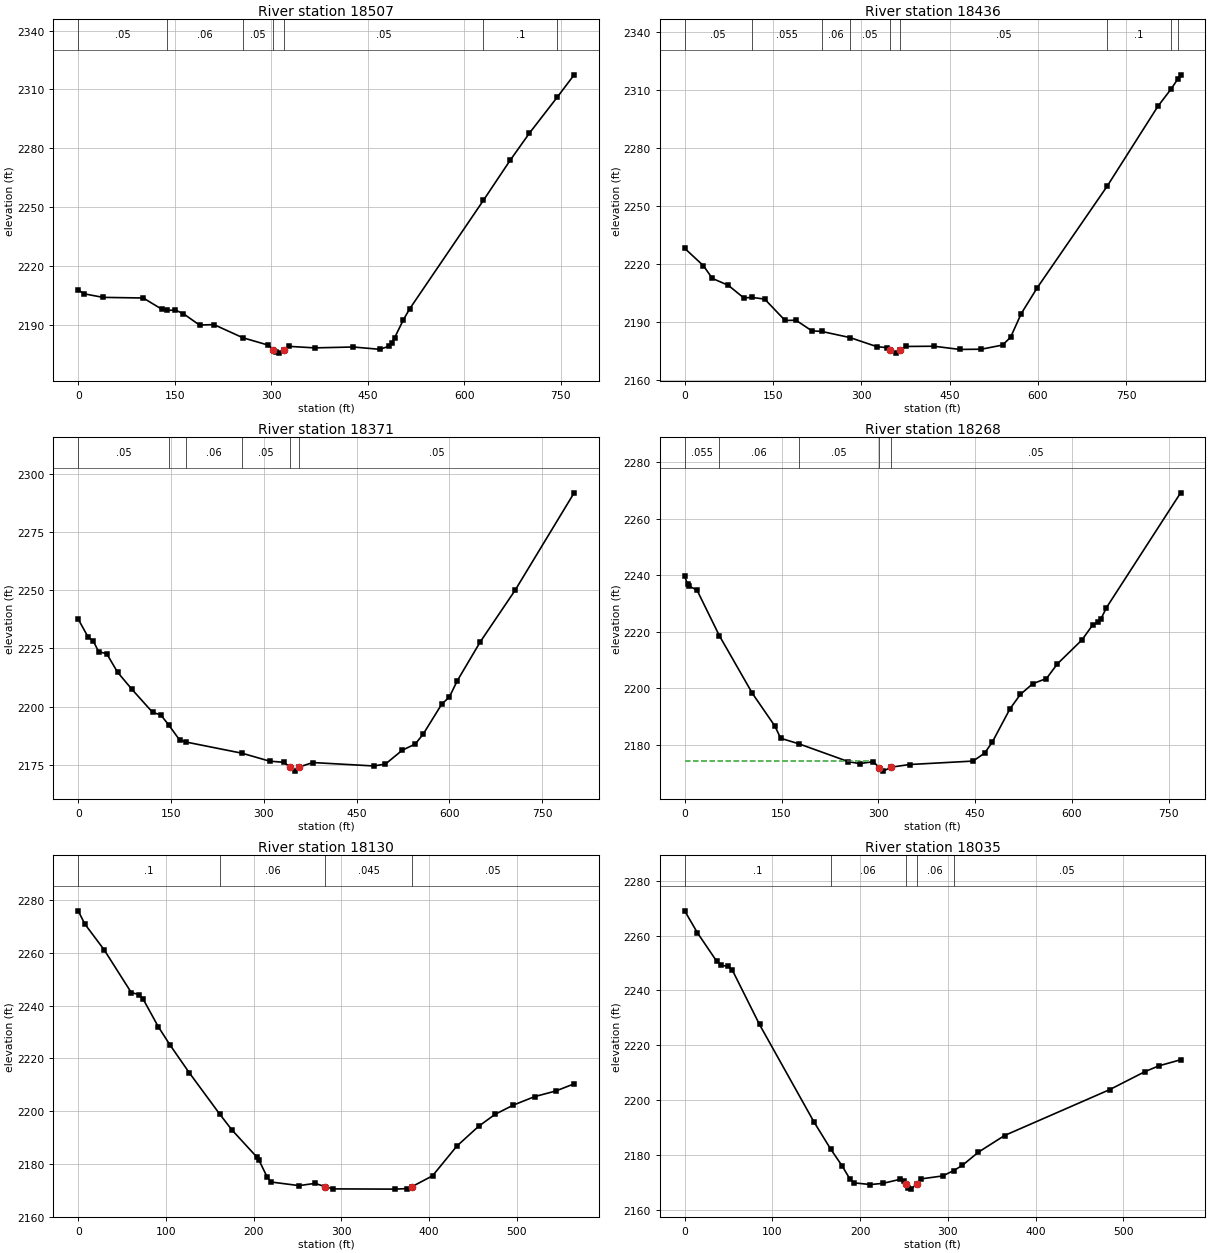
Type RM Length L Ch R = 1 ,18507   ,71.9,71.8,71.6
XS GIS Cut Line= 4
2438339.76991144617112.7589217872438151.95352848617057.858748305
2437845.66835011 616883.045038012437637.62558744616803.584260602
#Sta/Elev= 30
       0 2207.78     9.4  2205.8    38.6    2204   101.1 2203.68   130.3 2197.89
  137.74 2197.36   151.1 2197.52   163.6 2195.65   188.6 2189.87   210.9 2190.13
  256.132183.391   295.5 2179.64  303.382177.312   307.6  2175.9   312.2 2175.57
   320.32177.313   327.8 2179.02   367.5 2178.25   427.6 2178.69   468.5 2177.52
   482.6 2179.01   487.2 2180.75     492 2183.49   505.6 2192.62   515.4  2198.2
  629.98  2253.5   671.4 2273.84   701.3 2287.66  744.792306.104     771 2317.47
#Mann= 7 ,-1 , 0
       0     .05       0  137.74     .06       0  256.13     .05       0
  303.38    .045       0   320.3     .05       0  629.98      .1       0
  744.79      .1       0
Bank Sta=303.38,320.3
XS Rating Curve= 0 ,0
Exp/Cntr(USF)=0,0
Exp/Cntr=0.5,0.3

Type RM Length L Ch R = 1 ,18436   ,64.1,64.5,64.6
XS GIS Cut Line= 4
2438406.22801618617089.6430592682438144.72982144616969.729522454
2437847.11309151616809.3632262322437637.62558744616754.463052751
#Sta/Elev= 30
       0 2228.21    31.9 2219.21    46.9 2212.69    74.2 2209.09   100.6 2202.57
  113.542202.893   135.8 2202.02   170.6 2190.96   188.9 2191.11   215.9 2185.64
  233.122185.286   280.72182.153   326.3 2177.47   344.4 2176.91  348.37 2175.87
   358.1 2174.12  366.392175.869   376.3 2177.56   423.5 2177.68   467.1 2176.03
   503.8 2176.14   539.8 2178.28   553.5  2182.3   571.7 2194.56   598.9 2207.91
  717.452260.224   803.9 2301.59  826.08 2310.39  837.762315.693   842.3 2317.74
#Mann= 9 ,-1 , 0
       0     .05       0  113.54    .055       0  233.12     .06       0
   280.7     .05       0  348.37    .045       0  366.39     .05       0
  717.45      .1       0  826.08      .1       0  837.76      .1       0
#XS Ineff= 2 , 0
          327.98 2176.95  386.51         2176.87
Permanent Ineff=
       F       F
Bank Sta=348.37,366.39
XS Rating Curve= 0 ,0
Exp/Cntr(USF)=0,0
Exp/Cntr=0.5,0.3

Type RM Length L Ch R = 1 ,18371   ,102.7,102.7,103
XS GIS Cut Line= 4
2438425.00965447617024.6296959352438154.84301129616906.160900528
2437968.47136974616792.0263293432437696.85998514616695.228655047
#Sta/Elev= 30
       0 2237.58    15.6 2230.07    24.3 2228.22      33 2223.61    46.1 2222.74
    63.6 2214.82    86.6 2207.55   120.4 2197.56   133.5 2196.52  146.772192.022
   164.1  2185.7  173.842184.893  265.042180.059   309.6 2176.66   332.4 2176.18
  342.362174.164   349.8 2172.39  357.112174.165   379.5 2176.07     478  2174.6
   496.8 2175.43   523.9 2181.34   545.1 2184.04   557.8 2188.26   587.6 2201.03
   600.3 2204.27     613 2211.19   650.4 2227.96   706.5 2249.99   801.9 2291.75
#Mann= 6 ,-1 , 0
       0     .05       0  146.77    .055       0  173.84     .06       0
  265.04     .05       0  342.36    .045       0  357.11     .05       0
#XS Ineff= 2 , 0
                          384.15         2175.47
Permanent Ineff=
       F       F
Bank Sta=342.36,357.11
XS Rating Curve= 0 ,0
Exp/Cntr(USF)=0,0
Exp/Cntr=0.5,0.3

Type RM Length L Ch R = 1 ,18268   ,139.6,138.7,144.5
XS GIS Cut Line= 4
 2438430.7886201616927.8320216392438276.20128951616859.929175491
2437967.02662833616672.1127925292437741.64696877616596.986239344
#Sta/Elev= 30
       0 2239.68     4.4  2236.8     6.8 2236.11      19 2234.74   53.762218.541
   104.9  2198.1   139.9 2186.47   148.6 2182.22  177.172180.223   253.6 2173.93
     271 2173.23   292.2 2173.92   301.2 2171.85   307.5 2170.57   320.3 2171.99
   348.4 2172.91   446.7 2174.13   464.7 2176.96   476.4 2180.82   503.9 2192.65
     520 2197.75   539.3 2201.56   560.4 2203.38   577.3 2208.57   615.2 2217.01
   632.1 2222.39   640.5 2223.27   644.7 2224.45   653.2 2228.44   768.2 2269.17
#Mann= 5 ,-1 , 0
       0    .055       0   53.76     .06       0  177.17     .05       0
   301.2    .045       0   320.3     .05       0
#XS Ineff= 2 , 0
          287.75 2174.08
Permanent Ineff=
       F       F
Bank Sta=301.2,320.3
XS Rating Curve= 0 ,0
Exp/Cntr(USF)=0,0
Exp/Cntr=0.3,0.1

Type RM Length L Ch R = 1 ,18130   ,94.4,94.6,110.9
XS GIS Cut Line= 4
2438501.58094907616810.8079676392438320.98827314 616727.01296601
2438073.93749247616591.2072737142437990.14249085616602.765204974
#Sta/Elev= 30
       0 2275.89     7.5 2270.91    29.6 2261.11    60.5 2244.93    69.3 2244.14
    73.7 2242.65    91.3 2231.98   104.5 2225.16   126.6 2214.56  161.512198.801
   175.1 2192.95   203.8 2182.55   206.2 2181.39   215.3 2175.15   219.9 2173.14
   251.9 2171.77   270.1 2172.62   281.4 2171.39   290.7 2170.53   361.4 2170.44
   375.1 2170.65  380.722171.388   404.1 2175.49   431.8 2186.74   456.7 2194.26
   475.5  2198.8   496.3 2202.29   520.6  2205.5   544.8 2207.64   565.6 2210.34
#Mann= 4 ,-1 , 0
       0      .1       0  161.51     .06       0   281.4    .045       0
  380.72     .05       0
Bank Sta=281.4,380.72
XS Rating Curve= 0 ,0
Exp/Cntr(USF)=0,0
Exp/Cntr=0.3,0.1

Type RM Length L Ch R = 1 ,18035   ,98.8,96.2,92.3
XS GIS Cut Line= 4
2438495.80198344616718.3445175662438349.88310129 616648.99693001
 2438196.7405121616553.6439971222437974.25033536616533.417617418
#Sta/Elev= 30
       0 2268.99    14.5    2261    36.6 2250.57      41 2249.18    49.9 2248.73
    54.3 2247.41    85.3 2227.59   147.3 2192.14  166.62 2182.12   179.4 2176.13
   188.2 2171.39   193.5 2169.89   211.8 2169.29   226.1 2169.73   245.4 2171.18
   249.6 2170.67   251.82169.601   254.8 2168.11   258.3 2167.62  264.692169.643
   269.9 2171.36   294.2 2172.43  306.532174.356   316.4 2176.23   334.9 2181.09
   364.7 2187.15   484.5 2203.86   524.7 2210.41   540.8 2212.55   565.4 2214.73
#Mann= 5 ,-1 , 0
       0      .1       0  166.62     .06       0   251.8    .045       0
  264.69     .06       0  306.53     .05       0
Bank Sta=251.8,264.69
XS Rating Curve= 0 ,0
Exp/Cntr(USF)=0,0
Exp/Cntr=0.3,0.1

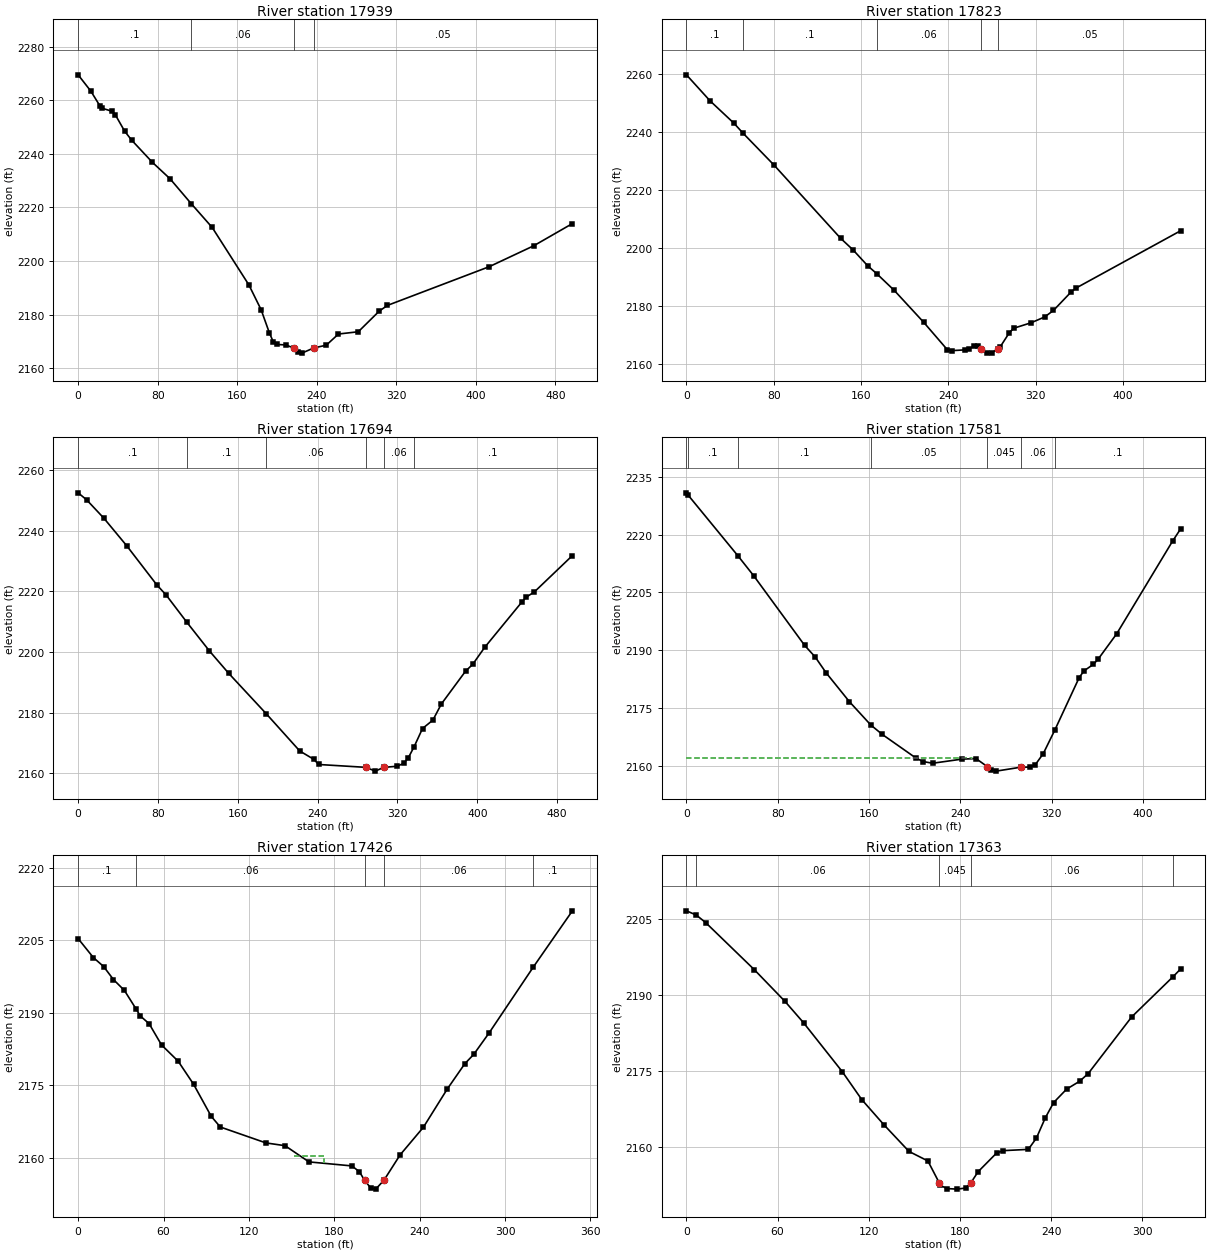
Type RM Length L Ch R = 1 ,17939   ,116.4,115.6,114
XS GIS Cut Line= 4
2438529.03103581616581.0940838622438412.00698181616536.307100233
2438224.19059884616494.4095994182438056.60059559616430.840977493
#Sta/Elev= 30
       0 2269.47    12.8 2263.38    22.1 2257.77    23.9 2257.03    34.5 2255.83
    37.5 2254.49    46.8 2248.44    53.8 2245.11    74.7 2236.82    92.4  2230.7
  113.66 2221.43   134.8 2212.53   171.7  2191.1     184 2181.84   192.2 2173.31
   196.3 2169.78   200.4 2168.87   208.6 2168.71  216.962167.557   220.9 2166.05
     225 2165.65  236.732167.555   249.5 2168.61   261.8 2172.78   281.7 2173.62
   302.8 2181.33     311 2183.45   413.4  2197.9   458.1 2205.69     497 2213.98
#Mann= 4 ,-1 , 0
       0      .1       0  113.66     .06       0  216.96    .045       0
  236.73     .05       0
Bank Sta=216.96,236.73
XS Rating Curve= 0 ,0
Exp/Cntr(USF)=0,0
Exp/Cntr=0.3,0.1

Type RM Length L Ch R = 1 ,17823   ,126.3,129.2,132.9
XS GIS Cut Line= 4
2438557.92586395616494.4095994182438412.00698181616417.838304826
2438240.08275433616390.3882180852438130.28240736 616360.04864853
#Sta/Elev= 30
       0 2259.77    21.7 2250.76    43.5 2243.06   51.72 2239.67    80.4 2228.53
   141.2 2203.33   152.7 2199.28   166.1  2193.8  174.162191.152   190.4 2185.31
   217.4 2174.28     239 2164.83     243 2164.51   255.2 2164.77   259.2 2165.12
   263.3  2166.1   267.3 2166.07   269.8 2165.19   275.4 2163.65   279.5 2163.69
  285.562165.217   287.6 2165.91   295.7 2170.63   299.7 2172.23   315.9 2174.16
   328.1 2176.13   336.2 2178.38   352.7 2184.89   356.9 2186.12   452.8 2205.93
#Mann= 5 ,-1 , 0
       0      .1       0   51.72      .1       0  174.16     .06       0
   269.8    .045       0  285.56     .05       0
Bank Sta=269.8,285.56
XS Rating Curve= 0 ,0
Exp/Cntr(USF)=0,0
Exp/Cntr=0.3,0.1

Type RM Length L Ch R = 1 ,17694   ,114.5,113.2,110.4
XS GIS Cut Line= 4
2438588.26543351616440.954167344 2438449.5702584616348.490717271
2438268.97758247616234.356146086 2438157.7324941616205.461317938
#Sta/Elev= 30
       0 2252.52     8.4 2250.25    25.9 2244.11    48.7 2235.05    78.7 2222.21
    88.4 2218.72  109.032209.781   131.6 2200.34   150.9 2192.96  188.372179.684
   222.1 2167.34   236.3 2164.57     241 2162.89   288.3 2161.95   297.8  2160.7
   306.2 2161.94   319.4  2162.3   326.2 2163.24   330.9 2165.12  336.672168.733
   345.1 2174.76   355.5 2177.53     364 2182.86   388.3  2193.7   395.4 2195.93
   407.4 2201.53   444.6 2216.47   448.8 2218.05   457.2 2219.83   495.3 2231.82
#Mann= 6 ,-1 , 0
       0      .1       0  109.03      .1       0  188.37     .06       0
   288.3    .045       0   306.2     .06       0  336.67      .1       0
Bank Sta=288.3,306.2
XS Rating Curve= 0 ,0
Exp/Cntr(USF)=0,0
Exp/Cntr=0.3,0.1

Type RM Length L Ch R = 1 ,17581   ,147.2,155.4,165.8
XS GIS Cut Line= 4
2438594.04439914616349.935458678 2438468.3518967 616209.79554216
2438320.98827314616153.450627271 2438235.7485301616136.113730382
#Sta/Elev= 30
       0 2230.89    1.532230.275   45.182214.493    58.9 2209.35   103.6 2191.23
   112.8 2188.23   122.3 2184.15   142.7 2176.64  161.552170.546   171.6  2168.1
     201 2161.98   207.1 2161.07   215.7 2160.62   241.4 2161.69   253.7 2161.83
   263.6 2159.73   267.1 2158.93   271.3 2158.57   292.7 2159.58   301.3 2159.63
   305.6 2160.23   312.6 2163.12   322.7 2169.23   344.1  2182.9   348.3 2184.63
   356.5 2186.32   360.6 2187.64   376.9 2194.25   425.9 2218.35     433 2221.55
#Mann= 7 ,-1 , 0
       0      .1       0    1.53      .1       0   45.18      .1       0
  161.55     .05       0   263.6    .045       0   292.7     .06       0
   322.7      .1       0
#XS Ineff= 2 , 0
          250.45 2161.89
Permanent Ineff=
       F       F
Bank Sta=263.6,292.7
XS Rating Curve= 0 ,0
Exp/Cntr(USF)=0,0
Exp/Cntr=0.5,0.3

Type RM Length L Ch R = 1 ,17426   ,63.1,63,62.9
XS GIS Cut Line= 4
2438562.26008818616256.0272671972438495.80198344616147.671661642
2438465.46241388616011.8659693462438413.45172321615949.742088827
#Sta/Elev= 30
       0 2205.33    10.7 2201.41    17.9 2199.56    24.8 2196.87    32.5 2194.62
   40.892190.702    43.6 2189.36    49.9 2187.73    58.6 2183.35    70.3 2179.98
    81.1 2175.23    93.5  2168.6    99.9 2166.38     132 2163.09   145.4 2162.52
   162.2 2159.17   192.3 2158.34   197.6 2157.16  201.272155.365   205.7 2153.74
   209.1 2153.54  214.852155.362   226.3 2160.64   242.6 2166.33   259.3  2174.2
   271.7 2179.46     278  2181.4   288.8 2185.84  319.75 2199.41   347.3 2211.07
#Mann= 5 ,-1 , 0
       0      .1       0   40.89     .06       0  201.27    .045       0
  214.85     .06       0  319.75      .1       0
#XS Ineff= 3 ,-1
  151.62  172.87 2160.46  174.87  189.28 2158.28  223.84   347.3 2158.38
Permanent Ineff=
       F       F       F
Bank Sta=201.27,214.85
XS Rating Curve= 0 ,0
Exp/Cntr(USF)=0,0
Exp/Cntr=0.5,0.3

Type RM Length L Ch R = 1 ,17363   ,58.6,59.7,59.1
XS GIS Cut Line= 4
2438572.37327803616222.7982148272438550.70215692 616098.55045379
2438529.03103581616017.6449349752438448.12551699615935.294674753
#Sta/Elev= 30
       0 2206.57    6.442205.745    12.6 2204.27    44.6    2195    64.9 2188.72
    77.1 2184.52   102.6 2174.88   115.4 2169.39   129.9 2164.46   146.5 2159.18
   158.9 2157.31  166.442152.966   167.2 2152.49   171.5 2151.87   178.1 2151.76
   183.7 2151.97   187.12152.968     192  2155.2   204.2 2158.89   208.6 2159.34
     225 2159.59   230.3 2161.79   236.2 2165.81   241.7 2168.82   250.2 2171.45
   258.8 2173.01   264.4 2174.51     293 2185.66  320.24 2193.59   325.3 2195.13
#Mann= 5 ,-1 , 0
       0      .1       0    6.44     .06       0  166.44    .045       0
   187.1     .06       0  320.24      .1       0
Bank Sta=166.44,187.1
XS Rating Curve= 0 ,0
Exp/Cntr(USF)=0,0
Exp/Cntr=0.5,0.3

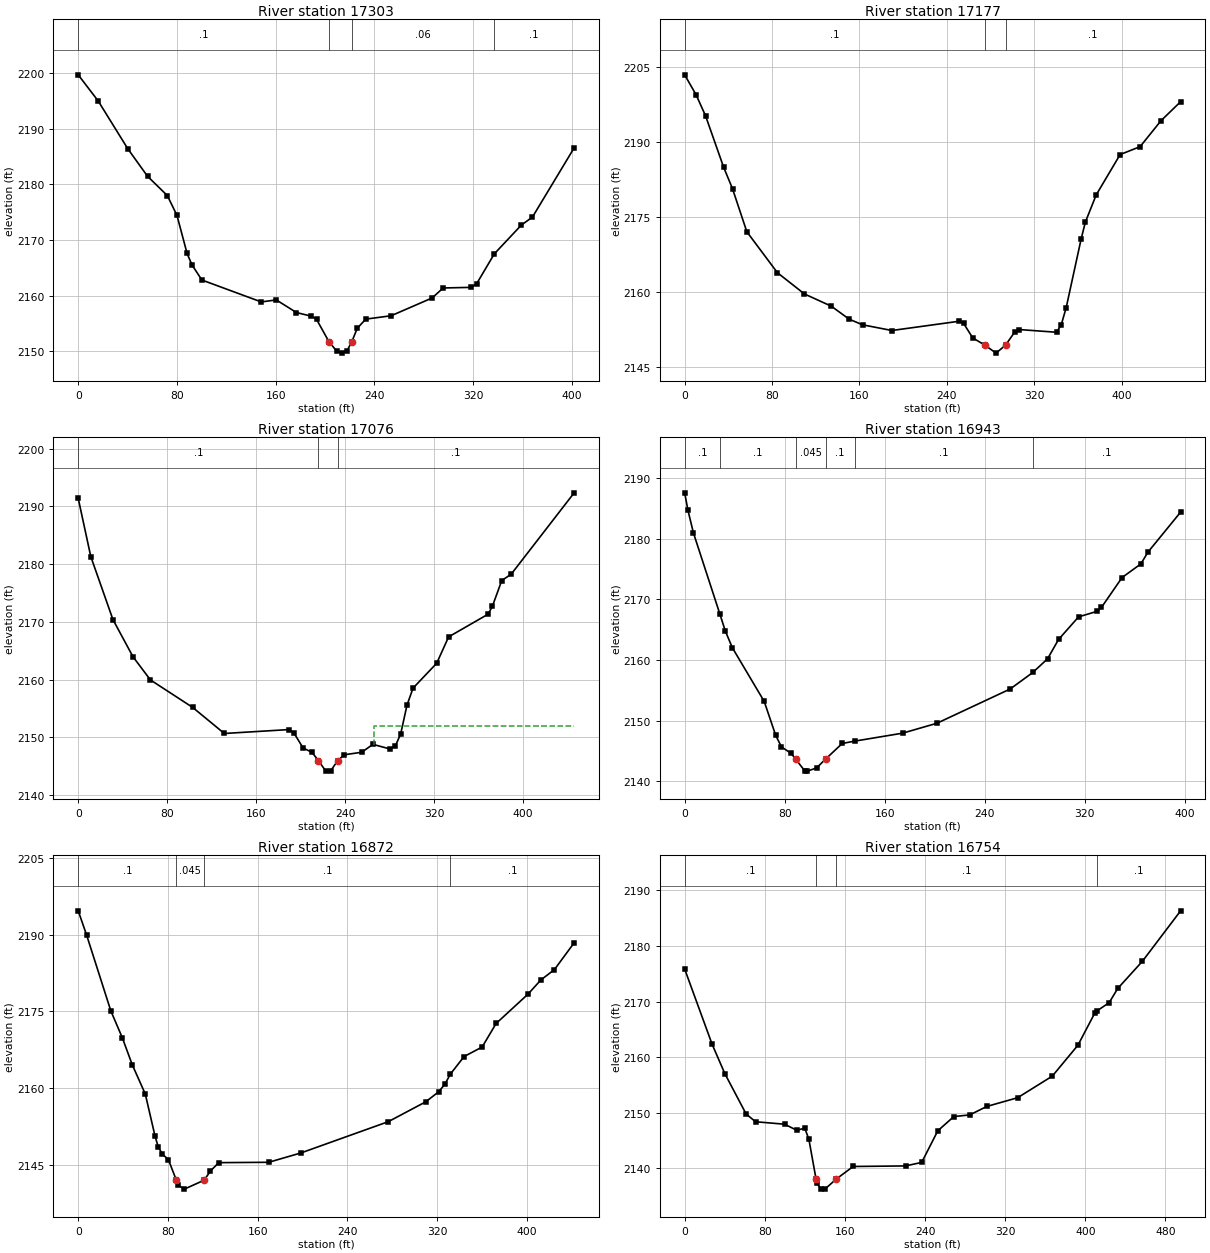
Type RM Length L Ch R = 1 ,17303   ,120.1,125.9,130.3
XS GIS Cut Line= 4
2438599.82336477616227.1324390492438598.37862336616081.213556901
2438575.26276084615961.3000200872438456.79396544615899.176139568
#Sta/Elev= 30
       0 2199.71    16.2    2195    40.2  2186.4    56.2 2181.45    72.2 2177.99
      80 2174.43    88.2 2167.58    92.2 2165.51   100.2  2162.8   148.3 2158.86
   160.5 2159.22   176.8 2156.95     189 2156.29   193.1 2155.72  203.092151.726
   209.4 2150.01   213.5 2149.65   217.5 2149.95   221.72151.726   226.1 2154.13
     233 2155.77   253.5 2156.37   286.7 2159.57   295.7 2161.37   318.3 2161.48
   322.8 2162.13  337.112167.506     359 2172.68     368 2174.12   401.8 2186.57
#Mann= 4 ,-1 , 0
       0      .1       0  203.09    .045       0   221.7     .06       0
  337.11      .1       0
Bank Sta=203.09,221.7
XS Rating Curve= 0 ,0
Exp/Cntr(USF)=0,0
Exp/Cntr=0.3,0.1

Type RM Length L Ch R = 1 ,17177   ,91.1,100.9,108.7
XS GIS Cut Line= 4
2438628.71819292616257.4720086042438676.39465936616058.097694383
2438724.07112581615928.0709677162438777.52655788 615831.27329342
#Sta/Elev= 30
       0 2203.47    10.5 2199.46    19.1 2195.29    35.6 2185.05    43.8 2180.71
    56.9 2172.12    84.9 2163.94   109.6  2159.7   134.3 2157.24   150.7 2154.64
   162.9 2153.53   189.7 2152.39     251 2154.23   255.3 2153.84   263.8  2150.9
  274.852149.474   285.1 2147.87  293.842149.474   302.1 2152.06   306.4 2152.58
   340.5 2152.04   344.8 2153.54   349.3 2156.93   363.1 2170.76   366.9 2174.06
   376.8 2179.48   398.7 2187.54     417 2189.12   436.2 2194.32   454.1  2198.1
#Mann= 3 ,-1 , 0
       0      .1       0  274.85    .045       0  293.84      .1       0
#XS Ineff= 2 , 0
          246.96 2153.82
Permanent Ineff=
       F       F
Bank Sta=274.85,293.84
XS Rating Curve= 0 ,0
Exp/Cntr(USF)=0,0
Exp/Cntr=0.3,0.1

Type RM Length L Ch R = 1 ,17076   ,134.6,132.7,125.3
XS GIS Cut Line= 4
2438646.05508981616244.469335938 2438703.8447461616071.100367049
 2438800.6424204616047.9845045312438923.44544003615939.628898976
#Sta/Elev= 30
       0 2191.39    11.3 2181.32    31.2 2170.41    49.2 2163.98    64.9 2159.95
   102.9 2155.19   131.4 2150.67   189.8 2151.35     194 2150.76   202.2 2148.17
   210.4 2147.38     2162145.961   222.7 2144.15   226.9 2144.16  233.34 2145.96
   239.2 2146.98     255 2147.42     265 2148.79   280.3 2147.99   285.1 2148.46
     290  2150.6   295.7 2155.59   301.1 2158.52   322.4 2162.84   333.1  2167.4
   368.6 2171.33   372.4 2172.67   380.9 2177.16   389.4 2178.26     446 2192.35
#Mann= 3 ,-1 , 0
       0      .1       0     216    .045       0  233.34      .1       0
#XS Ineff= 2 , 0
                          266.16         2151.97
Permanent Ineff=
       F       F
Bank Sta=216,233.34
XS Rating Curve= 0 ,0
Exp/Cntr(USF)=0,0
Exp/Cntr=0.3,0.1

Type RM Length L Ch R = 1 ,16943   ,77.2,71.1,65.6
XS GIS Cut Line= 4
2438654.72353825 616248.803560162438682.17362499616219.908732012
2438807.86612744616147.6716616422438933.55862988615977.192175568
#Sta/Elev= 30
       0 2187.54     2.6 2184.67       7 2180.93   28.162167.545    32.5 2164.76
    38.1 2162.01    63.6 2153.15    72.8 2147.55    77.4 2145.65      85 2144.61
   88.692143.661    95.9 2141.73    98.1 2141.66   105.5 2142.19  112.752143.661
     126 2146.22  136.062146.609   174.3 2147.92   201.7 2149.55   260.3  2155.2
  278.382157.921   290.2 2160.18     299 2163.37     315 2167.09   329.9 2168.01
   333.3 2168.65   349.8 2173.58   364.8 2175.82   370.5 2177.77   396.6 2184.36
#Mann= 6 ,-1 , 0
       0      .1       0   28.16      .1       0   88.69    .045       0
  112.75      .1       0  136.06      .1       0  278.38      .1       0
Bank Sta=88.69,112.75
XS Rating Curve= 0 ,0
Exp/Cntr(USF)=0,0
Exp/Cntr=0.3,0.1

Type RM Length L Ch R = 1 ,16872   ,122.3,118.5,109.1
XS GIS Cut Line= 4
2438709.62371173616336.9327860112438732.73957425616305.148475048
2438815.08983447616175.1217483822438969.67716506615980.081658383
#Sta/Elev= 30
       0 2194.63     7.5 2189.89    29.1 2175.08    39.3 2169.85    48.2 2164.56
    59.8 2158.86    68.5 2150.62    71.4  2148.5    75.1 2147.11    80.4 2146.05
   87.452142.049    89.3 2141.03    94.6 2140.29  112.392142.048   117.8 2143.82
   125.3 2145.46   169.8 2145.53   198.6 2147.36   276.4 2153.46   309.9 2157.35
   321.5 2159.33     327 2160.83  331.822162.768     344 2166.18   360.1 2168.04
   372.5 2172.63     401 2178.37   412.4 2181.13   424.5 2183.15   442.1 2188.39
#Mann= 4 ,-1 , 0
       0      .1       0   87.45    .045       0  112.39      .1       0
  331.82      .1       0
Bank Sta=87.45,112.39
XS Rating Curve= 0 ,0
Exp/Cntr(USF)=0,0
Exp/Cntr=0.3,0.1

Type RM Length L Ch R = 1 ,16754   ,124.6,132.5,140.5
XS GIS Cut Line= 4
2438833.87147277616436.6199431222438868.54526655616341.267010233
2438849.76362825616162.1190757162438985.56932055615997.418555272
#Sta/Elev= 30
       0 2175.84    27.4 2162.32    40.1 2157.05    61.3 2149.81    70.7  2148.4
    99.7 2147.96   111.9 2146.87   119.9 2147.25     124 2145.24  131.152138.096
     132 2137.37     136 2136.32     140 2136.29  151.312138.099   168.2 2140.36
   220.5 2140.46   236.6 2141.09   252.7 2146.78   268.7 2149.33   284.6 2149.63
   301.6 2151.15   332.4 2152.72     367  2156.6   392.6 2162.16   409.6    2168
  411.862168.354   423.8 2169.81   432.3 2172.35   456.9 2177.23   495.1 2186.31
#Mann= 4 ,-1 , 0
       0      .1       0  131.15    .045       0  151.31      .1       0
  411.86      .1       0
Bank Sta=131.15,151.31
XS Rating Curve= 0 ,0
Exp/Cntr(USF)=0,0
Exp/Cntr=0.3,0.1

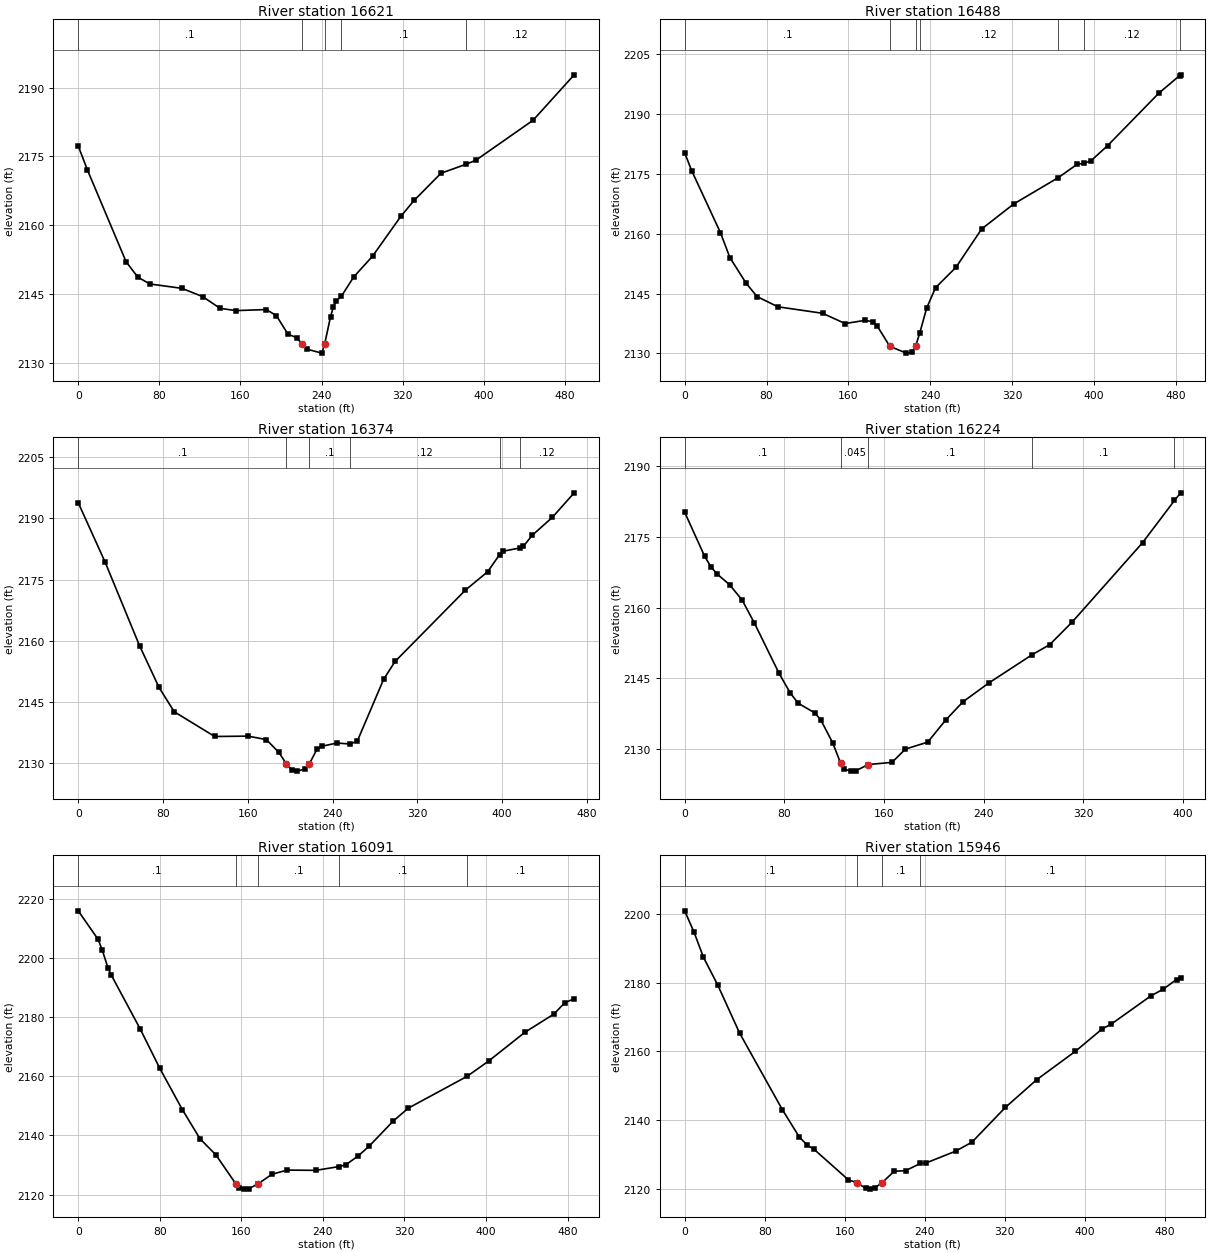
Type RM Length L Ch R = 1 ,16621   ,132.8,133.7,133.5
XS GIS Cut Line= 4
2438861.32155951616462.6252884552438945.11656114616329.709078974
2439033.24578699616211.2402835672439106.92759877616042.205538901
#Sta/Elev= 30
       0 2177.31     9.1 2172.05    47.2 2152.07    58.8 2148.69    70.6 2147.21
   102.3 2146.25   122.7 2144.46     140 2141.89   155.7  2141.4   185.6 2141.63
   195.5  2140.3   206.8  2136.3   215.5 2135.48  220.862134.146   226.1 2132.97
   240.3 2132.13  243.142134.146   248.9 2140.09   251.8 2142.29   254.6  2143.5
  259.482144.485   271.8 2148.75   290.3 2153.25   318.5 2162.03   331.3 2165.41
   357.8 2171.34  382.662173.313   392.4  2174.2   448.7  2182.9   489.2  2192.8
#Mann= 5 ,-1 , 0
       0      .1       0  220.86    .045       0  243.14     .12       0
  259.48      .1       0  382.66     .12       0
Bank Sta=220.86,243.14
XS Rating Curve= 0 ,0
Exp/Cntr(USF)=0,0
Exp/Cntr=0.3,0.1

Type RM Length L Ch R = 1 ,16488   ,108.9,114,117.4
XS GIS Cut Line= 4
2438946.56130255616516.0807205292439052.02742529616396.167183715
2439122.81975425616303.7037336412439213.83846292616115.887350679
#Sta/Elev= 30
       0 2180.31     6.9 2175.81      35 2160.29    44.2 2154.05    60.2 2147.57
    70.8 2144.27    91.1 2141.71   134.8 2140.08   156.9 2137.51   176.4 2138.31
   183.9 2137.97   188.2  2136.9  200.652131.774   216.8 2130.09   221.8 2130.27
  225.722131.776  229.942135.225   236.7 2141.46   245.3  2146.5   265.3 2151.63
   290.4 2161.23   321.8 2167.51  365.352174.107   383.7 2177.44  390.542177.714
   397.1 2178.29   413.6 2182.14   463.7 2195.31  483.96 2199.68   484.9 2199.88
#Mann= 7 ,-1 , 0
       0      .1       0  200.65    .045       0  225.72      .1       0
  229.94     .12       0  365.35      .1       0  390.54     .12       0
  483.96      .1       0
Bank Sta=200.65,225.72
XS Rating Curve= 0 ,0
Exp/Cntr(USF)=0,0
Exp/Cntr=0.3,0.1

Type RM Length L Ch R = 1 ,16374   ,149.9,149.7,149.7
XS GIS Cut Line= 4
2439002.90621743616585.4283080852439109.81708158616469.848995492
2439208.05949729616406.2803735672439316.41510284616245.914077345
#Sta/Elev= 30
       0 2193.84    25.3 2179.33    57.9  2158.8    76.3 2148.58    90.6 2142.64
   128.8 2136.58   160.3 2136.67   177.6 2135.81   189.2 2132.73   196.52129.864
   201.4 2128.45   206.2  2128.1   214.4 2128.63  218.112129.865   225.2 2133.43
     230  2134.2   244.1 2134.98  256.652134.737   263.4 2135.47   288.2 2150.58
     299 2154.95   365.4 2172.43   386.4 2176.93  397.632181.119   400.7 2181.94
  416.47 2182.73     420 2183.14   428.6 2185.89   447.5 2190.26     468 2196.25
#Mann= 6 ,-1 , 0
       0      .1       0   196.5    .045       0  218.11      .1       0
  256.65     .12       0  397.63      .1       0  416.47     .12       0
Bank Sta=196.5,218.11
XS Rating Curve= 0 ,0
Exp/Cntr(USF)=0,0
Exp/Cntr=0.3,0.1

Type RM Length L Ch R = 1 ,16224   ,132.8,133.2,133.5
XS GIS Cut Line= 4
 2439093.9249261 616660.554861272439147.38035818616620.102101862
2439275.96234343616536.3071002332439414.65751854616425.062011863
#Sta/Elev= 30
       0 2180.27      16 2170.93    21.1 2168.67    26.1 2167.14    36.1 2164.88
    46.2 2161.61      56 2156.75    75.8 2146.08    84.8 2141.91    91.2 2139.74
   104.5 2137.69   109.2 2136.25   118.8 2131.39  125.332126.977   128.3 2125.71
   133.9 2125.34   137.9 2125.47   147.4 2126.74   166.5  2127.2   177.3 2130.02
   195.2 2131.49   209.5 2136.14   223.5 2140.05   244.6  2144.1  279.23 2150.07
   293.1 2152.16   311.3 2156.99   367.7 2173.79  393.372182.755   398.3 2184.38
#Mann= 5 ,-1 , 0
       0      .1       0  125.33    .045       0   147.4      .1       0
  279.23      .1       0  393.37      .1       0
Bank Sta=125.33,147.4
XS Rating Curve= 0 ,0
Exp/Cntr(USF)=0,0
Exp/Cntr=0.3,0.1

Type RM Length L Ch R = 1 ,16091   ,145.6,144.8,143.4
XS GIS Cut Line= 4
2439125.70923706616781.913139491 2439210.9489801616734.236673047
 2439346.7546724616651.886412825 2439504.2314858616484.296409566
#Sta/Elev= 30
       0 2216.03    19.5 2206.38    23.6 2202.72    29.4 2196.51    32.4  2194.3
    60.8 2176.04    79.9  2162.8   102.1 2148.77   119.5 2138.85     135 2133.45
  154.412123.702   158.2 2122.31   162.9 2121.82   167.6 2121.99  176.782123.704
   190.2 2126.87     205 2128.27   233.1 2128.17  256.182129.476   262.3 2130.04
   274.2 2132.92   285.5  2136.4     309 2144.86   323.7 2149.21  381.442159.992
   402.5 2165.15   438.3 2174.94   466.6 2181.07   477.4 2184.95   486.5 2186.24
#Mann= 5 ,-1 , 0
       0      .1       0  154.41    .045       0  176.78      .1       0
  256.18      .1       0  381.44      .1       0
Bank Sta=154.41,176.78
XS Rating Curve= 0 ,0
Exp/Cntr(USF)=0,0
Exp/Cntr=0.3,0.1

Type RM Length L Ch R = 1 ,15946   ,123.6,121.7,120.6
XS GIS Cut Line= 4
2439222.50691136616929.2767630472439303.41243018616854.150209862
2439450.77605373616741.4603800842439573.57907336616583.983566677
#Sta/Elev= 30
       0  2200.9     9.4 2194.64    18.8 2187.35      33 2179.32    54.9  2165.3
    97.6 2143.03   114.6 2135.03   122.4 2132.73   129.4 2131.45   163.6 2122.59
   172.3 2121.76   180.7 2120.12   185.1 2119.89   190.1  2120.3  197.312121.761
   209.3 2125.09   220.7 2125.26  235.442127.355   240.7 2127.45   270.7 2130.93
     287 2133.54   320.5 2143.68   351.9 2151.77   390.5 2160.02   417.4 2166.57
     426 2167.87   465.9 2176.14     478 2178.05   491.5 2180.91   495.6 2181.34
#Mann= 4 ,-1 , 0
       0      .1       0   172.3    .045       0  197.31      .1       0
  235.44      .1       0
Bank Sta=172.3,197.31
XS Rating Curve= 0 ,0
Exp/Cntr(USF)=0,0
Exp/Cntr=0.3,0.1