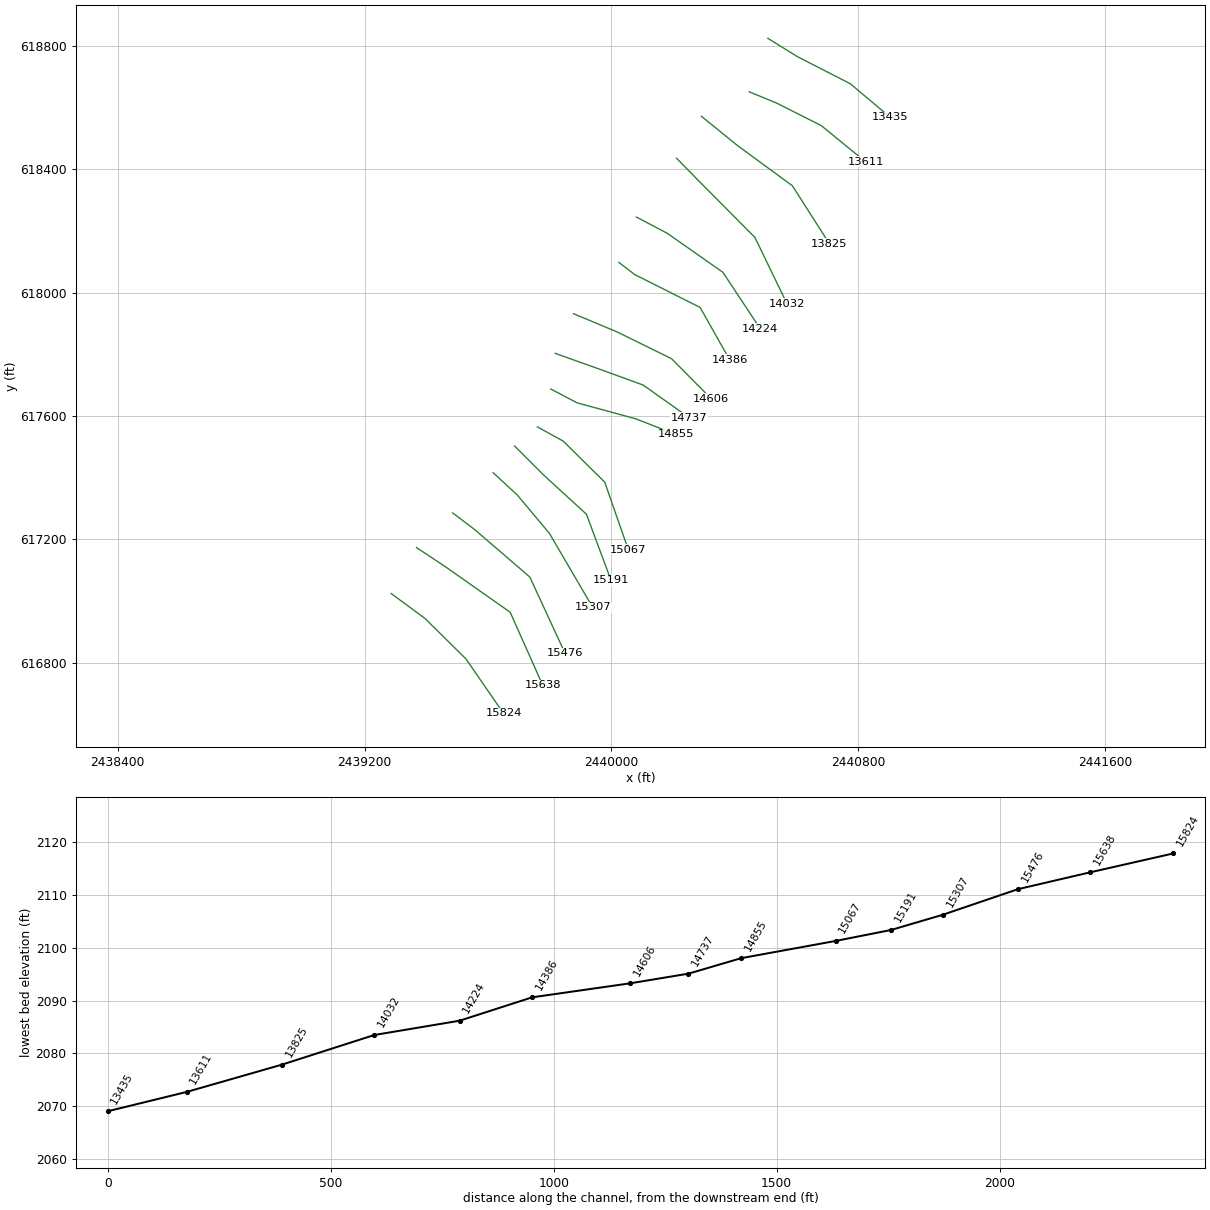
HEC-RAS study PETERSRN.prj: PETERSRN

--- PETERSRN.g01 (geometry) --- (continued)

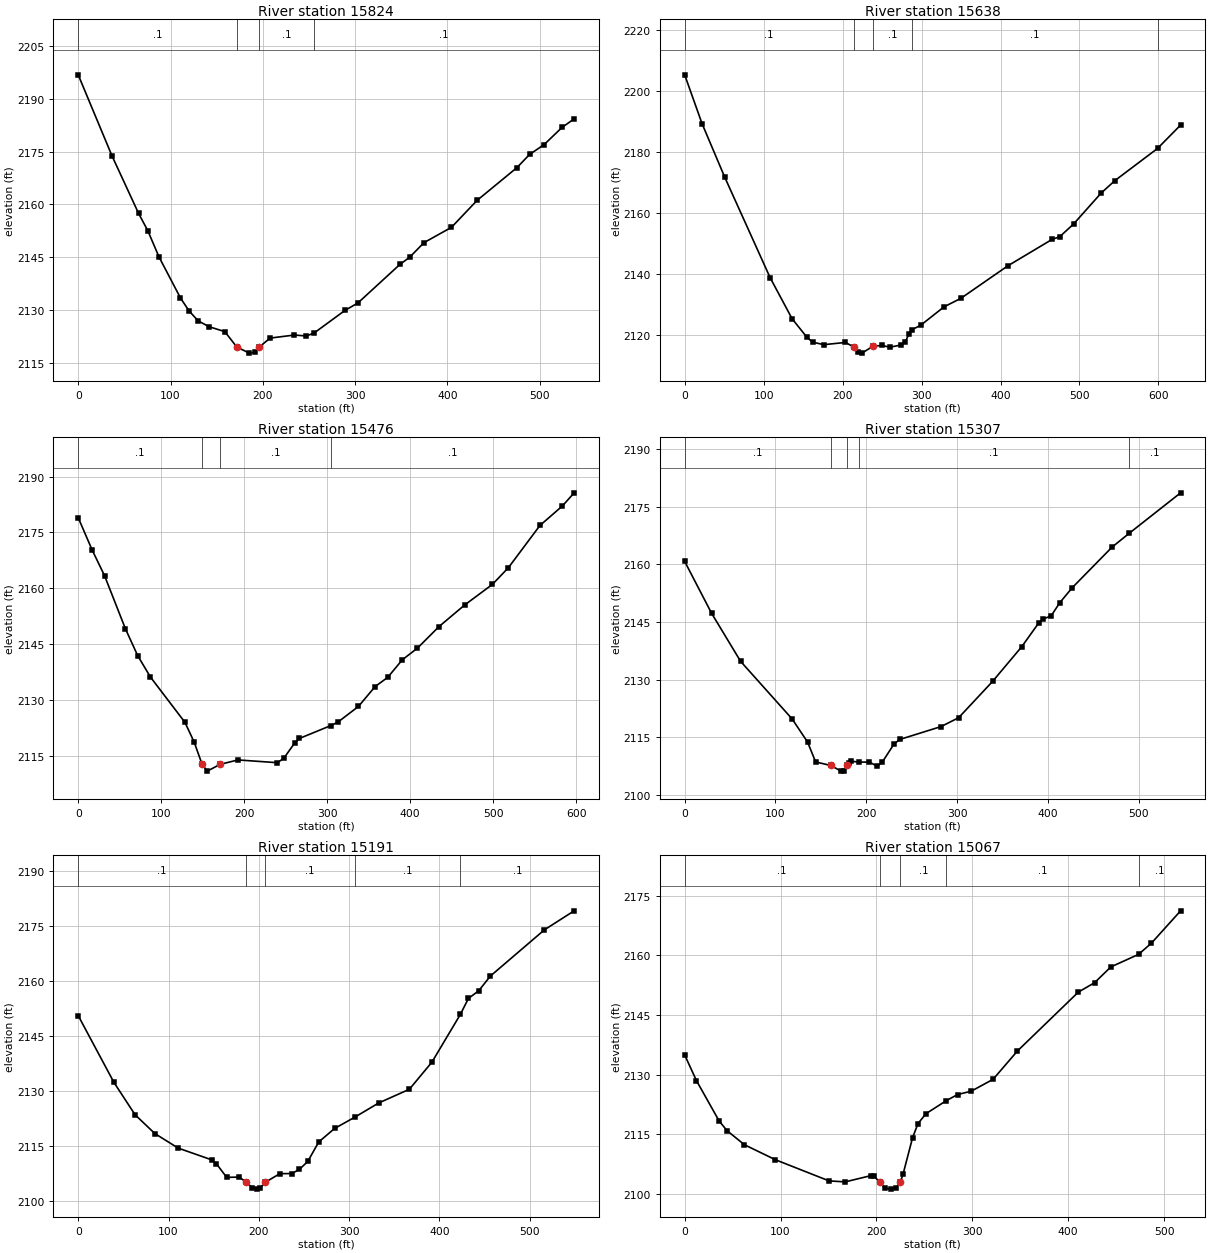
Type RM Length L Ch R = 1 ,15824   ,183.9,186.1,188.3
XS GIS Cut Line= 4
2439286.07553329617024.6296959352439395.87588025 616943.72417712
2439528.79208973616812.2527090472439650.15036795616635.994257344
#Sta/Elev= 30
       0 2196.81    36.6  2173.8    65.4 2157.47    75.4 2152.55    87.5 2145.12
   110.8 2133.44   120.1 2129.77     130 2126.94   141.8 2125.29   158.8  2123.9
  171.822119.519   185.4 2117.79   191.1    2118  196.142119.517   207.9 2122.06
   234.3 2122.93   247.3 2122.65  255.812123.548   288.9  2129.9   303.1 2132.05
   348.7 2143.02     359 2144.99   374.6 2149.16   404.4 2153.51   432.1 2161.15
   475.3 2170.46     489  2174.2   504.7 2176.98   524.1 2181.86   537.3 2184.31
#Mann= 4 ,-1 , 0
       0      .1       0  171.82    .045       0  196.14      .1       0
  255.81      .1       0
Bank Sta=171.82,196.14
XS Rating Curve= 0 ,0
Exp/Cntr(USF)=0,0
Exp/Cntr=0.3,0.1

Type RM Length L Ch R = 1 ,15638   ,162.7,162.8,160.3
XS GIS Cut Line= 4
2439368.42579351617173.4380608982439457.99976077617114.203663194
2439671.82148906616963.950556824 2439777.2876118 616727.01296601
#Sta/Elev= 30
       0 2205.23      22 2189.27    50.7 2171.78   108.3 2138.86   136.1 2125.45
   154.9 2119.39     162 2117.82   176.3    2117   203.6 2117.72  214.062116.247
   219.4 2114.61   224.5 2114.23   238.4 2116.47   250.1 2116.75   259.6 2116.16
   274.5 2116.91   279.4 2117.92   284.3 2120.62  288.052121.915     299 2123.36
   328.5 2129.37   349.7 2132.13   409.3 2142.78   465.7 2151.48   474.8 2152.25
   492.5 2156.44   527.5 2166.58     545 2170.67   598.92181.163   628.1 2188.81
#Mann= 5 ,-1 , 0
       0      .1       0  214.06    .045       0   238.4      .1       0
  288.05      .1       0   598.9      .1       0
Bank Sta=214.06,238.4
XS Rating Curve= 0 ,0
Exp/Cntr(USF)=0,0
Exp/Cntr=0.3,0.1

Type RM Length L Ch R = 1 ,15476   ,169.4,168.3,165.9
XS GIS Cut Line= 4
2439485.44984751617286.1278906752439557.68691788617231.227717194
2439735.39011099617078.0851280092439849.52468217616831.034347343
#Sta/Elev= 30
       0 2178.97    16.7 2170.35    31.8 2163.38    56.9 2149.17    71.7 2141.97
      87 2136.25   128.6  2124.1   139.7 2118.81  149.262112.852   155.5 2111.03
  171.022112.854   192.5 2114.03     240 2113.29   247.7 2114.48   261.1 2118.67
   266.4 2119.78  304.492123.252   312.9 2124.17   337.6 2128.37   357.7 2133.69
   372.9 2136.17   390.5 2140.88   408.6 2143.98   434.6 2149.76   465.4 2155.53
     499 2161.08   518.3 2165.57   556.3 2176.88   583.4 2182.12   597.5 2185.63
#Mann= 4 ,-1 , 0
       0      .1       0  149.26    .045       0  171.02      .1       0
  304.49      .1       0
Bank Sta=149.26,171.02
XS Rating Curve= 0 ,0
Exp/Cntr(USF)=0,0
Exp/Cntr=0.3,0.1

Type RM Length L Ch R = 1 ,15307   ,114.2,115.8,117.1
XS GIS Cut Line= 4
2439616.92131558617416.1546173412439694.93735158617343.917546971
2439798.95873291617219.6697859342439939.09864943616979.842712306
#Sta/Elev= 30
       0  2160.8    29.7 2147.27    61.6 2134.78   118.3 2119.79   135.3 2113.78
   144.2 2108.59   160.9 2107.67   172.2  2106.2   175.5 2106.32  179.13  2107.7
   180.7 2108.41   183.6 2108.77   191.92108.552   203.5 2108.55     212 2107.47
   217.7 2108.58   230.6  2113.3   236.9 2114.45   282.3  2117.8   301.7 2120.11
     339 2129.55   371.2 2138.61   389.7 2144.73   394.4 2145.75   403.6 2146.65
   412.9 2150.01   426.7 2153.94   470.5  2164.5  489.682168.162   546.1 2178.66
#Mann= 5 ,-1 , 0
       0      .1       0   160.9    .045       0  179.13      .1       0
   191.9      .1       0  489.68      .1       0
Bank Sta=160.9,179.13
XS Rating Curve= 0 ,0
Exp/Cntr(USF)=0,0
Exp/Cntr=0.3,0.1

Type RM Length L Ch R = 1 ,15191   ,124.8,124.7,124.4
XS GIS Cut Line= 4
2439686.26890314617502.8391017852439781.62183602617407.486168897
2439918.87226973617281.7936664532439998.33304714617067.971938157
#Sta/Elev= 30
       0 2150.57    39.5 2132.41    62.9  2123.6    84.8 2118.47   110.6 2114.51
   147.6 2111.32   153.1 2110.21   164.4 2106.53   178.5 2106.61  185.912105.183
   192.7 2103.75   198.4 2103.33   201.5  2103.6  207.062105.183   223.2 2107.54
   236.4 2107.57   244.9  2108.7   254.2 2110.88   266.3 2116.17   283.8 2119.84
  305.912122.872   332.6 2126.78   366.7 2130.53   391.6  2137.9  423.15 2150.92
     432 2155.24   443.5 2157.36   456.3 2161.34   516.2 2173.94   549.1 2179.11
#Mann= 5 ,-1 , 0
       0      .1       0  185.91    .045       0  207.06      .1       0
  305.91      .1       0  423.15      .1       0
Bank Sta=185.91,207.06
XS Rating Curve= 0 ,0
Exp/Cntr(USF)=0,0
Exp/Cntr=0.3,0.1

Type RM Length L Ch R = 1 ,15067   ,205.9,211.6,215.7
XS GIS Cut Line= 4
2439759.95071491617564.9629823042439843.74571654617518.731257267
2439978.10666743617385.8150477862440054.67796202617166.214353861
#Sta/Elev= 30
       0 2134.97    12.3 2128.51      36 2118.35    44.3 2115.92    62.3 2112.41
    94.6 2108.64   150.6 2103.32   167.4 2103.07   193.9 2104.62   197.9 2104.46
   203.5 2102.93   209.2 2101.51   214.9 2101.25   220.6 2101.57  225.092103.111
   227.8 2105.02   237.7 2114.17   243.4 2117.74   251.8 2120.23  273.092123.509
   284.7 2125.03   298.8 2125.85   321.7 2128.85   347.1 2135.97   410.6 2150.76
   427.6 2153.14   444.5 2157.09  473.452160.246   486.9 2163.08   517.3 2171.19
#Mann= 5 ,-1 , 0
       0      .1       0   203.5    .045       0  225.09      .1       0
  273.09      .1       0  473.45      .1       0
Bank Sta=203.5,225.09
XS Rating Curve= 0 ,0
Exp/Cntr(USF)=0,0
Exp/Cntr=0.3,0.1

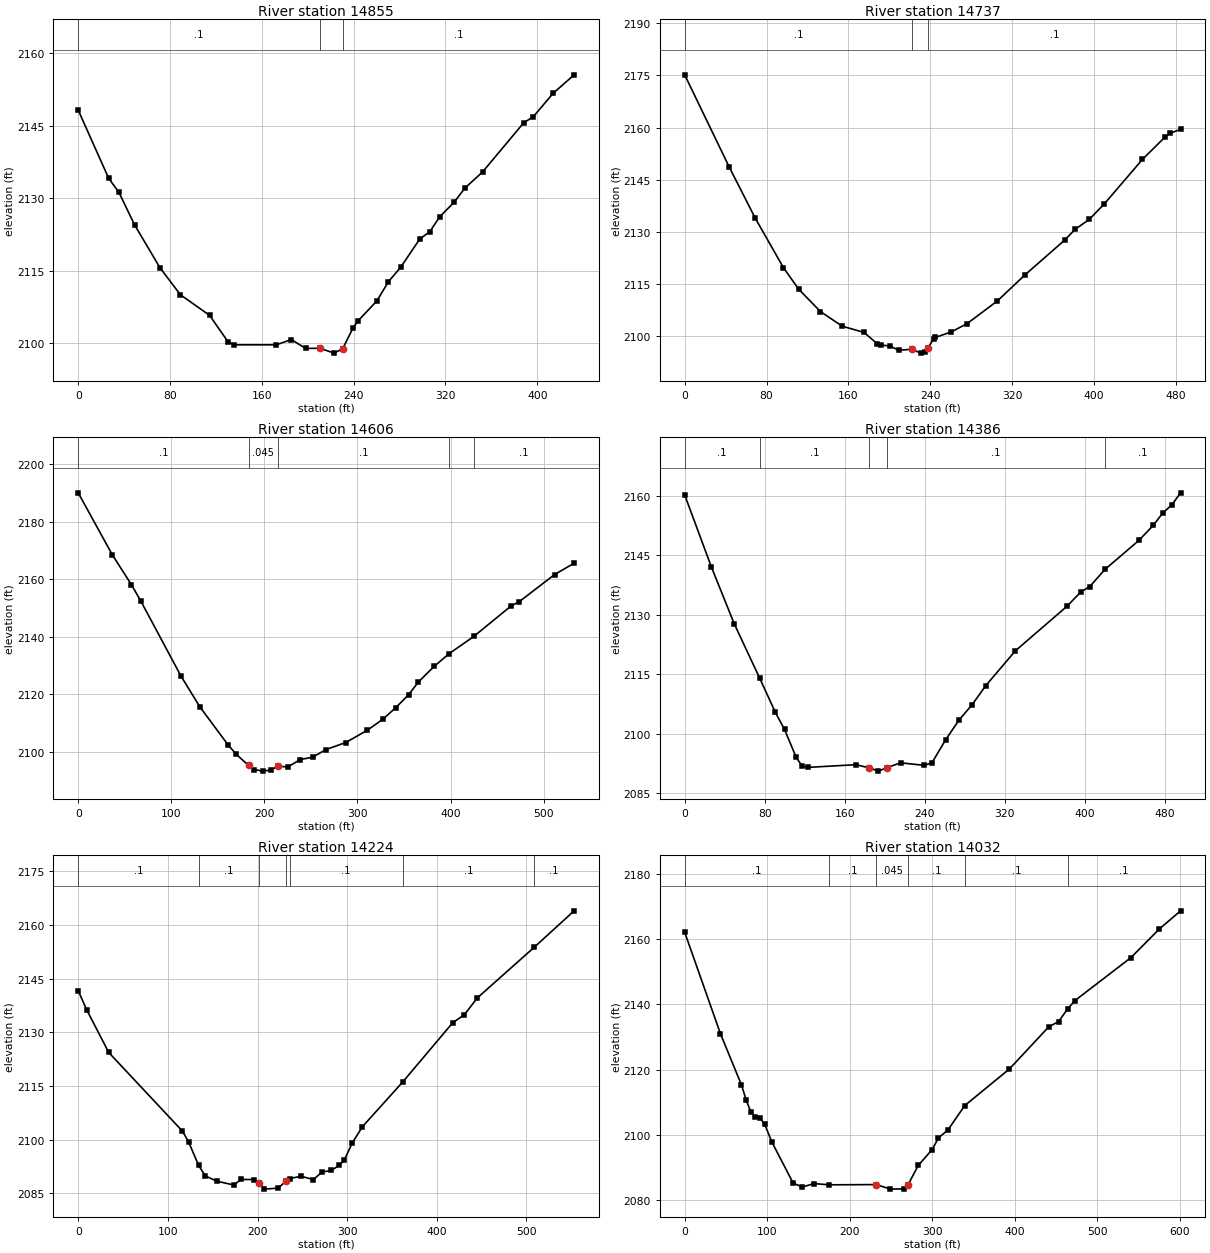
Type RM Length L Ch R = 1 ,14855   ,119,118.4,117.8
XS GIS Cut Line= 4
2439803.29295714617687.7660019332439888.53270017617642.979018303
2440079.23856595617590.9683276372440207.82055121617540.402378378
#Sta/Elev= 30
       0 2148.27    26.5 2134.19    35.5 2131.25    49.1 2124.54    71.3 2115.64
    89.1 2110.07   114.5 2105.81   130.7 2100.28   135.9 2099.72   172.6 2099.72
   185.7 2100.81   198.1 2098.97   210.5 2099.01     223    2098   230.4  2098.9
   239.5 2103.23   243.7 2104.65   260.3 2108.83   270.3 2112.79     281 2115.77
   297.7 2121.65   306.3  2123.1   314.9  2126.2   327.6 2129.23   336.8 2132.12
   352.3 2135.48     388 2145.62   396.6 2146.94   413.8 2151.76   432.1 2155.58
#Mann= 3 ,-1 , 0
       0      .1       0   210.5    .045       0   230.4      .1       0
Bank Sta=210.5,230.4
XS Rating Curve= 0 ,0
Exp/Cntr(USF)=0,0
Exp/Cntr=0.3,0.1

Type RM Length L Ch R = 1 ,14737   ,133.7,130.4,127.8
XS GIS Cut Line= 4
2439817.74037121617803.3453145252439959.32502914617752.779365266
2440102.35442847617700.7686745992440251.16279343617595.302551859
#Sta/Elev= 30
       0 2175.19    43.5 2148.68      69 2133.92    96.5 2119.71   111.5 2113.46
   132.7 2107.05     154 2102.83   175.3 2101.04     188 2097.84   191.9  2097.4
   200.8 2097.11   209.3 2095.88   222.1 2096.19   230.6 2095.07   234.9 2095.36
   237.8 2096.46   243.4 2099.22     245 2099.58   260.6 2101.17   276.2 2103.58
   305.8 2110.11   332.4 2117.51   371.7 2127.65   381.6 2130.67   395.7  2133.6
   410.3 2138.04   447.6 2150.85   469.7 2157.29   474.6 2158.38   484.9 2159.49
#Mann= 3 ,-1 , 0
       0      .1       0   222.1    .045       0   237.8      .1       0
Bank Sta=222.1,237.8
XS Rating Curve= 0 ,0
Exp/Cntr(USF)=0,0
Exp/Cntr=0.3,0.1

Type RM Length L Ch R = 1 ,14606   ,200,220.1,199.1
XS GIS Cut Line= 4
2439876.97476891617931.9272997842440018.55942684 617872.69290208
2440194.81787854617786.008417636 2440323.3998638 617655.98169097
#Sta/Elev= 30
       0 2189.99    36.6 2168.47    57.2 2158.05      67 2152.51   110.3 2126.36
   130.5 2115.68   160.9 2102.41   169.9 2099.06   183.12095.213   189.3 2093.81
   198.3 2093.25   207.2 2093.65   214.7 2095.01     225 2094.67   238.6 2097.28
   251.7 2098.08   266.3 2100.75   287.4  2103.2   310.3 2107.39   327.5 2111.35
   340.9 2115.24   354.9 2119.79   365.5 2124.25   382.4 2129.66  398.572134.099
   424.92140.049   465.2 2150.71   473.7 2152.12   511.8 2161.59   532.8 2165.52
#Mann= 5 ,-1 , 0
       0      .1       0   183.1    .045       0   214.7      .1       0
  398.57      .1       0   424.9      .1       0
Bank Sta=183.1,214.7
XS Rating Curve= 0 ,0
Exp/Cntr(USF)=0,0
Exp/Cntr=0.3,0.1

Type RM Length L Ch R = 1 ,14386   ,172.5,162.8,169.2
XS GIS Cut Line= 4
2440024.33839247618098.0725616352440074.90434173618059.064543635
2440287.28132862617952.153679488 2440382.6342615617783.118934821
#Sta/Elev= 30
       0 2160.28    26.8 2142.01    49.6 2127.72   74.992114.029    90.6 2105.45
    99.8 2101.11   111.5 2094.04   117.4 2091.88   123.4 2091.55   171.2 2092.22
   184.6 2091.42   193.6  2090.6   202.5 2091.51   215.8 2092.69   239.6 2092.06
   247.3 2092.76   260.7 2098.46   274.2 2103.49   287.3 2107.35     301 2112.18
   330.6 2120.96     382 2132.15   396.1 2135.83   404.9 2137.15  420.082141.472
   453.9 2148.77   468.4 2152.59   477.6 2155.62   486.8 2157.73   495.7 2160.79
#Mann= 5 ,-1 , 0
       0      .1       0   74.99      .1       0   184.6    .045       0
   202.5      .1       0  420.08      .1       0
Bank Sta=184.6,202.5
XS Rating Curve= 0 ,0
Exp/Cntr(USF)=0,0
Exp/Cntr=0.3,0.1

Type RM Length L Ch R = 1 ,14224   ,191.4,191.3,190.9
XS GIS Cut Line= 4
2440080.68330736 618245.436185192440181.81520588618191.980753116
2440360.96314039618066.2882506722440482.32141862617882.806091932
#Sta/Elev= 30
       0 2141.65     9.3 2136.38      34 2124.39   116.3 2102.38   123.3 2099.29
  134.182092.877   141.7 2089.88   154.6  2088.4   173.3 2087.35   181.9 2088.88
   196.2 2088.86     202  2087.9   207.7 2086.18     223 2086.46  231.832088.427
  235.772089.128   248.6 2089.78   262.3 2088.85   271.9 2090.96   282.4 2091.39
   291.4 2092.89   296.8 2094.27   305.4 2098.97   316.9 2103.59  361.982116.132
   417.8  2132.7   430.7 2134.92   445.2 2139.63  508.452153.739   553.2 2163.97
#Mann= 7 ,-1 , 0
       0      .1       0  134.18      .1       0     202    .045       0
  231.83      .1       0  235.77      .1       0  361.98      .1       0
  508.45      .1       0
Bank Sta=202,231.83
XS Rating Curve= 0 ,0
Exp/Cntr(USF)=0,0
Exp/Cntr=0.3,0.1

Type RM Length L Ch R = 1 ,14032   ,204.1,207.1,207.1
XS GIS Cut Line= 4
2440210.71003402618436.1420509672440280.05762158618365.349722005
2440464.98452173 618178.978080452440569.00590306617963.711610747
#Sta/Elev= 30
       0 2162.12    43.3 2131.07    68.8 2115.36    74.5 2110.74    80.1 2107.14
    85.7 2105.54    91.4 2105.11    96.9 2103.33   105.6  2097.9   131.3 2085.36
   142.3  2084.1   156.5 2085.18  174.892084.799   232.2 2084.87   249.1 2083.48
     266 2083.57  270.372084.719   282.9 2090.74   299.8  2095.6   307.4 2099.18
   318.7 2101.54  339.272109.067   393.3 2120.25   440.9 2133.14   452.9 2134.78
  464.032138.715   472.8 2141.22   540.4 2154.32     575 2163.13   600.7 2168.67
#Mann= 6 ,-1 , 0
       0      .1       0  174.89      .1       0   232.2    .045       0
  270.37      .1       0  339.27      .1       0  464.03      .1       0
Bank Sta=232.2,270.37
XS Rating Curve= 0 ,0
Exp/Cntr(USF)=0,0
Exp/Cntr=0.3,0.1

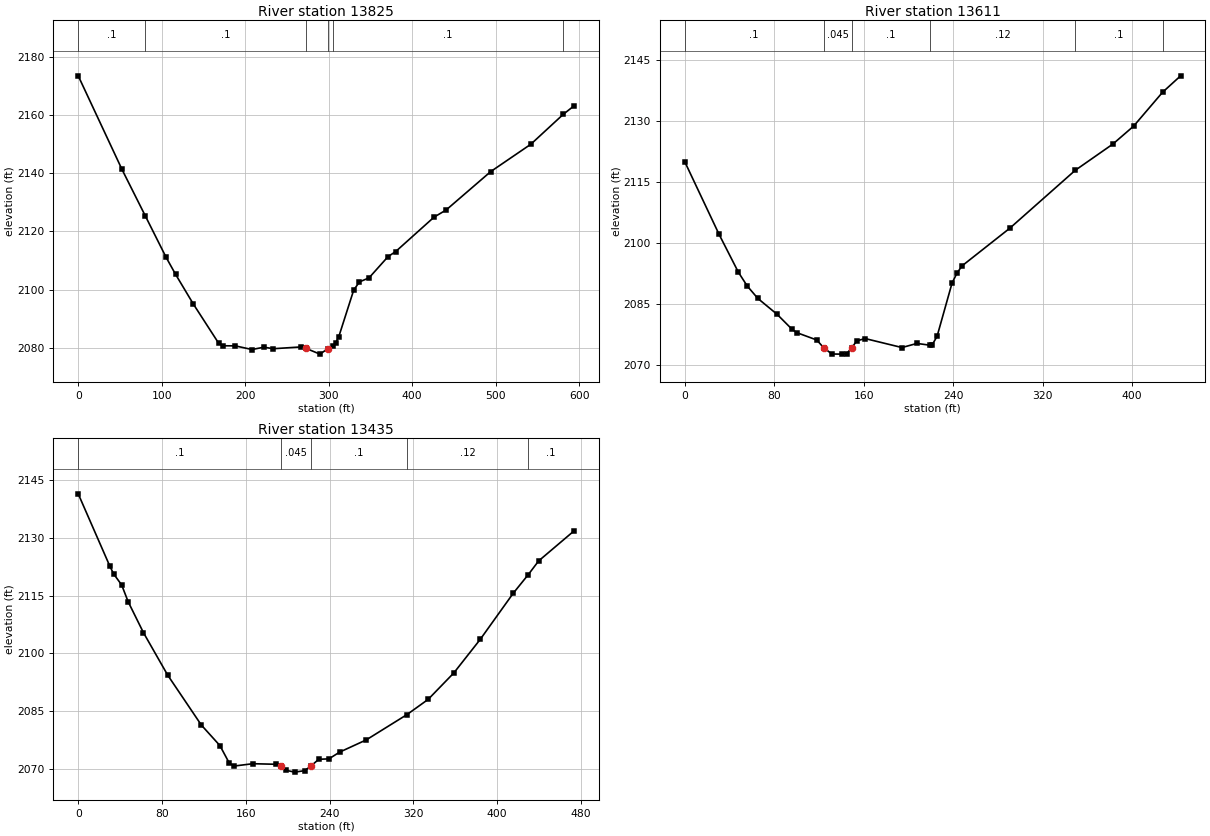
Type RM Length L Ch R = 1 ,13825   ,211.5,213.8,216.1
XS GIS Cut Line= 4
2440291.61555284618571.9477432632440407.19486543618478.039551782
2440586.34279995618346.5680837082440706.25633676618158.751700746
#Sta/Elev= 30
       0 2173.46    52.4 2141.33   80.232125.433   105.3 2111.11   116.7 2105.24
     138 2095.03   168.2 2081.63   173.7 2080.75   188.1 2080.72   208.1 2079.46
   222.4 2080.26   233.8 2079.74   267.4 2080.36   272.4 2079.91   289.5 2077.88
  299.13 2079.77  305.092080.751   308.2 2081.64   312.1 2083.88     330 2099.91
   336.9 2102.69   348.3 2104.07   371.1 2111.37   380.2  2113.1   426.2 2124.93
   440.7 2127.39   494.1 2140.58   542.1 2149.96  581.052160.262     594 2163.18
#Mann= 6 ,-1 , 0
       0      .1       0   80.23      .1       0   272.4    .045       0
  299.13      .1       0  305.09      .1       0  581.05      .1       0
Bank Sta=272.4,299.13
XS Rating Curve= 0 ,0
Exp/Cntr(USF)=0,0
Exp/Cntr=0.3,0.1

Type RM Length L Ch R = 1 ,13611   ,176.8,176.7,178.1
XS GIS Cut Line= 4
2440446.20288343 618651.408520672440534.33210928618615.289985485
2440680.25099143618541.6081737082440823.28039076618424.584119708
#Sta/Elev= 30
       0  2120.1    30.8 2102.16    48.1 2092.83      56 2089.46    65.4 2086.43
    82.7  2082.5    95.8 2078.89   100.2 2078.01   118.1  2076.2  124.152074.337
   131.6 2072.75   140.5 2072.72     145 2072.86  149.472074.337     154    2076
   161.4 2076.55   194.3 2074.34   207.7 2075.35   219.72074.902   221.2 2074.95
   225.7 2077.09   239.1 2090.21   243.6  2092.7   248.1 2094.45   290.8 2103.71
  349.252117.942     383 2124.42   401.5 2128.82  427.382137.152   443.5 2141.19
#Mann= 6 ,-1 , 0
       0      .1       0  124.15    .045       0  149.47      .1       0
   219.7     .12       0  349.25      .1       0  427.38      .1       0
Bank Sta=124.15,149.47
XS Rating Curve= 0 ,0
Exp/Cntr(USF)=0,0
Exp/Cntr=0.3,0.1

Type RM Length L Ch R = 1 ,13435   ,196.7,198.5,196.9
XS GIS Cut Line= 4
2440506.88202254618824.7774895592440602.23495543618765.543091855
2440774.15918291618677.4138660042440902.74116817618569.058260449
#Sta/Elev= 30
       0 2141.48    30.3  2122.6    33.9 2120.62    41.5 2117.77    47.7 2113.41
    62.3 2105.36    85.5 2094.29   117.6 2081.32   135.3 2075.99   144.3 2071.41
   148.8 2070.66   166.8 2071.27   189.2 2071.12   193.52070.612   198.2 2069.57
   206.7 2069.08   216.2 2069.46  221.982070.611   229.7 2072.42   239.4 2072.53
   249.6 2074.28   275.1 2077.47  314.052084.067   334.2 2088.01   358.8 2094.92
   383.9 2103.61   415.5 2115.64  429.812120.469   439.7 2124.03   473.6 2131.86
#Mann= 5 ,-1 , 0
       0      .1       0   193.5    .045       0  221.98      .1       0
  314.05     .12       0  429.81      .1       0
Bank Sta=193.5,221.98
XS Rating Curve= 0 ,0
Exp/Cntr(USF)=0,0
Exp/Cntr=0.3,0.1