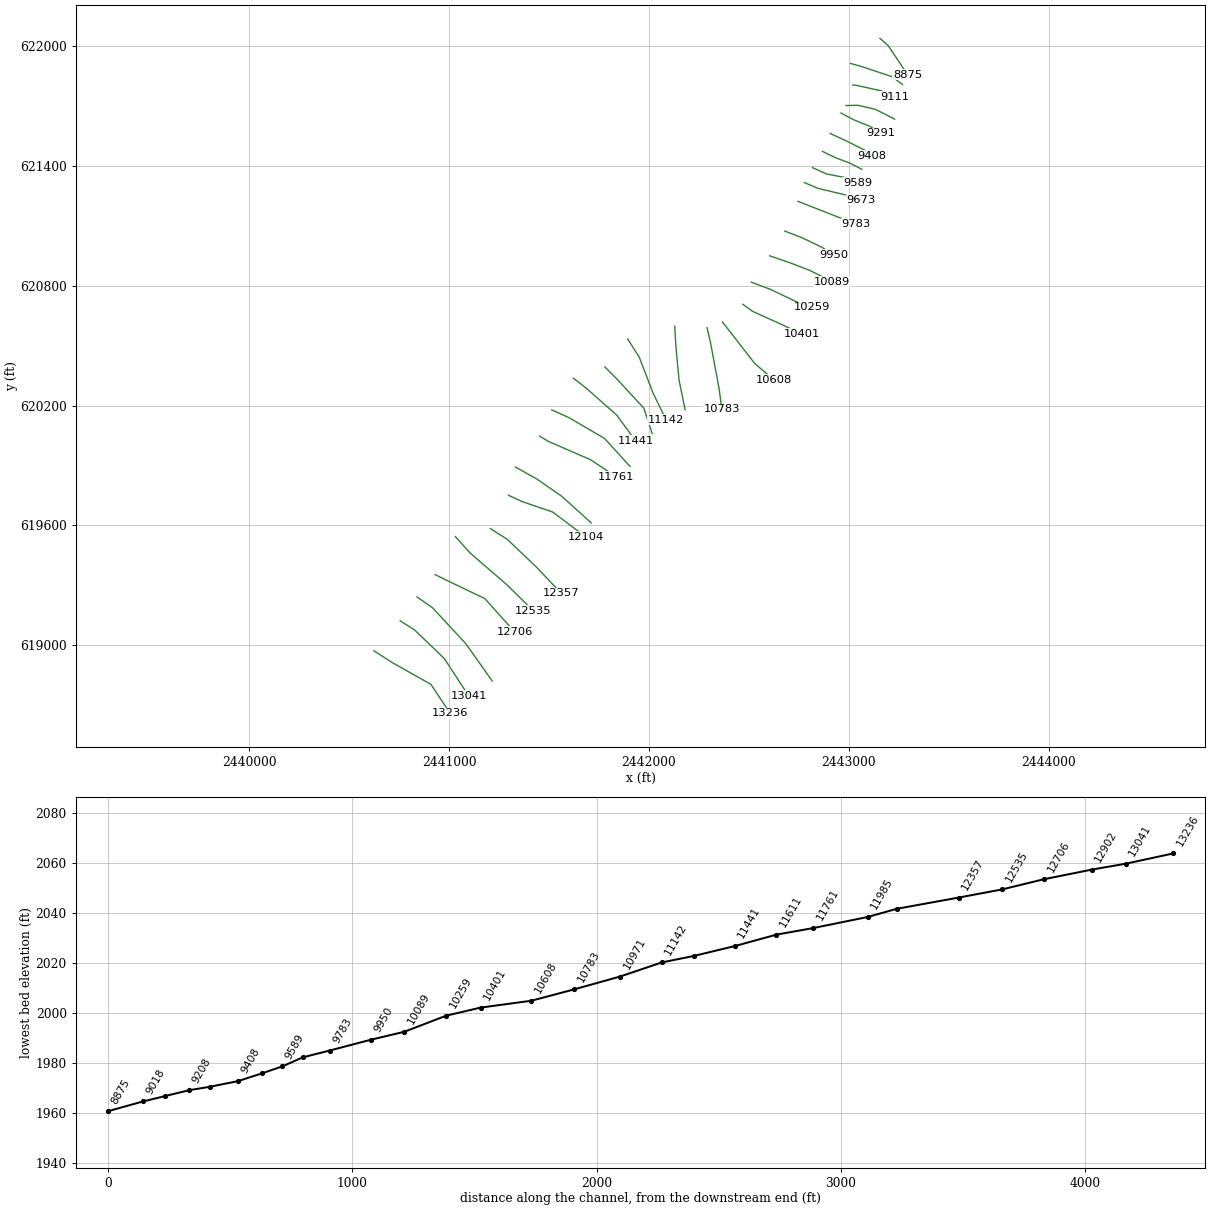
HEC-RAS study PETERSRN.prj: PETERSRN

--- PETERSRN.g01 (geometry) --- (continued)

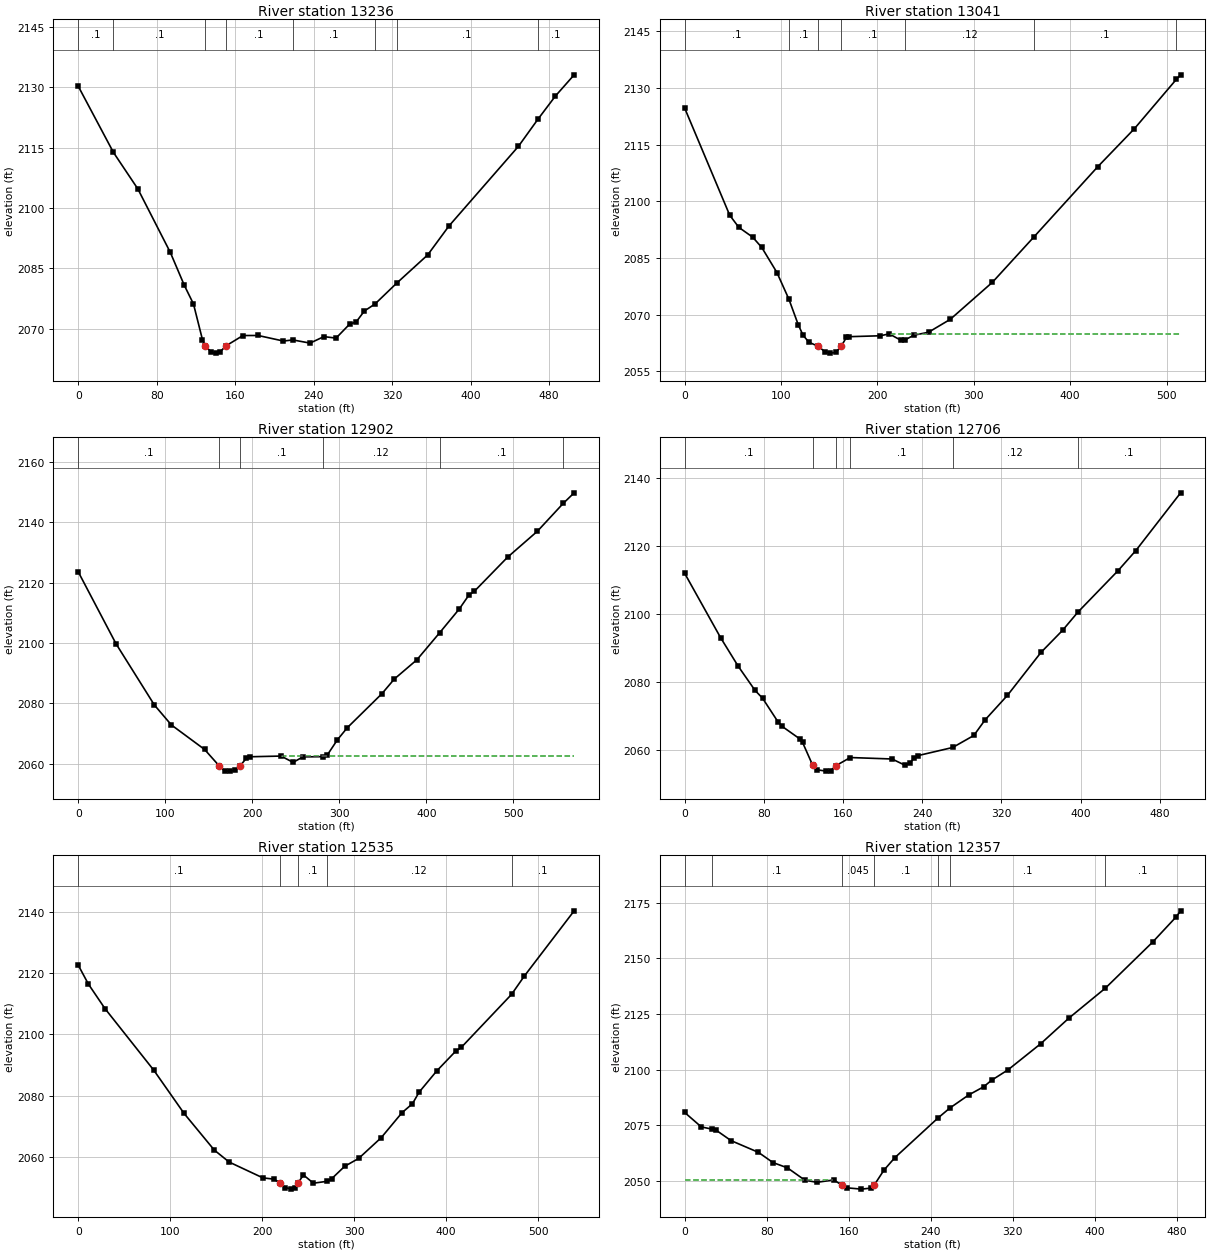
Type RM Length L Ch R = 1 ,13236   ,196.5,195.2,192.3
XS GIS Cut Line= 4
2440623.90607654618972.1411131142440717.81426802618911.461974003
 2440908.5201338618804.551109855 2441005.3178081618658.632227708
#Sta/Elev= 30
       0 2130.26    35.9 2113.81    60.8 2104.74    93.9 2088.96   108.2 2080.77
   117.5 2076.16   126.6 2067.34   129.72065.697   135.8 2064.18   140.4 2063.96
     145 2064.34  150.182065.699   167.9 2068.33   183.4 2068.34   209.2 2066.96
  218.762067.239   236.3 2066.45   250.4 2068.06   262.8 2067.69   276.6 2071.15
   283.3  2071.7   291.7 2074.43   302.5 2076.16  324.492081.308   356.2 2088.35
   377.9 2095.54   448.7 2115.32  468.48 2122.02   486.4 2127.81   505.5 2133.08
#Mann= 8 ,-1 , 0
       0      .1       0    35.9      .1       0   129.7    .045       0
  150.18      .1       0  218.76      .1       0   302.5     .12       0
  324.49      .1       0  468.48      .1       0
Bank Sta=129.7,150.18
XS Rating Curve= 0 ,0
Exp/Cntr(USF)=0,0
Exp/Cntr=0.3,0.1

Type RM Length L Ch R = 1 ,13041   ,139.6,139.1,138.2
XS GIS Cut Line= 4
2440755.37754461619122.3942194842440827.61461499619076.162494447
2440976.42297995618933.1330951142441097.78125817618746.761453559
#Sta/Elev= 30
       0 2124.63    46.7 2096.32    56.2 2093.09    70.5 2090.52      80 2087.78
    95.7 2081.16  108.182074.077   117.8 2067.38   122.8 2064.58   128.9 2062.73
  138.442061.651   145.6  2060.2   151.1 2059.84   156.7 2060.02  162.412061.651
   167.8    2064   170.9 2064.19     203 2064.43   212.2 2064.93   224.7  2063.2
  228.912063.375   237.7 2064.57     253 2065.36   275.6 2068.78   319.3 2078.57
  362.452090.583   428.4 2109.07   466.7  2119.2  510.082132.202   514.6 2133.43
#Mann= 7 ,-1 , 0
       0      .1       0  108.18      .1       0  138.44    .045       0
  162.41      .1       0  228.91     .12       0  362.45      .1       0
  510.08      .1       0
#XS Ineff= 2 , 0
                          213.77         2064.94
Permanent Ineff=
       F       F
Bank Sta=138.44,162.41
XS Rating Curve= 0 ,0
Exp/Cntr(USF)=0,0
Exp/Cntr=0.3,0.1

Type RM Length L Ch R = 1 ,12902   ,189.4,195.6,199
XS GIS Cut Line= 4
2440839.17254624619242.3077562982440917.18858224619187.407582817
 2441083.3338441619008.2596482992441216.25005358618820.443265337
#Sta/Elev= 30
       0 2123.63    43.5 2099.71    87.5 2079.42     107 2072.81   145.2 2064.66
  162.23 2059.13   168.3 2057.54   174.2 2057.47     180 2057.69  185.752059.127
   193.1 2061.73   197.7 2062.24     233 2062.47   246.9 2060.38   258.2  2062.2
  281.12 2062.27   285.9  2062.7   297.8 2067.87   309.1 2071.86   348.9 2083.16
   363.2 2088.04   389.1 2094.42  415.492103.471   437.9 2111.32   449.2 2116.03
   455.1 2117.15   493.3 2128.47   527.6  2137.1  557.192146.316   569.8 2149.84
#Mann= 6 ,-1 , 0
       0      .1       0  162.23    .045       0  185.75      .1       0
  281.12     .12       0  415.49      .1       0  557.19      .1       0
#XS Ineff= 2 , 0
                          234.01         2062.58
Permanent Ineff=
       F       F
Bank Sta=162.23,185.75
XS Rating Curve= 0 ,0
Exp/Cntr(USF)=0,0
Exp/Cntr=0.3,0.1

Type RM Length L Ch R = 1 ,12706   ,175.6,171,168.3
XS GIS Cut Line= 4
2440930.19125491619353.5528446682441009.65203232619314.544826668
2441178.68677698619233.6393078542441328.93988335619066.049304595
#Sta/Elev= 30
       0 2111.97    36.3 2092.98    54.1 2084.55    71.1 2077.43    78.7 2075.12
    94.2 2068.19    98.6 2066.79   116.1 2063.17   119.1 2062.08  129.21 2055.42
   134.1    2054   142.9 2053.62   147.4 2053.71   152.6 2055.19  167.24 2057.63
   209.5  2057.2   222.8 2055.32   227.2 2055.88   231.6 2057.41     236 2058.22
  270.752060.597   292.1 2064.14   303.4 2068.71   326.1 2075.99   359.9 2088.63
   381.7 2095.14  397.19 2100.51   437.8 2112.76   455.8  2118.7     501 2135.72
#Mann= 6 ,-1 , 0
       0      .1       0  129.21    .045       0   152.6      .1       0
  167.24      .1       0  270.75     .12       0  397.19      .1       0
Bank Sta=129.21,152.6
XS Rating Curve= 0 ,0
Exp/Cntr(USF)=0,0
Exp/Cntr=0.3,0.1

Type RM Length L Ch R = 1 ,12535   ,176.1,178.6,178.4
XS GIS Cut Line= 4
2441031.32315343619544.2587104452441105.00496521619461.908450224
2441284.15289972619307.3211196312441421.40333343619172.960168743
#Sta/Elev= 30
       0  2122.6    11.1  2116.4    29.1 2108.42    82.3 2088.27   115.1 2074.23
   147.9 2062.29   164.1 2058.37   200.8 2053.21   213.1 2052.79  219.412051.415
   225.3 2050.06   231.5 2049.54   235.8 2050.07  238.622051.414   244.9 2054.16
   255.7 2051.47  270.652052.098   275.5 2052.91   289.7 2056.98   304.9 2059.55
   329.4 2066.31   352.1 2074.49   363.4 2077.39   370.6 2081.15   389.9 2088.12
   410.6  2094.6   416.4 2095.74  471.142113.058     485 2119.02   539.2 2140.31
#Mann= 5 ,-1 , 0
       0      .1       0  219.41    .045       0  238.62      .1       0
  270.65     .12       0  471.14      .1       0
Bank Sta=219.41,238.62
XS Rating Curve= 0 ,0
Exp/Cntr(USF)=0,0
Exp/Cntr=0.3,0.1

Type RM Length L Ch R = 1 ,12357   ,241.3,253,254.9
XS GIS Cut Line= 4
2441206.13686372619584.7114698532441289.93186535619531.256037779
 2441435.8507475619392.5608626682441561.54324995619259.644653187
#Sta/Elev= 30
       0 2080.73    16.2 2074.24   26.282073.273    30.7 2072.75    45.2 2068.08
    71.9  2062.8    86.1  2058.2   100.2 2055.83   117.3 2050.25     129 2049.33
   145.5 2050.39  153.032048.124     158 2046.85   172.3 2046.26   181.2  2046.7
  184.882048.121   194.3  2054.8   204.9 2060.39  247.162078.311  258.642082.749
   277.1 2088.65   291.5 2092.27   299.2  2095.2   315.3  2099.9   347.1 2111.62
   374.8 2123.22  410.162136.609   456.3 2157.34   479.4 2168.76   483.6 2171.41
#Mann= 7 ,-1 , 0
       0      .1       0   26.28      .1       0  153.03    .045       0
  184.88      .1       0  247.16     .12       0  258.64      .1       0
  410.16      .1       0
#XS Ineff= 2 , 0
          144.62 2050.34
Permanent Ineff=
       F       F
Bank Sta=153.03,184.88
XS Rating Curve= 0 ,0
Exp/Cntr(USF)=0,0
Exp/Cntr=0.3,0.1

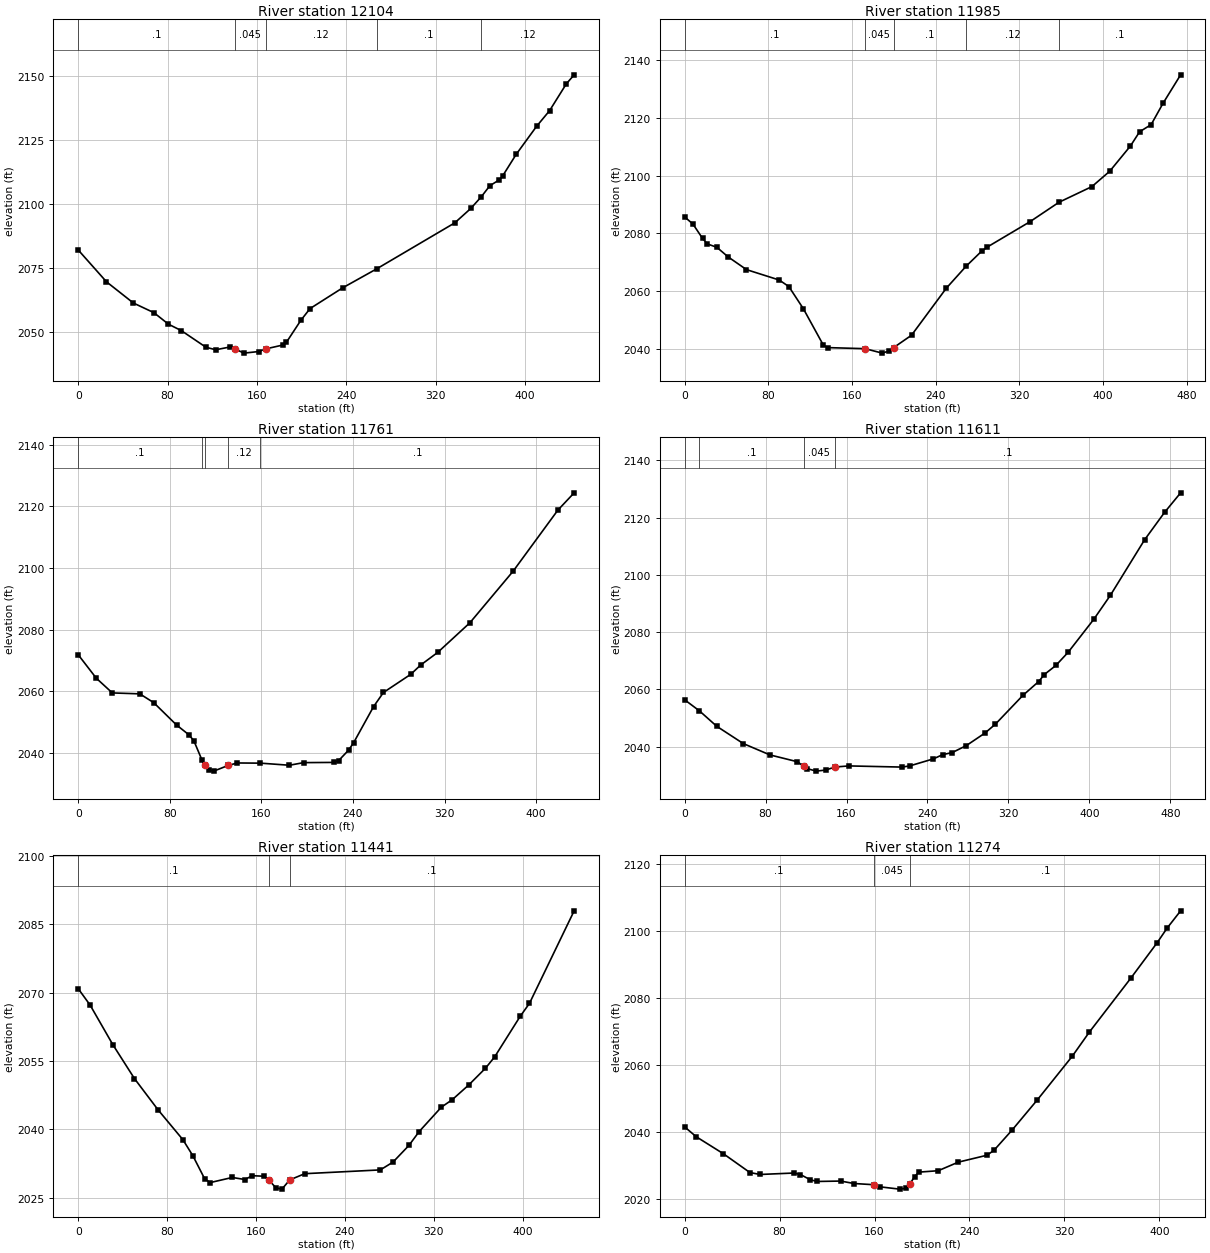
Type RM Length L Ch R = 1 ,12104   ,121,119,113.4
XS GIS Cut Line= 4
2441297.15557239619750.8567317042441366.50315995619719.072420741
2441518.20100772619667.0617300752441684.34626957619542.813969038
#Sta/Elev= 30
       0 2082.04    25.3 2069.62    49.4 2061.33    67.8 2057.56    80.8 2053.07
    92.4 2050.54   114.4 2044.06   123.1 2043.08   135.7 2044.15     140 2043.49
   148.4 2041.77   161.6 2042.39  167.982043.423   183.7 2044.98   186.5 2046.04
   199.4  2054.6   207.6 2059.16   236.9 2067.28  267.372074.693   337.2 2092.62
   351.5 2098.23  361.052102.859   368.6 2107.12   377.2 2109.44     380  2110.9
   392.2 2119.37   410.6 2130.39   422.1 2136.42   437.1  2146.9   444.1 2150.41
#Mann= 5 ,-1 , 0
       0      .1       0     140    .045       0  167.98     .12       0
  267.37      .1       0  361.05     .12       0
Bank Sta=140,167.98
XS Rating Curve= 0 ,0
Exp/Cntr(USF)=0,0
Exp/Cntr=0.3,0.1

Type RM Length L Ch R = 1 ,11985   ,219.3,223.6,225
XS GIS Cut Line= 4
2441331.82936617619892.4413896292441440.18497172619831.762250519
2441562.98799135619746.5225074822441711.79635632619612.161556593
#Sta/Elev= 30
       0 2085.66     7.9 2083.21    17.1 2078.23    21.7 2076.32    30.8 2075.15
    41.5 2071.84    59.1 2067.42    90.4 2063.82    99.6 2061.55   113.4 2053.92
   132.7 2041.19     137  2040.4   172.6 2040.03   188.9 2038.49   195.5 2039.25
  199.722040.384   216.9 2044.69   250.2    2061  268.952068.545   284.1 2073.87
   289.5 2075.28   329.9 2083.96  357.922090.763   389.4 2096.19   406.4  2101.5
   426.2 2110.25     435 2115.19     446 2117.65   457.3 2124.99   474.2 2134.91
#Mann= 5 ,-1 , 0
       0      .1       0   172.6    .045       0  199.72      .1       0
  268.95     .12       0  357.92      .1       0
Bank Sta=172.6,199.72
XS Rating Curve= 0 ,0
Exp/Cntr(USF)=0,0
Exp/Cntr=0.3,0.1

Type RM Length L Ch R = 1 ,11761   ,150.3,149.7,147.3
XS GIS Cut Line= 4
2441453.18764439620047.0287202222441496.52988661620021.023374888
 2441708.9068735619928.5599248152441834.59937594619844.764923185
#Sta/Elev= 30
       0 2071.84    15.8 2064.22    29.8 2059.44    53.8 2059.14      66 2056.27
    85.9 2049.02    96.6 2045.87     101 2043.92  108.242037.514  110.442035.891
     114  2034.4   118.4 2034.04  131.022035.891     139 2036.69  159.192036.631
   184.5 2035.95   196.9  2036.8   223.1 2036.87   227.5 2037.47   236.2 2040.87
   240.6 2043.29     258    2055   266.6 2059.58   290.5 2065.49   299.1 2068.49
     314 2072.59   342.1 2082.21   379.9 2098.98     419 2118.82   433.2 2124.43
#Mann= 5 ,-1 , 0
       0      .1       0  108.24     .12       0  110.44    .045       0
  131.02     .12       0  159.19      .1       0
Bank Sta=110.44,131.02
XS Rating Curve= 0 ,0
Exp/Cntr(USF)=0,0
Exp/Cntr=0.3,0.1

Type RM Length L Ch R = 1 ,11611   ,174.4,170.6,165.4
XS GIS Cut Line= 4
 2441513.8667835620178.5001882952441600.55126795620139.492170295
2441778.25446106620035.4707889622441905.39170491619895.330872444
#Sta/Elev= 30
       0 2056.33   14.542052.476    31.7 2047.08      58 2041.03    84.3 2037.08
   111.5 2034.69  117.452033.111   120.8 2032.33     130 2031.42   139.3 2031.79
   148.6 2032.86   162.5 2033.24     215 2032.83   222.5 2033.25   245.9 2035.71
     255 2037.17   264.5 2037.91   278.4 2040.34   296.9 2044.74   307.2 2047.85
   334.2 2057.84   349.9 2062.71   355.5 2065.16   366.9 2068.33   379.1 2072.96
   404.4 2084.46   420.8 2092.84   454.6 2112.22   474.3 2121.78   490.2 2128.62
#Mann= 4 ,-1 , 0
       0      .1       0   14.54      .1       0  117.45    .045       0
   148.6      .1       0
Bank Sta=117.45,148.6
XS Rating Curve= 0 ,0
Exp/Cntr(USF)=0,0
Exp/Cntr=0.3,0.1

Type RM Length L Ch R = 1 ,11441   ,159.7,166.1,164.4
XS GIS Cut Line= 4
2441622.22238906 620337.42174311 2441688.6804938620285.411052443
2441838.93360017620152.4948429622441934.28653306620022.468116296
#Sta/Elev= 30
       0 2070.85    10.7 2067.25    31.1 2058.58    50.6 2051.11    71.8 2044.26
    94.2 2037.69   103.2 2034.15   113.8 2029.09   118.8 2028.28   138.6  2029.4
     150 2028.95   156.6 2029.79   167.3 2029.67   171.7  2028.8   177.9 2027.11
   183.3 2026.84  190.232028.854   203.8 2030.23   271.8 2031.06   283.2 2032.77
   297.5 2036.42   306.8 2039.49   326.7 2044.83   336.6 2046.49   351.5 2049.74
   366.4 2053.38   374.7 2055.88   397.6 2064.76     406 2067.63   446.2 2087.94
#Mann= 3 ,-1 , 0
       0      .1       0   171.7    .045       0  190.23      .1       0
Bank Sta=171.7,190.23
XS Rating Curve= 0 ,0
Exp/Cntr(USF)=0,0
Exp/Cntr=0.3,0.1

Type RM Length L Ch R = 1 ,11274   ,134.9,132.9,127.5
XS GIS Cut Line= 4
2441779.69920246620393.7666579982441834.59937594620338.866484517
2441974.73929246 620187.168636742442016.63679328620060.031392888
#Sta/Elev= 30
       0  2041.5     9.8 2038.56    32.6  2033.5      55 2027.87    63.6  2027.3
    91.9 2027.73    97.5 2027.29     106  2025.7   111.7 2025.21   131.5 2025.33
   142.7  2024.6   159.3 2024.24   164.7  2023.6   181.1 2022.92   186.5 2023.16
   189.9 2024.54   193.8 2026.65   197.4    2028   213.7 2028.42   230.6 2030.98
   254.7 2033.04   260.6 2034.48   275.9 2040.54   297.1 2049.53   326.6 2062.59
   341.1 2069.85   376.3 2086.08   398.2 2096.53   406.6  2100.9     418 2106.07
#Mann= 3 ,-1 , 0
       0      .1       0   159.3    .045       0   189.9      .1       0
Bank Sta=159.3,189.9
XS Rating Curve= 0 ,0
Exp/Cntr(USF)=0,0
Exp/Cntr=0.3,0.1

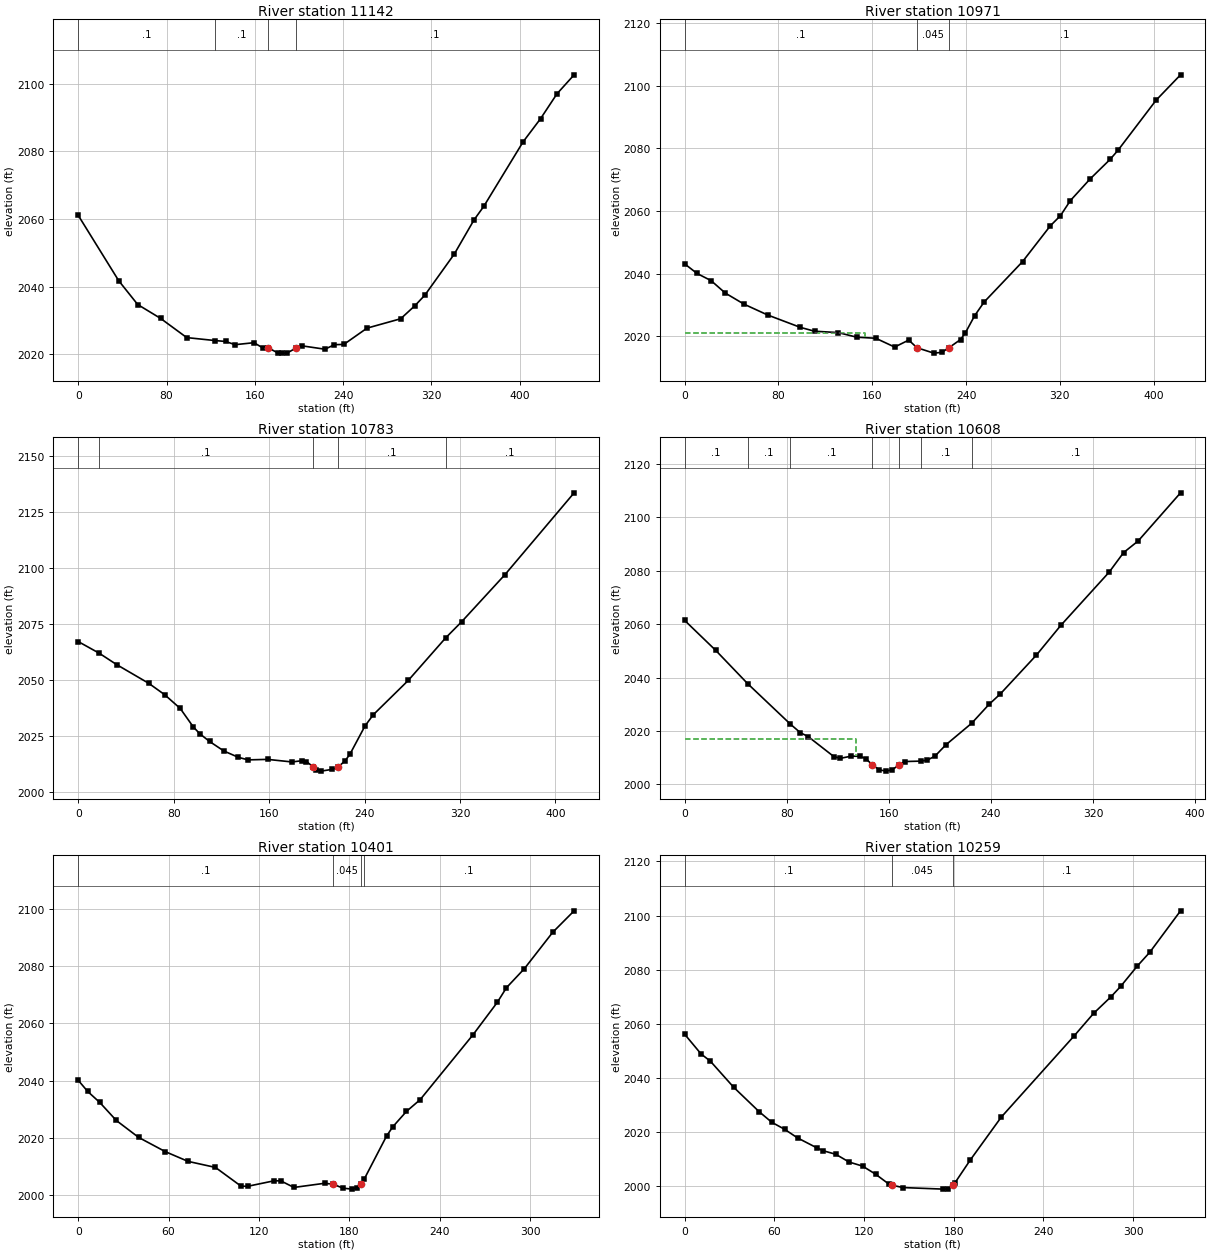
Type RM Length L Ch R = 1 ,11142   ,172.6,170.3,166.1
XS GIS Cut Line= 4
2441893.83377365620533.9065745162441951.62342994 620442.88786585
 2442020.9710175620262.2951899252442085.98438083620129.378980444
#Sta/Elev= 30
       0 2061.09    36.7 2041.72    53.9 2034.67    74.6 2030.57    98.3 2024.88
  123.612024.014   133.5 2023.73   142.1 2022.78   159.2 2023.37   167.8 2021.71
   172.3 2021.81   180.7 2020.36   184.5 2020.28   189.2 2020.31   196.9 2021.71
   203.1 2022.42   223.5 2021.44   232.1 2022.78   240.6 2022.86   261.6 2027.68
   292.1 2030.46   305.1 2034.36     314 2037.45   340.7 2049.64   358.5 2059.72
   367.4 2063.76     403 2082.86   418.8 2089.71   433.7 2097.09   449.2  2102.7
#Mann= 4 ,-1 , 0
       0      .1       0  123.61      .1       0   172.3    .045       0
   196.9      .1       0
Bank Sta=172.3,196.9
XS Rating Curve= 0 ,0
Exp/Cntr(USF)=0,0
Exp/Cntr=0.3,0.1

Type RM Length L Ch R = 1 ,10971   ,188.6,188.5,189.6
XS GIS Cut Line= 4
2442129.32662305620597.4751964422442135.10558868620496.343297924
2442150.99774417620327.3085532582442181.33731372620178.500188295
#Sta/Elev= 30
       0 2043.14    10.6 2040.07    22.6 2037.77    34.6 2033.83    50.7 2030.26
    70.7 2026.83    98.7 2022.86   110.8 2021.63   130.9  2021.2   146.9 2019.72
     163 2019.39   179.1 2016.58   191.1  2018.8  198.132016.364   212.5 2014.64
   219.3 2014.88  225.392016.365   235.3 2018.98   239.4 2021.12   247.4 2026.63
   255.4 2030.95   288.2 2043.86   311.9  2055.3   320.5 2058.52   328.9 2063.31
   345.8 2070.25   362.8 2076.47   369.6 2079.41   402.1  2095.4   422.9 2103.48
#Mann= 3 ,-1 , 0
       0      .1       0  198.13    .045       0  225.39      .1       0
#XS Ineff= 2 , 0
          153.85 2021.03
Permanent Ineff=
       F       F
Bank Sta=198.13,225.39
XS Rating Curve= 0 ,0
Exp/Cntr(USF)=0,0
Exp/Cntr=0.3,0.1

Type RM Length L Ch R = 1 ,10783   ,171,174.6,180.9
XS GIS Cut Line= 4
2442291.13766068620590.2514894052442308.47455757 620515.12493622
2442351.81679979620282.5215696282442364.81947246 620181.38967111
#Sta/Elev= 30
       0 2067.31   17.632062.095    32.2 2057.03    59.2 2048.65    72.5 2043.58
    85.5 2037.47    96.4 2029.27   101.8 2026.22   110.1 2022.73   122.1 2018.47
   134.3 2015.64   142.4 2014.51   158.7 2014.73   179.1 2013.59   187.2  2014.1
   191.3 2013.76  196.912011.438   199.4 2010.15   203.5 2009.49     213 2010.28
  218.062011.438   223.8 2014.12   227.9 2017.16   240.4 2029.63   247.3 2034.62
   276.7 2049.98  308.022068.945   321.4 2076.13   357.7 2097.14   415.7 2133.67
#Mann= 5 ,-1 , 0
       0      .1       0   17.63      .1       0  196.91    .045       0
  218.06      .1       0  308.02      .1       0
Bank Sta=196.91,218.06
XS Rating Curve= 0 ,0
Exp/Cntr(USF)=0,0
Exp/Cntr=0.3,0.1

Type RM Length L Ch R = 1 ,10608   ,203.6,207.5,212.4
XS GIS Cut Line= 4
2442367.70895528620619.1463175532442409.60645609620565.690885479
 2442529.5199929620411.1035548872442624.87292579620330.198036073
#Sta/Elev= 30
       0 2061.41    24.4 2050.16   49.35 2037.73   82.89 2022.54    90.7 2019.34
    96.8 2017.89     117 2010.37   122.1 2009.75   130.6 2010.57   137.3 2010.48
     142 2009.66  147.052007.283   152.5 2005.48   157.5 2004.95   162.6 2005.44
  168.082007.283   172.7 2008.54  185.042008.704   190.1 2009.06   196.2 2010.58
   204.7 2014.79  224.922022.879   238.5 2029.93   247.5 2033.92   275.7 2048.43
   294.8 2059.55   332.7  2079.5     344 2086.82   355.4 2091.16   388.6 2109.19
#Mann= 7 ,-1 , 0
       0      .1       0   49.35      .1       0   82.89      .1       0
  147.05    .045       0  168.08      .1       0  185.04      .1       0
  224.92      .1       0
#XS Ineff= 2 , 0
          134.06 2017.14
Permanent Ineff=
       F       F
Bank Sta=147.05,168.08
XS Rating Curve= 0 ,0
Exp/Cntr(USF)=0,0
Exp/Cntr=0.3,0.1

Type RM Length L Ch R = 1 ,10401   ,143.9,141.3,140.4
XS GIS Cut Line= 4
 2442470.2855952620707.2755434052442517.96206165620672.601749627
2442655.21249535620610.477869109 2442763.5681009 620559.91191985
#Sta/Elev= 30
       0 2040.16     6.3 2036.26    14.3 2032.43    25.3 2026.14    40.1 2020.24
    57.9 2015.25    72.9 2011.88    91.1 2009.77   108.1 2003.23   112.5 2003.19
   130.1 2005.11   134.5 2005.08   143.2 2002.79   163.6 2004.24   169.4 2003.89
   175.7 2002.55   181.7  2002.2   184.8 2002.69  187.982004.044  189.832005.654
   204.7 2020.72   208.9 2023.98   217.9  2029.3     227  2033.4   262.1 2056.04
   278.2 2067.33   284.3 2072.45   296.2 2079.09     315 2091.76   329.2 2099.25
#Mann= 4 ,-1 , 0
       0      .1       0   169.4    .045       0  187.98      .1       0
  189.83      .1       0
Bank Sta=169.4,187.98
XS Rating Curve= 0 ,0
Exp/Cntr(USF)=0,0
Exp/Cntr=0.3,0.1

Type RM Length L Ch R = 1 ,10259   ,170,170.5,170.5
XS GIS Cut Line= 4
2442512.18309602620818.520631775 2442607.5360289 620782.40209659
2442759.23387668620710.1650262192442818.46827439620692.828129331
#Sta/Elev= 30
       0 2056.17      11 2048.88    17.2 2046.22    32.7 2036.64    49.8 2027.58
    58.3 2023.64    66.9 2021.05    75.5 2017.88    88.6 2014.16    92.6 2013.15
   101.1 2011.83     110 2008.96     119 2007.47   127.7 2004.48   136.5 2000.87
  138.832000.405     146 1999.54     173 1998.96   176.4 1999.07  179.232000.406
   180.8 2001.27     191 2009.67   211.8 2025.56   260.6 2055.59   273.6  2063.9
   285.1 2069.96   291.6  2073.8   302.8 2081.36   311.2 2086.48   331.7 2101.74
#Mann= 3 ,-1 , 0
       0      .1       0  138.83    .045       0  179.23      .1       0
Bank Sta=138.83,179.23
XS Rating Curve= 0 ,0
Exp/Cntr(USF)=0,0
Exp/Cntr=0.3,0.1

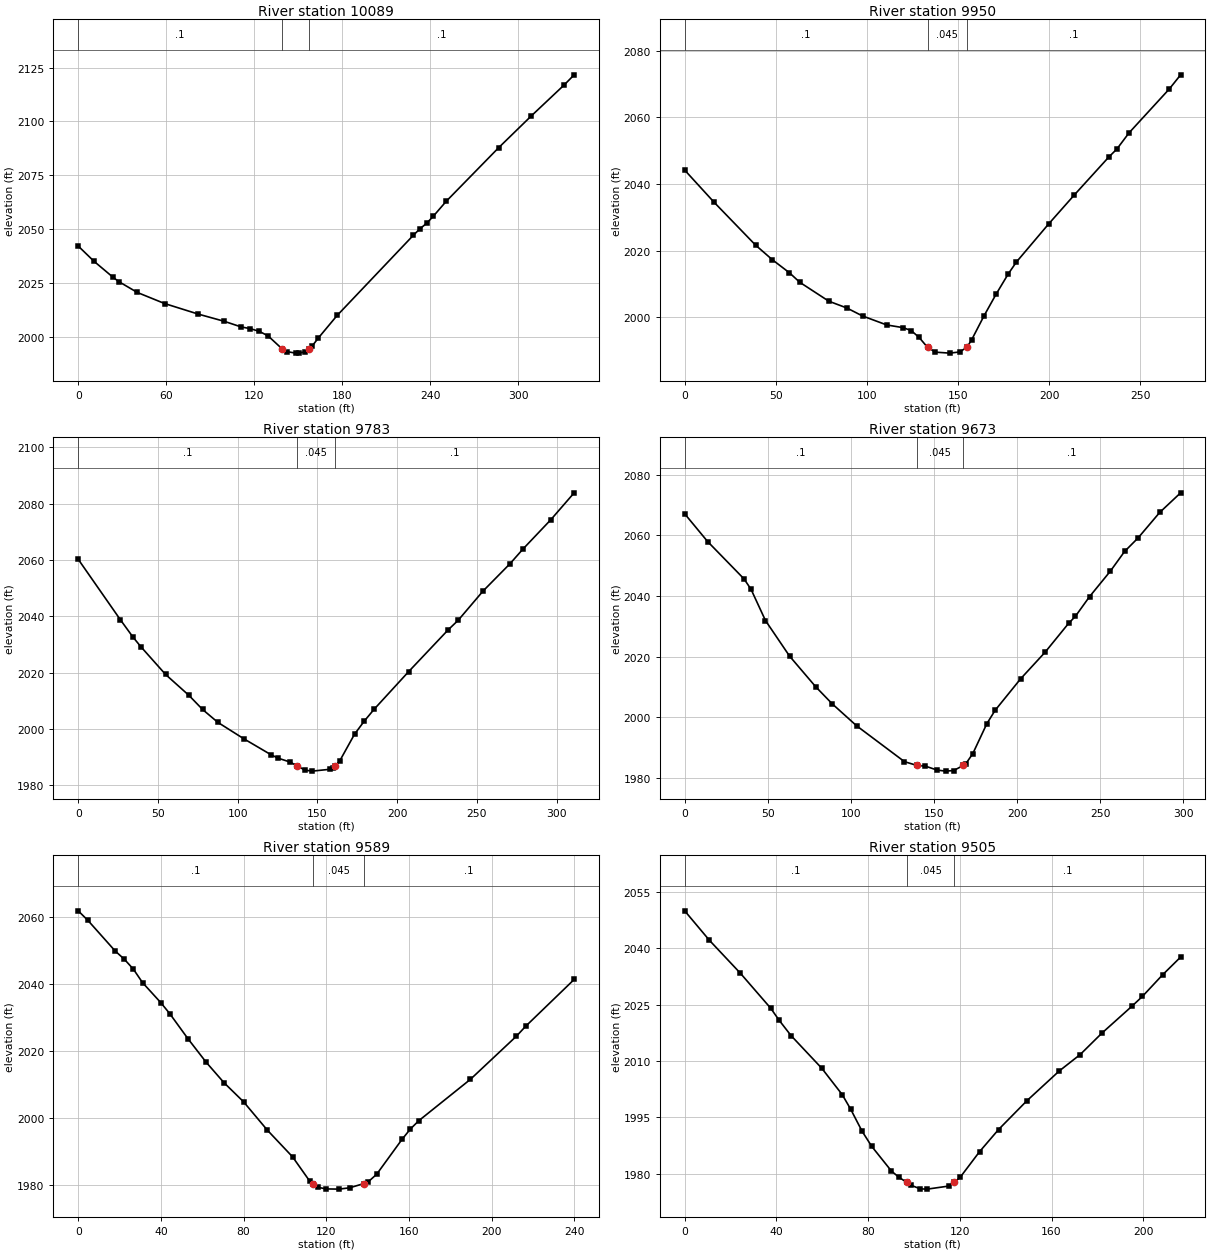
Type RM Length L Ch R = 1 ,10089   ,139.1,139,138
XS GIS Cut Line= 4
2442604.64654609620949.9920998482442705.77844461620915.318306071
2442806.91034313620876.3102880712442916.71069009 620821.41011459
#Sta/Elev= 30
       0 2042.21    10.7 2035.18    23.4 2027.92    27.6 2025.74    40.3 2020.68
    58.9 2015.54      82 2010.61    99.5 2007.31   111.1 2004.69   117.3  2003.9
   123.5 2002.62   129.4 2000.56  139.011994.516   142.2 1993.26   148.2 1992.54
   150.8 1992.57   154.4 1993.13  157.381994.514   159.4 1995.75   163.7 1999.56
   176.5    2010   228.5 2047.23     233 2050.23   237.5 2052.75     242 2055.98
   250.9 2062.98   286.7 2087.88     309 2102.64   331.4    2117   338.1 2121.63
#Mann= 3 ,-1 , 0
       0      .1       0  139.01    .045       0  157.38      .1       0
Bank Sta=139.01,157.38
XS Rating Curve= 0 ,0
Exp/Cntr(USF)=0,0
Exp/Cntr=0.3,0.1

Type RM Length L Ch R = 1 ,9950    ,166.2,167.3,168.1
XS GIS Cut Line= 4
2442679.77309927621074.2398608852442769.34706653621039.566067107
2442864.69999942 620993.334342072442923.93439713620955.771065478
#Sta/Elev= 30
       0 2044.19    16.1 2034.57    38.9 2021.69    48.2 2017.27    57.5 2013.39
    63.2 2010.53    79.1 2004.87      89 2002.83    97.6 2000.44   110.9 1997.74
   119.8 1996.94   124.3 1996.07   128.7 1993.98  133.291991.026   137.6 1989.58
   145.5 1989.29   150.9 1989.64  154.881991.028   157.5 1993.28   164.3 2000.48
   170.9 2006.95   177.6 2013.06   182.1 2016.64   199.8 2028.06   213.9 2036.76
   232.9 2048.18   237.2  2050.5   243.9 2055.37     266 2068.53   272.2 2072.77
#Mann= 3 ,-1 , 0
       0      .1       0  133.29    .045       0  154.88      .1       0
Bank Sta=133.29,154.88
XS Rating Curve= 0 ,0
Exp/Cntr(USF)=0,0
Exp/Cntr=0.3,0.1

Type RM Length L Ch R = 1 ,9783    ,106.9,110,110.7
XS GIS Cut Line= 4
2442746.23120401621223.0482258472442808.35508453621198.487621922
2442955.71870809621140.697965625 2443036.6242269621111.803137477
#Sta/Elev= 30
       0 2060.21    26.4 2038.77    34.4 2032.54    39.3 2029.16    54.8 2019.31
    69.4 2011.91      78 2006.88    87.6  2002.3   103.7 1996.54   120.9 1990.82
   125.2 1989.63   133.1 1988.18  137.311986.786   142.4 1985.34   146.7    1985
   157.8 1985.65   159.6 1985.95  161.181986.784   163.9 1988.53   173.3 1998.13
   179.4 2002.77   185.6 2006.99   207.2 2020.32     232 2035.16   238.3 2038.57
   253.9 2048.95   270.8 2058.65   278.9 2063.84   296.3 2074.21     311  2083.8
#Mann= 3 ,-1 , 0
       0      .1       0  137.31    .045       0  161.18      .1       0
Bank Sta=137.31,161.18
XS Rating Curve= 0 ,0
Exp/Cntr(USF)=0,0
Exp/Cntr=0.3,0.1

Type RM Length L Ch R = 1 ,9673    ,82.1,83.5,83.6
XS GIS Cut Line= 4
2442778.01551498621316.9564173292442845.91836113621288.061589181
2443003.39517453621250.4983125882443062.62957224621230.271932884
#Sta/Elev= 30
       0 2067.11    13.8 2057.96    35.7 2045.64    39.9 2042.23    48.6 2031.91
    63.1 2020.18    78.7 2010.15    88.7 2004.48   103.4 1997.22   132.2 1985.39
   139.8 1984.13   144.6 1983.95   151.8 1982.62   156.9 1982.27   161.8 1982.46
   167.5 1984.13   169.2 1984.78   173.3 1988.04   181.7 1997.86   186.7  2002.3
   202.1 2012.73   216.8 2021.48   230.9 2030.97     235  2033.3   243.5 2039.78
   256.1 2048.24   264.6 2054.69   272.7 2059.14   285.7 2067.54   298.3 2074.02
#Mann= 3 ,-1 , 0
       0      .1       0   139.8    .045       0   167.5      .1       0
Bank Sta=139.8,167.5
XS Rating Curve= 0 ,0
Exp/Cntr(USF)=0,0
Exp/Cntr=0.3,0.1

Type RM Length L Ch R = 1 ,9589    ,86.2,83.9,82.3
XS GIS Cut Line= 4
2442818.46827438621392.0829705142442887.81586194621360.298659551
2442993.28198468621340.0722798472443043.84793394621315.511675921
#Sta/Elev= 30
       0 2061.93     4.7 2059.06    17.9  2049.9    22.3 2047.45    26.7 2044.47
    31.1 2040.46    39.9 2034.49    44.3 2031.15    53.1 2023.65    61.9 2016.62
    70.5 2010.52      80 2004.78    91.5  1996.3   103.7 1988.31   111.9 1981.13
  113.54 1980.34   115.9 1979.21     120 1978.72   126.2 1978.66   131.3 1979.06
  138.311980.343   140.4 1980.91   144.4 1983.13   156.7  1993.6   160.7 1996.66
   164.8 1999.16   189.7  2011.5     212 2024.44   216.4 2027.36   239.9 2041.39
#Mann= 3 ,-1 , 0
       0      .1       0  113.54    .045       0  138.31      .1       0
Bank Sta=113.54,138.31
XS Rating Curve= 0 ,0
Exp/Cntr(USF)=0,0
Exp/Cntr=0.3,0.1

Type RM Length L Ch R = 1 ,9505    ,98.3,97.3,96
XS GIS Cut Line= 4
2442869.03422364621472.9884893282442934.04758698621441.204178365
2443007.72939875621413.7540916252443065.51905505621383.414522069
#Sta/Elev= 30
       0 2049.98    10.8 2042.12    24.2 2033.42    37.5 2024.05    41.2 2020.83
    46.4 2016.74    59.8 2008.04    68.7 2001.03    72.4 1997.14    77.4 1991.24
    81.6 1987.22    90.2 1980.65    93.4 1979.03   96.851977.657    98.7  1976.9
   102.7 1975.92   105.8 1975.85   115.1 1976.66  117.531977.659   120.1 1978.96
   128.6 1985.82   136.9 1991.73   149.3 1999.42   163.4 2007.34   172.5  2011.7
     182 2017.42   195.1 2024.59   199.6 2027.16   208.4 2032.91   216.3 2037.66
#Mann= 3 ,-1 , 0
       0      .1       0   96.85    .045       0  117.53      .1       0
Bank Sta=96.85,117.53
XS Rating Curve= 0 ,0
Exp/Cntr(USF)=0,0
Exp/Cntr=0.3,0.1

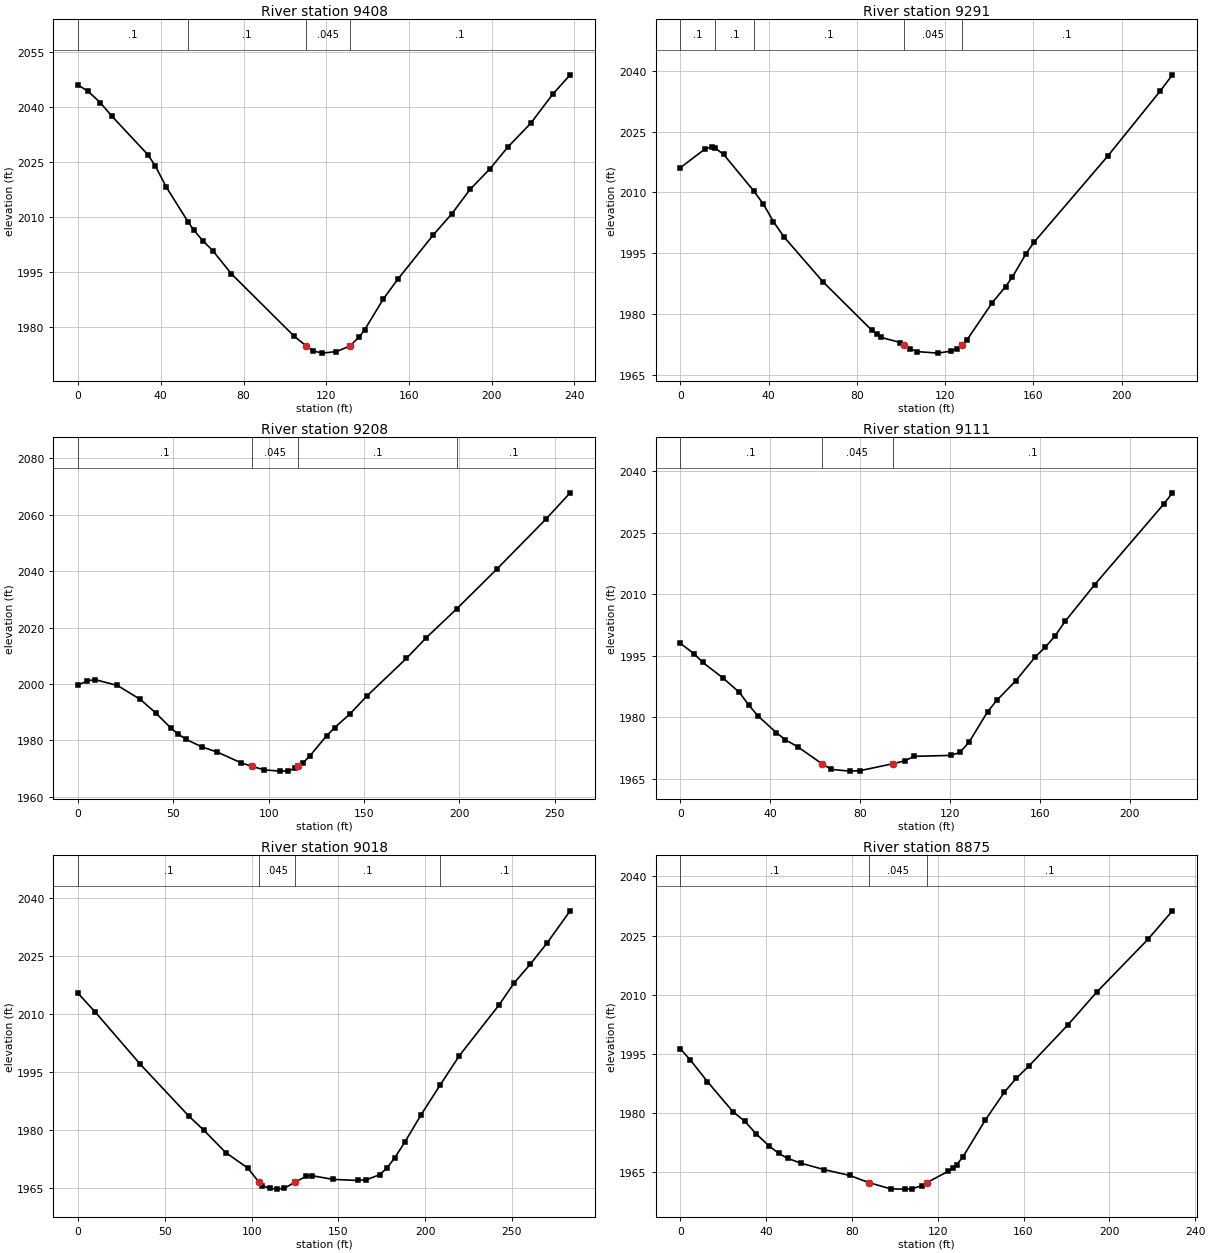
Type RM Length L Ch R = 1 ,9408    ,115.8,116.6,117.1
XS GIS Cut Line= 4
2442908.04224164621562.5624565872442986.05827764621526.443921402
2443081.41121053621478.7674549582443117.52974572621451.317368217
#Sta/Elev= 30
       0 2045.94     4.8 2044.28    10.8 2041.13    16.2 2037.55    33.8 2026.92
    37.3 2023.93    42.6 2018.16   53.122008.664    55.9 2006.41    60.3 2003.45
    65.1 2000.77    74.1 1994.43   104.6 1977.32   110.41974.674   113.6 1973.39
     118 1972.76   124.9 1973.18  131.341974.677   135.9 1977.14   138.6 1979.17
   147.6 1987.56   154.7 1993.01   171.7 2005.01   180.7 2010.79   189.6 2017.52
   199.2 2023.11   207.7 2028.97   218.8 2035.48   229.4 2043.38   237.9 2048.74
#Mann= 4 ,-1 , 0
       0      .1       0   53.12      .1       0   110.4    .045       0
  131.34      .1       0
Bank Sta=110.4,131.34
XS Rating Curve= 0 ,0
Exp/Cntr(USF)=0,0
Exp/Cntr=0.3,0.1

Type RM Length L Ch R = 1 ,9291    ,80.6,83,84.7
XS GIS Cut Line= 4
2442961.49767372621665.1390965132443023.62155424621631.910044142
2443105.97181446621598.6809917722443159.42724653621564.007197995
#Sta/Elev= 30
       0 2016.09    11.4 2020.79    14.4 2021.22   15.662020.958    19.6  2019.4
   33.34 2010.35    37.7 2007.09    42.2 2002.83    46.9 1999.12    64.6 1988.04
    86.8 1976.08      89 1975.13    91.1 1974.31    99.7 1973.07  101.491972.487
     104 1971.53   107.4 1970.83   116.7 1970.46   122.8 1970.97   125.6 1971.54
  127.511972.484   129.9 1973.71   141.2 1982.76   147.4 1986.85   150.5 1989.22
   156.6 1994.87   160.2  1997.7   193.6  2018.9   217.4 2034.93     223 2038.96
#Mann= 5 ,-1 , 0
       0      .1       0   15.66      .1       0   33.34      .1       0
  101.49    .045       0  127.51      .1       0
Bank Sta=101.49,127.51
XS Rating Curve= 0 ,0
Exp/Cntr(USF)=0,0
Exp/Cntr=0.3,0.1

Type RM Length L Ch R = 1 ,9208    ,97.4,97.7,96.9
XS GIS Cut Line= 4
2442986.05827764621702.7023731052443045.29267535621704.147114513
 2443133.4219012621683.9207348092443230.21957549621634.799526957
#Sta/Elev= 30
       0 1999.63     4.7 2001.02     8.7 2001.58    20.7 1999.48    32.7 1994.51
    40.7 1989.79    48.7 1984.41    52.7 1982.18    56.7  1980.4    64.8 1977.75
    73.1 1975.87    85.4 1972.12   91.151970.826    97.7 1969.57   105.9 1969.13
     110 1969.18   114.1  1970.1  115.571970.825   118.2 1972.14   121.6 1974.48
   130.5 1981.73   134.6  1984.5   142.8 1989.48   151.4 1995.64   172.3 2009.07
   182.6 2016.33  198.732026.644   219.9 2040.81   245.4 2058.35   258.2 2067.72
#Mann= 4 ,-1 , 0
       0      .1       0   91.15    .045       0  115.57      .1       0
  198.73      .1       0
Bank Sta=91.15,115.57
XS Rating Curve= 0 ,0
Exp/Cntr(USF)=0,0
Exp/Cntr=0.3,0.1

Type RM Length L Ch R = 1 ,9111    ,93.6,92.6,91.4
XS GIS Cut Line= 4
2443020.73207142621805.2790130312443038.06896831621803.834271623
2443163.76147075621776.3841848832443230.21957549621746.044615327
#Sta/Elev= 30
       0 1998.01       6 1995.52      10 1993.33    18.8 1989.64    26.3 1986.03
    30.4 1982.99    34.5 1980.32    42.7 1976.22    46.7 1974.49    52.4  1972.7
   63.091968.594    67.2 1967.23    75.4  1966.8    79.9  1966.9   94.511968.592
     100 1969.32   104.1 1970.41   120.4 1970.64   124.5 1971.36   128.6 1973.91
   136.8 1981.29   140.9 1984.08   149.3 1988.82   158.1 1994.73   162.5 1997.07
   166.9 1999.85   171.3 2003.35   184.5 2012.34   215.3 2032.03   219.1 2034.75
#Mann= 3 ,-1 , 0
       0      .1       0   63.09    .045       0   94.51      .1       0
Bank Sta=63.09,94.51
XS Rating Curve= 0 ,0
Exp/Cntr(USF)=0,0
Exp/Cntr=0.3,0.1

Type RM Length L Ch R = 1 ,9018    ,149.4,142.9,135.3
XS GIS Cut Line= 4
2443009.17414016621913.6346185862443069.85327927621896.297721697
2443217.21690283621847.1765138452443269.22759349621808.168495846
#Sta/Elev= 30
       0 2015.24      10 2010.34    35.8 1996.91      64  1983.4    72.5 1979.82
    85.1 1974.03    97.8 1970.05  104.161966.429   106.2 1965.49   110.4 1964.81
   114.6 1964.59   118.9 1964.85  125.25 1966.43   131.3  1967.9   134.5 1968.08
   147.1  1967.1     161 1966.84   166.1    1967   173.7 1968.31   177.9    1970
   182.5 1972.73   188.3 1976.77   197.7 1983.88  208.471991.407   219.7 1999.12
   242.6 2012.25   251.2 2017.89   260.4 2022.68   270.4 2028.36   283.5 2036.56
#Mann= 4 ,-1 , 0
       0      .1       0  104.16    .045       0  125.25      .1       0
  208.47      .1       0
Bank Sta=104.16,125.25
XS Rating Curve= 0 ,0
Exp/Cntr(USF)=0,0
Exp/Cntr=0.3,0.1

Type RM Length L Ch R = 1 ,8875    ,128.1,127.9,126.8
XS GIS Cut Line= 4
2443156.53776372 622039.327121032443198.43526453622001.763844438
2443264.89336927621902.0766873272443293.78819742621857.289703697
#Sta/Elev= 30
       0 1996.29     4.7 1993.43    12.6 1987.99    24.5 1980.35    30.2 1977.85
    35.2 1974.79    41.5 1971.59    45.9 1969.75      50  1968.5    56.3 1967.26
    67.2 1965.62      79 1964.16   87.741962.367    98.2 1960.74   104.7 1960.69
   107.8 1960.76   112.6 1961.54  115.031962.366   124.9 1965.22     127 1965.95
   128.9 1966.93   131.8 1968.92   142.2 1978.23   151.1 1985.31   156.6  1988.8
   162.4 1991.86   180.6 2002.31   194.2 2010.72     218 2024.06   229.4 2031.29
#Mann= 3 ,-1 , 0
       0      .1       0   87.74    .045       0  115.03      .1       0
Bank Sta=87.74,115.03
XS Rating Curve= 0 ,0
Exp/Cntr(USF)=0,0
Exp/Cntr=0.3,0.1