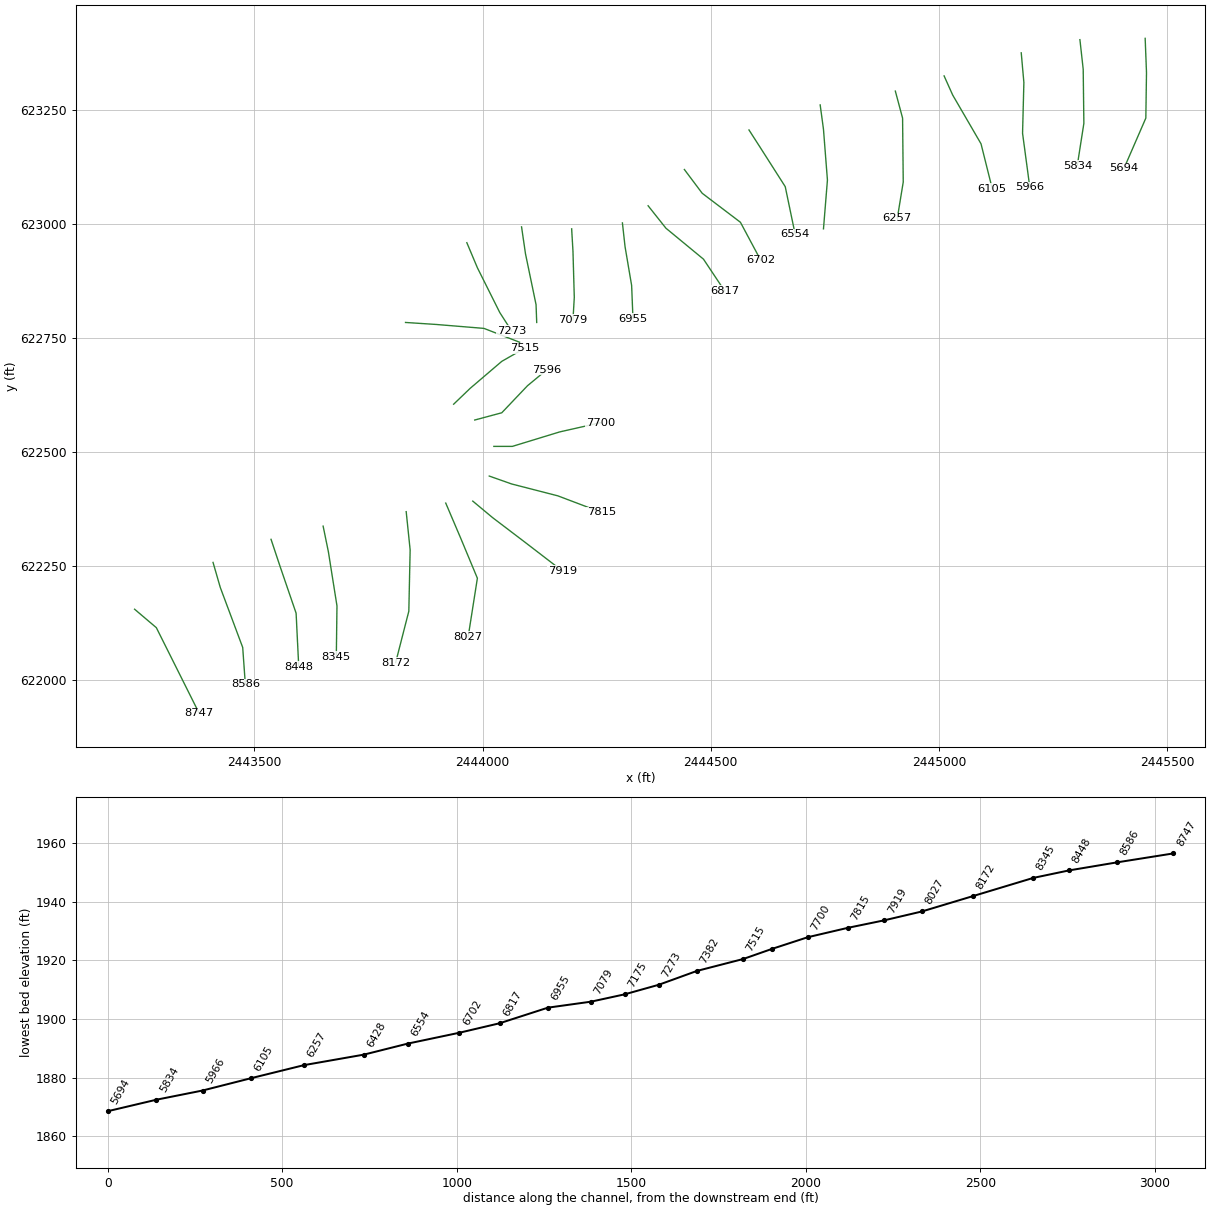
HEC-RAS study PETERSRN.prj: PETERSRN

--- PETERSRN.g01 (geometry) --- (continued)

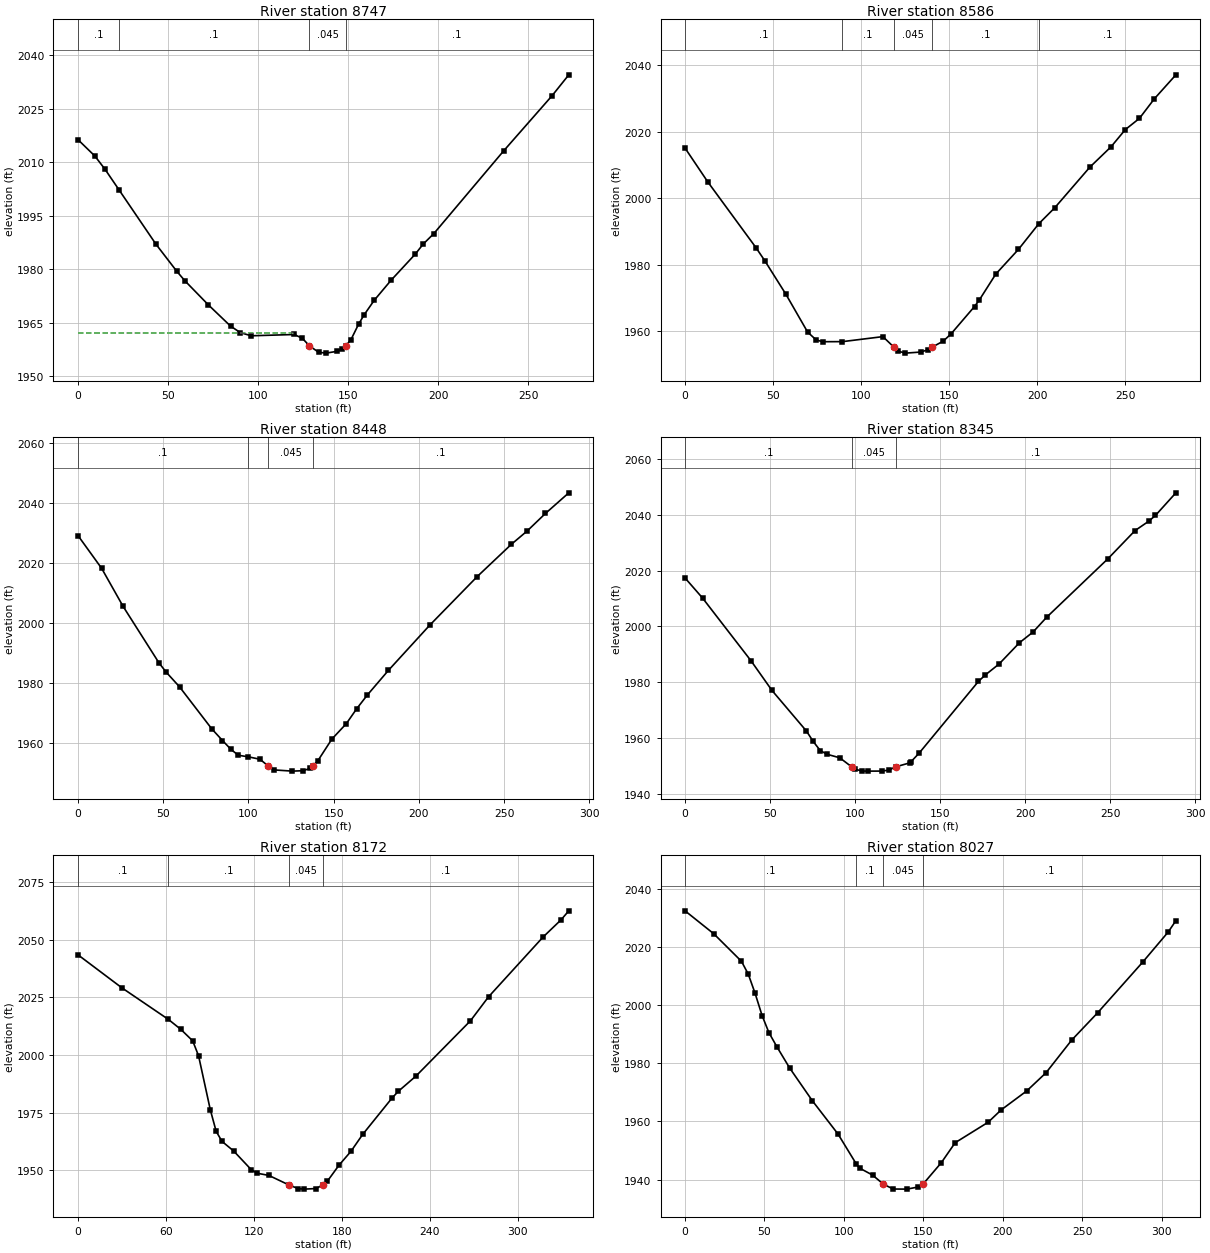
Type RM Length L Ch R = 1 ,8747    ,161.5,161.4,159.1
XS GIS Cut Line= 4
2443237.44328253622154.9064336222443285.11974898622114.453674215
 2443348.6883709621987.3164303632443379.02794046621926.637291253
#Sta/Elev= 30
       0 2016.31     9.4 2011.71    15.1 2007.95    22.7 2002.31    43.3 1987.01
    54.9  1979.4    59.4 1976.74    72.4 1970.01    84.7 1964.07    90.2 1962.22
    96.2 1961.35   120.1 1961.71   124.6 1960.63  128.541958.515   133.6 1956.74
   137.7 1956.49   143.9    1957   146.7 1957.64   148.61958.517   151.5  1960.2
   155.8  1964.6   158.8 1967.17   164.5 1971.31   173.8 1976.89   187.3 1984.25
   191.6 1987.01   197.6    1990   236.3 2013.14   263.2 2028.61   272.5 2034.47
#Mann= 4 ,-1 , 0
       0      .1       0    22.7      .1       0  128.54    .045       0
   148.6      .1       0
#XS Ineff= 2 , 0
          119.22 1962.01
Permanent Ineff=
       F       F
Bank Sta=128.54,148.6
XS Rating Curve= 0 ,0
Exp/Cntr(USF)=0,0
Exp/Cntr=0.3,0.1

Type RM Length L Ch R = 1 ,8586    ,138.5,138.2,137.5
XS GIS Cut Line= 4
2443409.36751001622257.4830735482443425.25966549622202.582900066
2443474.38087335622071.1114319932443480.15983898621990.205913178
#Sta/Elev= 30
       0 2015.06    12.9  2004.9    40.2 1985.18    45.2 1981.26    57.2 1971.17
    69.6 1959.75    74.5 1957.38    78.2 1956.87   89.371956.895   112.3  1958.4
  118.45 1955.29   120.9 1954.03   125.1 1953.44   133.7 1953.76     138 1954.46
  140.421955.291   146.5 1957.03   150.8 1959.11   164.3 1967.45   166.9  1969.3
   176.4 1977.21   189.2 1984.59  200.841992.349   209.8 1997.09   229.8 2009.34
   241.8 2015.45   249.9 2020.61   257.9 2023.98   266.4 2029.88   278.6 2037.07
#Mann= 5 ,-1 , 0
       0      .1       0   89.37      .1       0  118.45    .045       0
  140.42      .1       0  200.84      .1       0
Bank Sta=118.45,140.42
XS Rating Curve= 0 ,0
Exp/Cntr(USF)=0,0
Exp/Cntr=0.3,0.1

Type RM Length L Ch R = 1 ,8448    ,104.5,102.1,100.3
XS GIS Cut Line= 4
2443536.50475386622308.0490228072443556.73113357622247.369883696
2443591.40492735622146.2379851782443597.18389298622029.213931178
#Sta/Elev= 30
       0 2029.26    13.9 2018.31    26.5 2005.61    47.6 1986.73    51.8 1983.67
    59.6 1978.79    78.5 1964.79    84.8 1960.89    89.8 1957.92    94.1 1955.97
  100.051955.442   106.8 1954.64  111.761952.327   115.2 1951.08   125.8 1950.68
   132.1 1950.82   136.4 1951.63  137.641952.328   140.6    1954     149 1961.37
   157.5 1966.54   163.5 1971.45   169.8 1976.07   182.2 1984.31   206.3 1999.29
   234.3 2015.59   254.3 2026.33   263.6 2030.79   274.3 2036.62     288  2043.5
#Mann= 4 ,-1 , 0
       0      .1       0  100.05      .1       0  111.76    .045       0
  137.64      .1       0
Bank Sta=111.76,137.64
XS Rating Curve= 0 ,0
Exp/Cntr(USF)=0,0
Exp/Cntr=0.3,0.1

Type RM Length L Ch R = 1 ,8345    ,175.4,173.8,171.6
XS GIS Cut Line= 4
2443650.63932505622336.9438509552443662.19725631622280.598936066
 2443680.9788946622162.130140659 2443679.5341532622050.885052289
#Sta/Elev= 30
       0 2017.34    10.3 2010.15    38.8 1987.67    51.1 1977.07    71.4 1962.49
    75.4 1958.75    79.5 1955.52    83.5 1954.17      91 1952.91   98.021949.657
    99.7 1948.91   103.8 1948.18   107.8 1948.13   115.9 1948.15     120 1948.52
  123.861949.658   132.1 1951.08   132.9 1951.49   137.7 1954.59   172.6 1980.31
   176.7 1982.63   184.7 1986.51   196.7 1994.14   204.7 1997.98   212.7 2003.27
   248.7 2024.21   264.7 2034.33   272.7 2037.66   276.7 2039.76   288.7 2047.85
#Mann= 3 ,-1 , 0
       0      .1       0   98.02    .045       0  123.86      .1       0
Bank Sta=98.02,123.86
XS Rating Curve= 0 ,0
Exp/Cntr(USF)=0,0
Exp/Cntr=0.3,0.1

Type RM Length L Ch R = 1 ,8172    ,137.5,145.1,147.6
XS GIS Cut Line= 4
2443832.67674238622368.7281619182443841.34519083622284.933160288
2443838.45570801  622150.57220942443809.56087986622037.882379623
#Sta/Elev= 30
       0 2043.41      30 2029.09   61.772015.391    70.2 2011.11    78.3 2006.14
    82.3 1999.69    90.3 1976.35    94.3 1966.96    98.3 1962.58   106.3 1958.39
   118.3  1950.3   122.3 1948.78   130.3 1947.83  143.951943.708   150.3 1942.12
   154.3 1941.89   162.3 1942.13  167.391943.707   170.3  1945.4   178.3 1952.37
   186.3 1958.24   194.3 1965.57   214.3 1981.31   218.6 1984.24   230.7 1990.88
   267.9 2014.83   280.2 2025.19   317.4 2051.08   329.7 2058.55     335 2062.46
#Mann= 4 ,-1 , 0
       0      .1       0   61.77      .1       0  143.95    .045       0
  167.39      .1       0
Bank Sta=143.95,167.39
XS Rating Curve= 0 ,0
Exp/Cntr(USF)=0,0
Exp/Cntr=0.3,0.1

Type RM Length L Ch R = 1 ,8027    ,101.8,107.9,114.7
XS GIS Cut Line= 4
2443919.36122683622387.509800214 2443952.5902792622309.493764214
2443988.70881438 622222.809279772443968.48243468622094.227294511
#Sta/Elev= 30
       0 2032.48    18.1 2024.57    35.5 2015.11    39.8 2010.68    44.1 2004.06
    48.5 1996.41    52.8 1990.54    57.9 1985.59    65.9 1978.33    80.1 1967.12
    96.3 1955.63  107.791945.333   109.8 1943.94     118 1941.53  124.851938.377
     131 1936.73   139.6 1936.69   146.6 1937.41  149.731938.377   161.3  1945.8
     170 1952.67   190.8 1959.73   198.9 1963.94   215.1 1970.52   227.2 1976.76
   243.3 1987.97   259.6 1997.35     288 2014.81   304.1 2025.22   308.9 2029.09
#Mann= 4 ,-1 , 0
       0      .1       0  107.79      .1       0  124.85    .045       0
  149.73      .1       0
Bank Sta=124.85,149.73
XS Rating Curve= 0 ,0
Exp/Cntr(USF)=0,0
Exp/Cntr=0.3,0.1

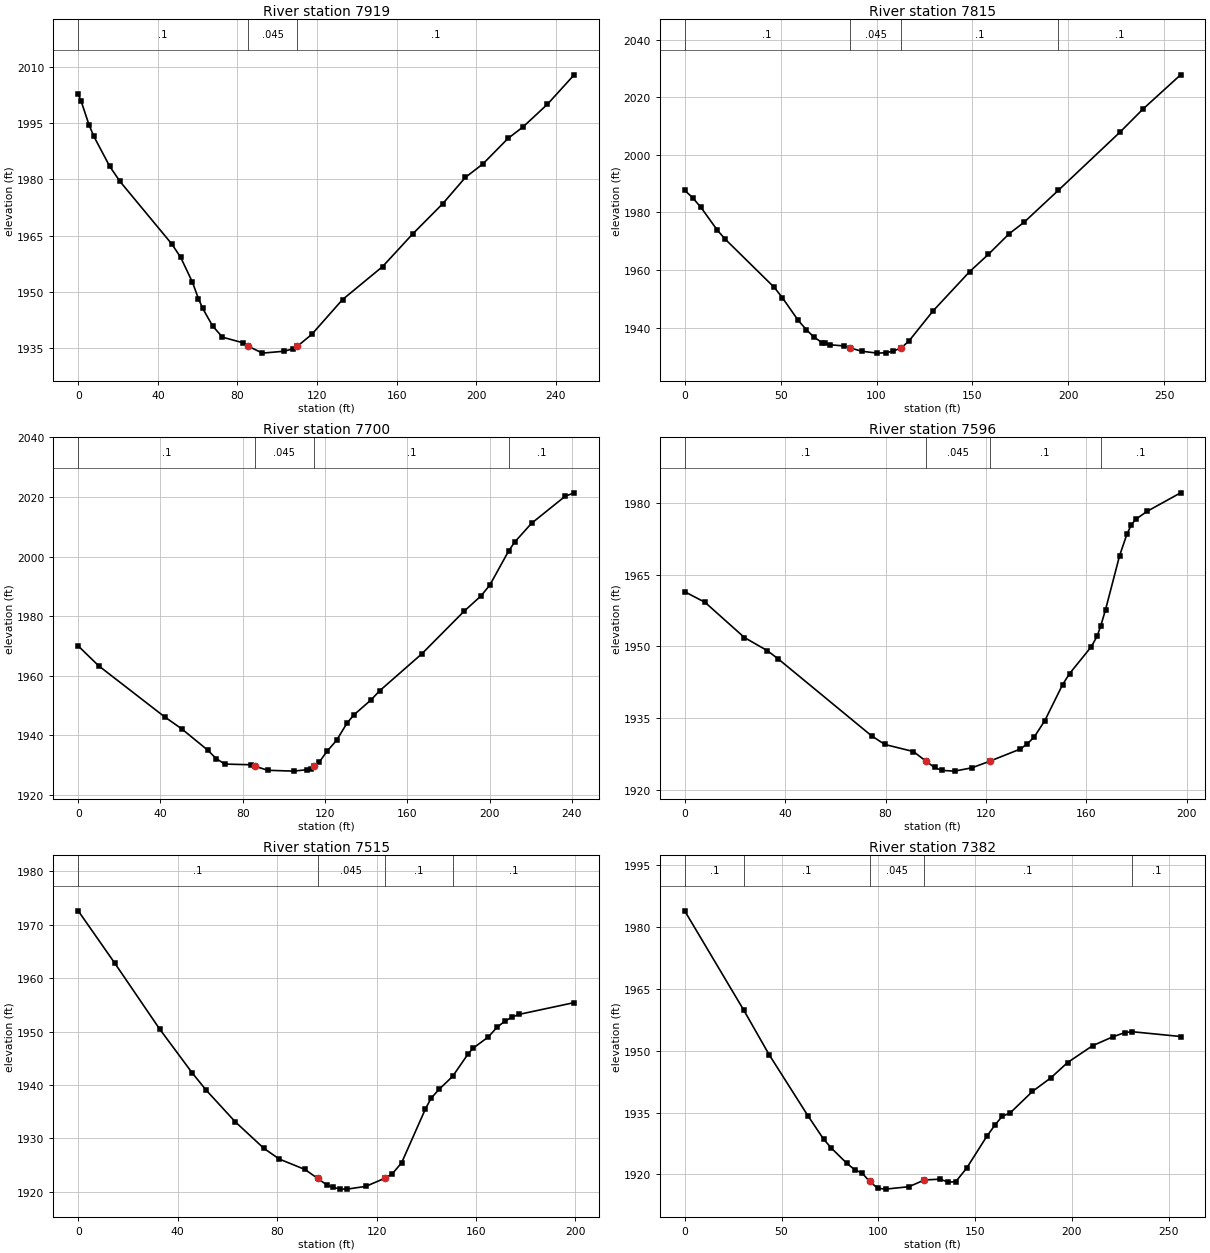
Type RM Length L Ch R = 1 ,7919    ,97.9,103.9,108.6
XS GIS Cut Line= 4
2443978.59562453622391.8440244362444021.93786675622355.725489251
2444094.17493712 622300.825315772444175.08045594622238.701435252
#Sta/Elev= 30
       0  2002.8     1.5 2000.84     5.4 1994.63     7.7 1991.66    15.8 1983.53
      21 1979.47    47.1 1962.73    51.5 1959.21    57.4 1952.58    60.4 1948.21
    62.5 1945.66    67.5 1940.93    72.5 1937.92    82.6 1936.46   85.311935.533
    92.6 1933.67   103.3 1934.17   107.7 1934.76  110.171935.532   117.3 1938.64
   132.8 1947.95   152.9 1956.74     168 1965.43   183.2 1973.56   194.6 1980.58
   203.3 1984.12     216 1990.97   223.5 1994.01   235.7 2000.03   249.2 2007.92
#Mann= 3 ,-1 , 0
       0      .1       0   85.31    .045       0  110.17      .1       0
Bank Sta=85.31,110.17
XS Rating Curve= 0 ,0
Exp/Cntr(USF)=0,0
Exp/Cntr=0.3,0.1

Type RM Length L Ch R = 1 ,7815    ,104.9,115.2,120.6
XS GIS Cut Line= 4
2444014.71415971622446.7441979182444063.83536757622429.407301029
2444164.96726608622403.4019556952444260.32019897 622367.28342051
#Sta/Elev= 30
       0 1987.67     4.3 1984.97     8.5  1981.7      17 1973.82    21.2 1970.64
    46.7 1953.94    50.9 1950.38    59.2 1942.46    63.4 1939.27    67.5 1936.59
    71.6 1934.81      73 1934.52    75.7 1934.02    82.8 1933.63   85.941932.982
    92.3 1931.77   100.5 1931.12   104.7 1931.24   108.8 1931.83     113 1932.98
     117 1935.41   129.4 1945.73   148.5 1959.39   158.3 1965.42   169.2 1972.62
   176.9 1976.55  194.781987.663   226.9 2007.85   238.9 2015.87   258.5 2027.75
#Mann= 4 ,-1 , 0
       0      .1       0   85.94    .045       0     113      .1       0
  194.78      .1       0
Bank Sta=85.94,113
XS Rating Curve= 0 ,0
Exp/Cntr(USF)=0,0
Exp/Cntr=0.3,0.1

Type RM Length L Ch R = 1 ,7700    ,96.1,103.4,109.8
XS GIS Cut Line= 4
2444024.82734957622511.7575612512444065.28010897622511.757561251
2444169.30149031622543.5418722132444258.87545756622563.768251917
#Sta/Elev= 30
       0 1969.97     9.9 1963.32      42 1946.15    50.3 1942.12    62.9    1935
    67.1  1932.1    71.3 1930.28    83.8 1930.05   85.731929.587    92.2 1928.19
   104.7 1927.91   111.4  1928.4   113.1 1928.71  114.671929.589   117.3 1931.06
     121 1934.61   125.6 1938.25   130.6 1943.96     134  1946.8   142.4 1951.86
   146.5 1954.87   167.1 1967.35   187.6 1981.63   195.8 1986.77   200.1 1990.41
  209.212001.824   212.2 2004.87   220.4 2011.18   236.7 2020.24   241.1 2021.41
#Mann= 4 ,-1 , 0
       0      .1       0   85.73    .045       0  114.67      .1       0
  209.21      .1       0
Bank Sta=85.73,114.67
XS Rating Curve= 0 ,0
Exp/Cntr(USF)=0,0
Exp/Cntr=0.3,0.1

Type RM Length L Ch R = 1 ,7596    ,82.7,81.6,79.9
XS GIS Cut Line= 4
2443982.92984875622569.5472175472444042.16424645622585.439373028
2444098.50916134622644.6737707322444140.40666216622679.347564509
#Sta/Elev= 30
       0 1961.44     8.1 1959.22    23.8 1951.85    32.9 1949.11    37.1 1947.44
    74.4 1931.29    79.7 1929.47    91.1 1927.99   96.141925.951    99.5 1924.66
   102.4 1924.04   107.5 1923.89   114.4 1924.59  121.421925.951   133.5 1928.48
   136.3 1929.52   139.2 1931.03   143.4 1934.44   150.5    1942   153.3 1944.32
   161.9 1949.91   164.2 1952.07  165.681954.268   167.6 1957.68   173.2 1968.99
   176.1 1973.47   177.9 1975.47   179.7 1976.63   184.2 1978.28   197.5 1982.14
#Mann= 4 ,-1 , 0
       0      .1       0   96.14    .045       0  121.42      .1       0
  165.68      .1       0
Bank Sta=96.14,121.42
XS Rating Curve= 0 ,0
Exp/Cntr(USF)=0,0
Exp/Cntr=0.3,0.1

Type RM Length L Ch R = 1 ,7515    ,140.7,132.6,118
XS GIS Cut Line= 4
2443936.69812371622604.221011324 2443972.8166589622638.894805102
2444042.16424645622698.1292028062444092.73019571622727.024030954
#Sta/Elev= 30
       0  1972.6    14.7  1962.8    32.7  1950.5    45.8 1942.28    51.4 1939.05
    63.1 1933.12    74.7 1928.11    80.9 1926.11    91.2 1924.16   96.271922.514
    99.9 1921.29   102.5 1920.82   105.3 1920.51   108.2 1920.48   115.7    1921
  123.321922.513   126.3 1923.32   130.1 1925.42   139.6 1935.42   141.9 1937.47
   145.2 1939.19  150.591941.579   156.9 1945.85   158.9 1946.89     165 1948.99
   168.6 1950.85   171.6 1951.91   174.5  1952.7   177.4 1953.21   199.5 1955.41
#Mann= 4 ,-1 , 0
       0      .1       0   96.27    .045       0  123.32      .1       0
  150.59      .1       0
Bank Sta=96.27,123.32
XS Rating Curve= 0 ,0
Exp/Cntr(USF)=0,0
Exp/Cntr=0.3,0.1

Type RM Length L Ch R = 1 ,7382    ,120.4,109.3,93.5
XS GIS Cut Line= 4
2443831.23200097622783.3689458422443897.69010571 622779.03472162
2444003.15622845622770.3662731762444081.17226445 622740.02670362
#Sta/Elev= 30
       0 1983.97   30.611959.775    43.6 1949.06    63.6 1934.25    71.7 1928.57
    75.7 1926.39    83.7 1922.69    87.7 1921.16    91.7 1920.28   95.48 1918.27
    99.8  1916.6   103.8 1916.41   115.8    1917   123.8 1918.63   131.9 1918.83
   135.9 1918.13   139.9 1918.17   145.6  1921.5     156 1929.22   160.4 1932.09
     164 1934.09     168 1934.87   179.6 1940.13   189.1 1943.43   197.7 1947.13
   210.6 1951.22   221.1 1953.39   227.3 1954.41  231.031954.625   256.1 1953.46
#Mann= 5 ,-1 , 0
       0      .1       0   30.61      .1       0   95.48    .045       0
   123.8      .1       0  231.03      .1       0
Bank Sta=95.48,123.8
XS Rating Curve= 0 ,0
Exp/Cntr(USF)=0,0
Exp/Cntr=0.3,0.1

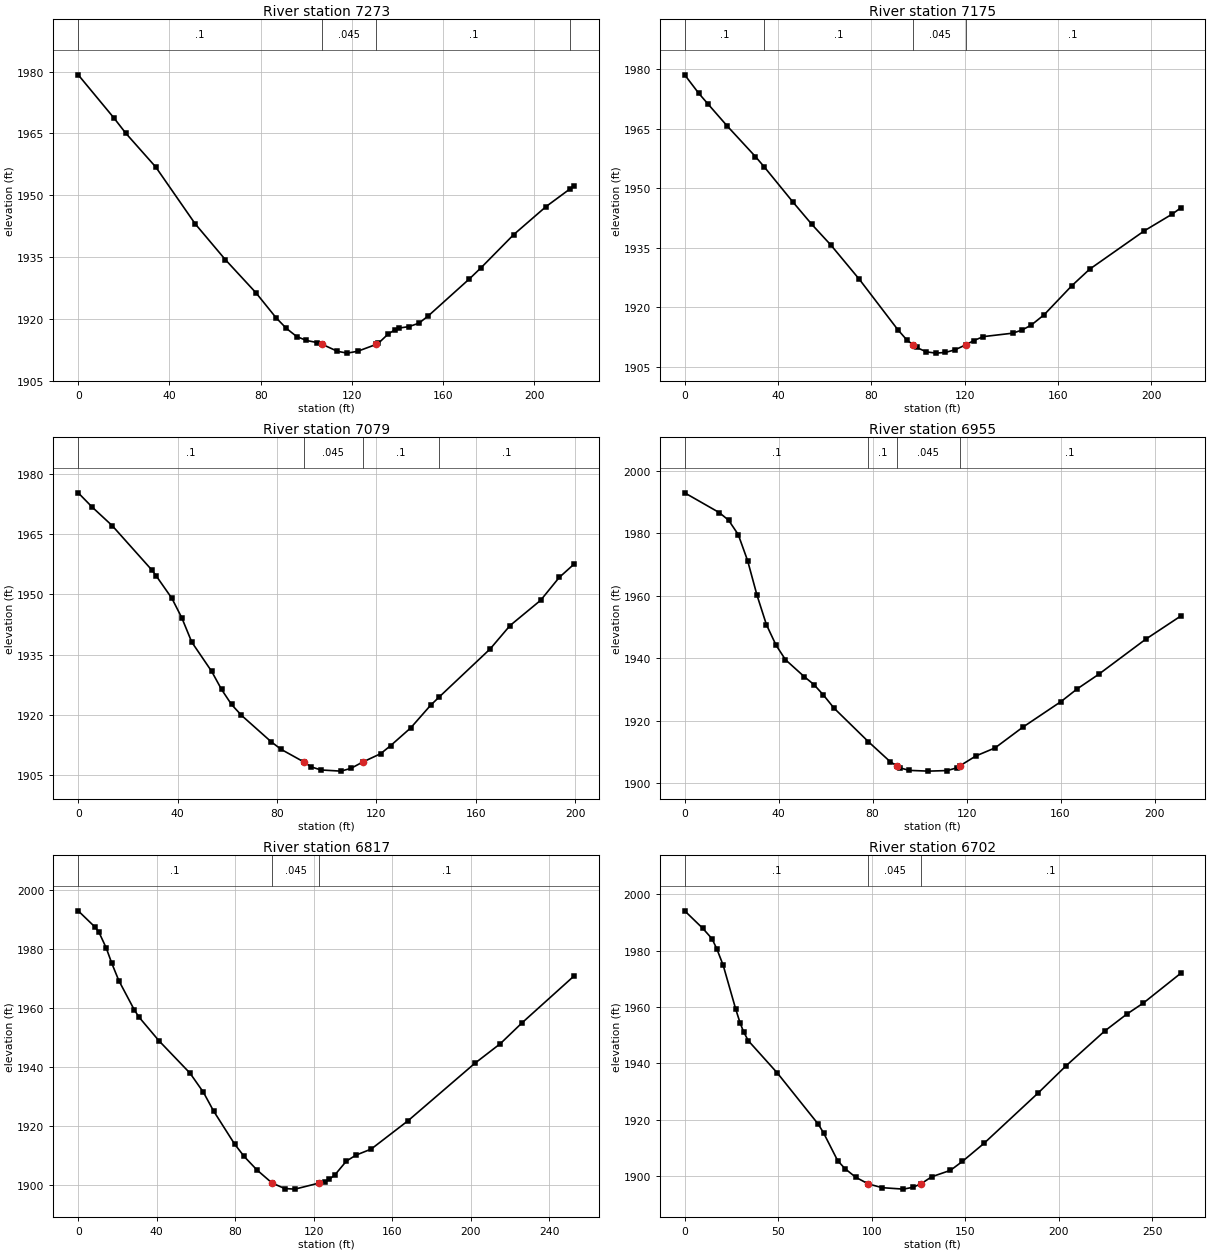
Type RM Length L Ch R = 1 ,7273    ,100.1,97.8,94.2
XS GIS Cut Line= 4
2443965.59295186622958.1826561382443988.70881438622903.282482657
2444037.83002223622805.0400669532444063.83536757622764.587307546
#Sta/Elev= 30
       0  1979.2    15.6 1968.78    20.9 1965.01      34 1956.84    51.3 1943.05
    64.5 1934.38    77.9 1926.36    86.8 1920.25    91.3 1917.69    95.8 1915.72
   100.1 1914.76   104.7 1914.26  107.041913.817   113.7 1912.13     118 1911.69
   122.6 1912.15  130.741913.818   131.6 1914.06   135.9 1916.31   138.9 1917.35
   140.5 1917.75     145 1918.12   149.4 1918.94   153.6 1920.76   171.6 1929.72
   176.7 1932.42     191 1940.45   205.2 1947.25   215.81951.574   217.5 1952.28
#Mann= 4 ,-1 , 0
       0      .1       0  107.04    .045       0  130.74      .1       0
   215.8      .1       0
Bank Sta=107.04,130.74
XS Rating Curve= 0 ,0
Exp/Cntr(USF)=0,0
Exp/Cntr=0.3,0.1

Type RM Length L Ch R = 1 ,7175    ,97.7,96.3,93.8
XS GIS Cut Line= 4
2444085.50648868622992.8564499162444094.17493712622933.622052212
2444117.29079964622822.3769638422444118.73554105622783.368945842
#Sta/Elev= 30
       0 1978.65       6 1974.01    10.1 1971.21    18.2 1965.75    30.3 1958.03
   34.071955.438    46.5 1946.47    54.5  1940.9    62.7 1935.66    74.9 1927.01
    91.3 1914.36    95.3 1911.68   97.961910.501    99.4 1909.86   103.5 1908.76
   107.6 1908.43   111.7 1908.61   115.8 1909.26  120.391910.502   123.9 1911.61
     128  1912.6   140.5 1913.46   144.4 1914.22   148.4 1915.46     154  1918.1
   165.8 1925.39   173.5  1929.6     197 1939.31   208.9 1943.51   212.5 1945.05
#Mann= 4 ,-1 , 0
       0      .1       0   34.07      .1       0   97.96    .045       0
  120.39      .1       0
Bank Sta=97.96,120.39
XS Rating Curve= 0 ,0
Exp/Cntr(USF)=0,0
Exp/Cntr=0.3,0.1

Type RM Length L Ch R = 1 ,7079    ,121.1,123.3,124.6
XS GIS Cut Line= 4
2444195.30683564622988.5222256932444198.19631845622939.401017842
2444201.08580127622838.2691193242444198.19631845622789.147911472
#Sta/Elev= 30
       0 1975.34     5.6 1971.79    13.7 1967.14    29.7 1956.04    31.3  1954.7
    37.7 1949.03    41.7 1944.16    45.7 1938.11    53.7 1930.82    57.7 1926.29
    61.7 1922.55    65.7 1919.85    77.7 1913.23    81.7 1911.35   90.961908.171
    93.7    1907    97.7 1906.22   105.7 1905.93   109.7  1906.6  114.42 1908.17
   121.7 1910.27   125.7 1912.27   133.8  1916.7   141.8 1922.34  145.371924.469
   165.8 1936.41   173.8 1942.24   186.1 1948.53   193.6 1954.24   199.6 1957.58
#Mann= 4 ,-1 , 0
       0      .1       0   90.96    .045       0  114.42      .1       0
  145.37      .1       0
Bank Sta=90.96,114.42
XS Rating Curve= 0 ,0
Exp/Cntr(USF)=0,0
Exp/Cntr=0.3,0.1

Type RM Length L Ch R = 1 ,6955    ,130.4,138.7,148.2
XS GIS Cut Line= 4
2444306.55192401 623001.524898362444312.33088964622949.514207694
2444326.77830371622864.2744646572444329.66778653622792.037394287
#Sta/Elev= 30
       0 1992.89    14.7 1986.58    18.7 1984.13    22.8 1979.54    26.8 1971.17
    30.8  1960.1    34.8 1950.72    38.9 1944.16    42.9 1939.52    50.9  1934.1
      55 1931.58      59 1928.28    63.6 1924.01    78.21913.301    87.4 1906.96
   90.341905.526    91.5 1904.96    95.6 1904.13   103.7 1903.89   111.8 1904.07
   115.8 1904.94  117.031905.529     124 1908.76   132.1 1911.31   143.9 1917.92
   160.2 1926.14     167 1930.15   176.2 1934.84   196.2 1946.05   211.1 1953.46
#Mann= 4 ,-1 , 0
       0      .1       0    78.2      .1       0   90.34    .045       0
  117.03      .1       0
Bank Sta=90.34,117.03
XS Rating Curve= 0 ,0
Exp/Cntr(USF)=0,0
Exp/Cntr=0.3,0.1

Type RM Length L Ch R = 1 ,6817    ,112.7,114.9,114.5
XS GIS Cut Line= 4
 2444362.8968389623039.088174953 2444401.9048569622989.966967101
2444484.25511712622922.0641209532444530.48684216622852.716533398
#Sta/Elev= 30
       0 1992.97     8.6 1987.44    10.5 1985.81    14.3 1980.34    17.1 1975.19
    20.7  1969.3    28.5 1959.48    30.9 1956.98    41.1 1948.93      57 1937.89
    63.8 1931.43      69 1925.07    79.7 1913.86    84.6 1909.63    91.1 1905.07
    98.81900.635   105.3 1898.75   110.5 1898.56  122.881900.637     126 1901.05
     128 1901.89   130.9 1903.44   136.7 1908.07   141.6  1910.1   149.3 1912.13
   168.2  1921.8   202.1  1941.2   215.2 1947.92   226.2 1954.95   252.8  1970.9
#Mann= 3 ,-1 , 0
       0      .1       0    98.8    .045       0  122.88      .1       0
Bank Sta=98.8,122.88
XS Rating Curve= 0 ,0
Exp/Cntr(USF)=0,0
Exp/Cntr=0.3,0.1

Type RM Length L Ch R = 1 ,6702    ,151.6,147.6,141.8
XS GIS Cut Line= 4
2444442.35761631 623118.54895236 2444481.3656343623066.538261693
2444565.16063593623002.9696397682444609.94761956622919.174638138
#Sta/Elev= 30
       0 1994.15     9.6 1987.98    14.6 1984.26    17.2 1980.62    20.6  1974.8
    27.3 1959.23    29.6 1954.41    31.5 1951.21      34 1948.05    49.6 1936.53
    71.5 1918.34    74.3 1915.26    81.8 1905.46    85.7 1902.62    91.4 1899.59
   98.211897.172   105.7 1895.85     117 1895.34     122 1895.99  126.271897.174
     132  1899.7   142.1 1902.01   148.5 1905.17     160 1911.56   189.2 1929.59
   203.9  1939.1   224.6 1951.47   236.4 1957.46   245.3 1961.42   265.2 1971.94
#Mann= 3 ,-1 , 0
       0      .1       0   98.21    .045       0  126.27      .1       0
Bank Sta=98.21,126.27
XS Rating Curve= 0 ,0
Exp/Cntr(USF)=0,0
Exp/Cntr=0.3,0.1

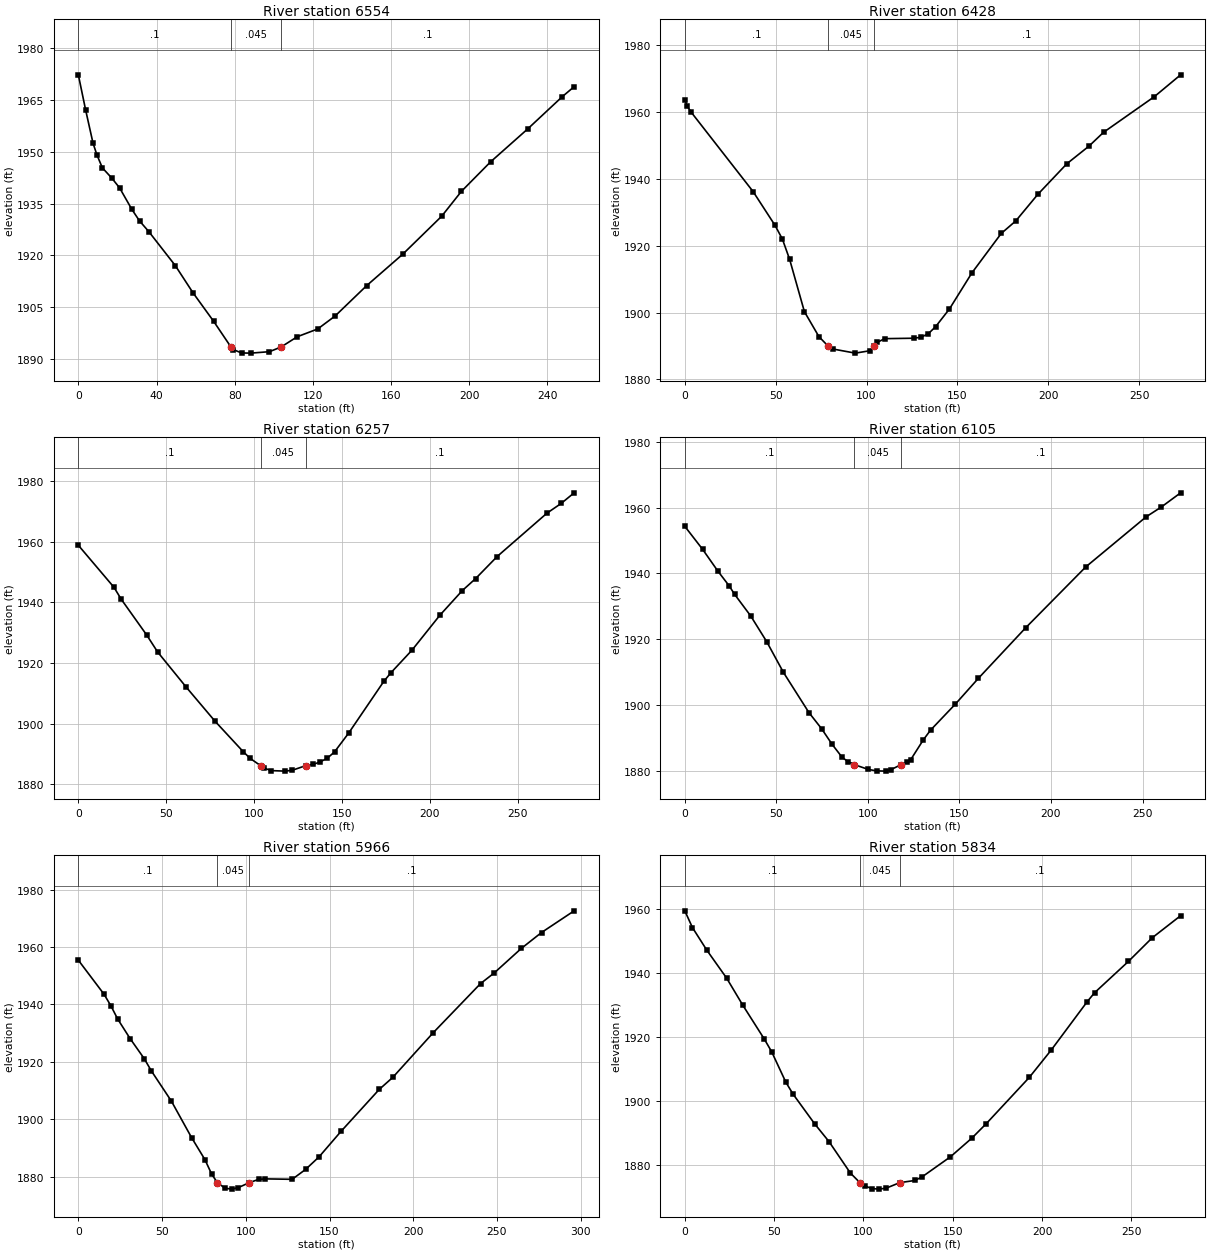
Type RM Length L Ch R = 1 ,6554    ,130.7,125.8,118.3
XS GIS Cut Line= 4
2444583.94227423623205.2334368042444609.94761956623164.780677397
2444663.40305164623080.9856757672444685.07417275622976.964294434
#Sta/Elev= 30
       0 1972.32     3.7 1962.22     7.5 1952.55     9.5 1949.12    12.3 1945.35
    17.1  1942.4    21.1 1939.56    27.4  1933.3    31.3 1929.98    36.1 1926.84
    49.6 1917.03    58.7 1909.11    69.3 1900.81   78.091893.414    79.3 1892.67
    83.5 1891.69    88.3 1891.64    97.8 1892.06  103.721893.412     112 1896.39
   122.5 1898.65   131.4 1902.41   147.5 1911.19     166 1920.32   185.9 1931.32
     196 1938.53   210.9 1947.07   229.9 1956.62   247.7 1966.03   253.7 1968.88
#Mann= 3 ,-1 , 0
       0      .1       0   78.09    .045       0  103.72      .1       0
Bank Sta=78.09,103.72
XS Rating Curve= 0 ,0
Exp/Cntr(USF)=0,0
Exp/Cntr=0.3,0.1

Type RM Length L Ch R = 1 ,6428    ,172.5,171.8,170.8
XS GIS Cut Line= 4
2444739.97434623623260.1336102852444747.19805327623206.678178211
2444755.86650171623095.4330898412444747.19805327622988.522225694
#Sta/Elev= 30
       0 1963.76     1.3  1961.8     3.6 1959.92    37.6 1936.21    49.6 1926.15
    53.7    1922    57.7  1915.9    65.8  1900.3    73.8 1892.81   79.011889.897
    81.8 1889.08    93.8 1887.88   101.9  1888.6  103.941889.894   105.9 1891.09
   109.9 1892.21   125.9 1892.34     130 1892.63     134  1893.7     138  1895.8
   145.6 1901.09     158 1911.92   174.1 1923.69   182.1 1927.44   194.2 1935.37
   210.2 1944.55   222.3 1949.79   230.4 1953.96   258.4 1964.65   272.8 1971.16
#Mann= 3 ,-1 , 0
       0      .1       0   79.01    .045       0  103.94      .1       0
Bank Sta=79.01,103.94
XS Rating Curve= 0 ,0
Exp/Cntr(USF)=0,0
Exp/Cntr=0.3,0.1

Type RM Length L Ch R = 1 ,6257    ,144.4,151.2,157.6
XS GIS Cut Line= 4
2444904.67486667623290.4731798412444920.56702216623231.238782137
2444922.01176356623091.098865619 2444909.0090909623011.638088212
#Sta/Elev= 30
       0 1958.89    20.3 1944.98    24.4 1941.06    38.9 1929.23    45.1 1923.64
    61.3 1912.07    77.7  1900.8    93.7 1890.76    97.7 1888.51  103.671886.092
   105.7 1885.29   109.7 1884.46   117.7 1884.29   121.7 1884.58  129.31 1886.09
   133.7 1886.52   137.7 1887.38   141.7  1888.6   145.7 1890.64   153.7 1896.81
   173.7  1913.9   177.7 1916.73   189.7  1924.2   205.7 1935.83   218.4 1943.93
     226 1947.91   238.2 1955.17   266.5 1969.48   274.6  1972.7     282 1976.21
#Mann= 3 ,-1 , 0
       0      .1       0  103.67    .045       0  129.31      .1       0
Bank Sta=103.67,129.31
XS Rating Curve= 0 ,0
Exp/Cntr(USF)=0,0
Exp/Cntr=0.3,0.1

Type RM Length L Ch R = 1 ,6105    ,144.1,139.5,133
XS GIS Cut Line= 4
2445011.58573082623323.7022322112445030.36736912623281.804731396
2445092.49124964623174.8938672482445117.05185356623076.651451545
#Sta/Elev= 30
       0 1954.33     9.7 1947.35    18.1 1940.68    24.2 1936.24    27.2 1933.64
      36 1927.06    44.7 1919.27    53.9 1909.86    67.8 1897.66    74.7 1892.76
    80.5 1887.97      86    1884    89.3  1882.7   92.541881.838   100.2 1880.37
   104.8 1879.92   109.8 1879.85   112.7 1880.33  118.191881.839   121.5 1882.57
   123.3 1883.26   130.3 1889.39   134.2 1892.31   147.8 1900.26   160.3 1908.06
   186.1 1923.42     219 1941.98     252 1957.23   260.3 1960.22   270.8 1964.52
#Mann= 3 ,-1 , 0
       0      .1       0   92.54    .045       0  118.19      .1       0
Bank Sta=92.54,118.19
XS Rating Curve= 0 ,0
Exp/Cntr(USF)=0,0
Exp/Cntr=0.3,0.1

Type RM Length L Ch R = 1 ,5966    ,131.9,132.1,132.3
XS GIS Cut Line= 4
2445180.62047549 623374.268181472445186.39944112623309.254818137
 2445183.5099583623198.0097297672445199.40211378 623079.54093436
#Sta/Elev= 30
       0 1955.39    15.4 1943.48    19.5 1939.43    23.5 1934.88    30.9 1928.09
    39.5 1920.96    43.5 1916.91    55.6 1906.26    67.6 1893.61    75.6 1885.91
    79.6 1880.89   83.02  1877.9    87.6 1875.95    91.6 1875.63    95.6 1876.18
  102.161877.903   107.6 1879.01   111.6  1879.2   127.7 1879.05   135.7 1882.49
   143.7 1886.84   156.9 1895.77   179.7 1910.37   187.8 1914.57     212 1930.16
   240.2 1947.24   248.3 1950.91   264.5 1959.46   276.6 1965.02   296.1 1972.58
#Mann= 3 ,-1 , 0
       0      .1       0   83.02    .045       0  102.16      .1       0
Bank Sta=83.02,102.16
XS Rating Curve= 0 ,0
Exp/Cntr(USF)=0,0
Exp/Cntr=0.3,0.1

Type RM Length L Ch R = 1 ,5834    ,139.5,139.7,138.8
XS GIS Cut Line= 4
2445309.20246075623403.1630096182445316.42616778623338.149646285
2445317.87090919623219.6808508782445303.42349512623127.217400804
#Sta/Elev= 30
       0 1959.52     4.3 1954.26    12.3 1947.24    23.4 1938.49    32.5 1929.98
    44.5 1919.42    48.6 1915.47    56.6 1905.88    60.6  1902.2    72.7  1892.9
    80.7 1887.37    92.7 1877.51      981874.533   100.7  1873.5   104.7 1872.68
   108.7  1872.5   112.7  1872.8  120.31 1874.53   128.7  1875.2   132.7 1876.29
   148.7 1882.62   160.7 1888.47   168.7 1892.96   192.8 1907.43   205.1 1916.01
   225.2  1931.1   229.3 1933.89   248.3 1943.71   261.6 1951.09   277.5    1958
#Mann= 3 ,-1 , 0
       0      .1       0      98    .045       0  120.31      .1       0
Bank Sta=98,120.31
XS Rating Curve= 0 ,0
Exp/Cntr(USF)=0,0
Exp/Cntr=0.3,0.1

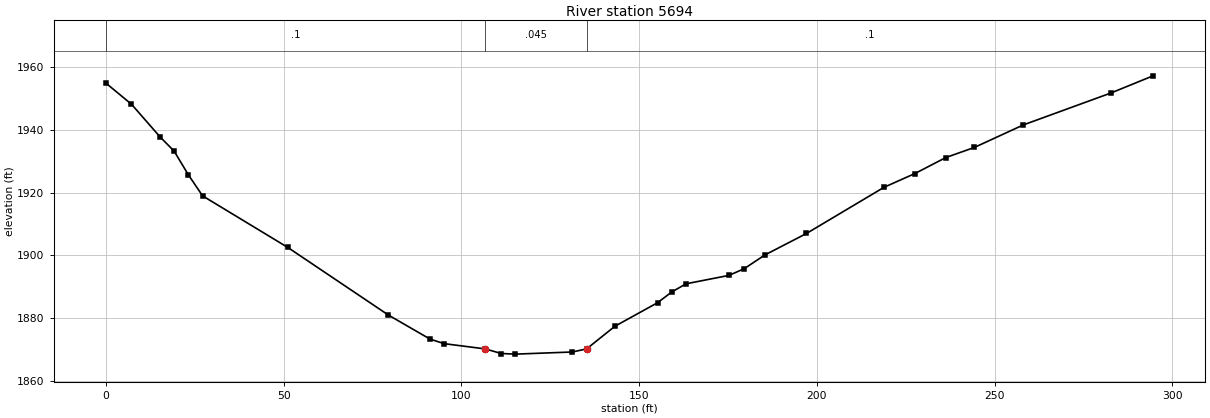
Type RM Length L Ch R = 1 ,5694    ,150.2,151.4,151.4
XS GIS Cut Line= 4
2445452.23186008623406.0524924332445455.12134289623330.925939248
2445453.67660149623231.2387821372445406.00013504623121.438435175
#Sta/Elev= 30
       0 1954.91     7.2 1948.18    15.2 1937.82    19.2 1933.23    23.2  1925.7
    27.2 1918.99    51.2 1902.54    79.5    1881    91.2 1873.35    95.2  1871.9
  106.791870.222   111.2 1868.77   115.2 1868.57   131.2 1869.25  135.231870.226
   143.2 1877.45   155.2 1884.95   159.2 1888.37   163.2 1890.97   175.3 1893.66
   179.6  1895.8   185.3  1900.1   197.1 1907.01   218.9 1921.71   227.6  1926.1
   236.3  1931.2   244.3  1934.4   258.1 1941.59   282.7 1951.74   294.6 1957.23
#Mann= 3 ,-1 , 0
       0      .1       0  106.79    .045       0  135.23      .1       0
Bank Sta=106.79,135.23
XS Rating Curve= 0 ,0
Exp/Cntr(USF)=0,0
Exp/Cntr=0.3,0.1