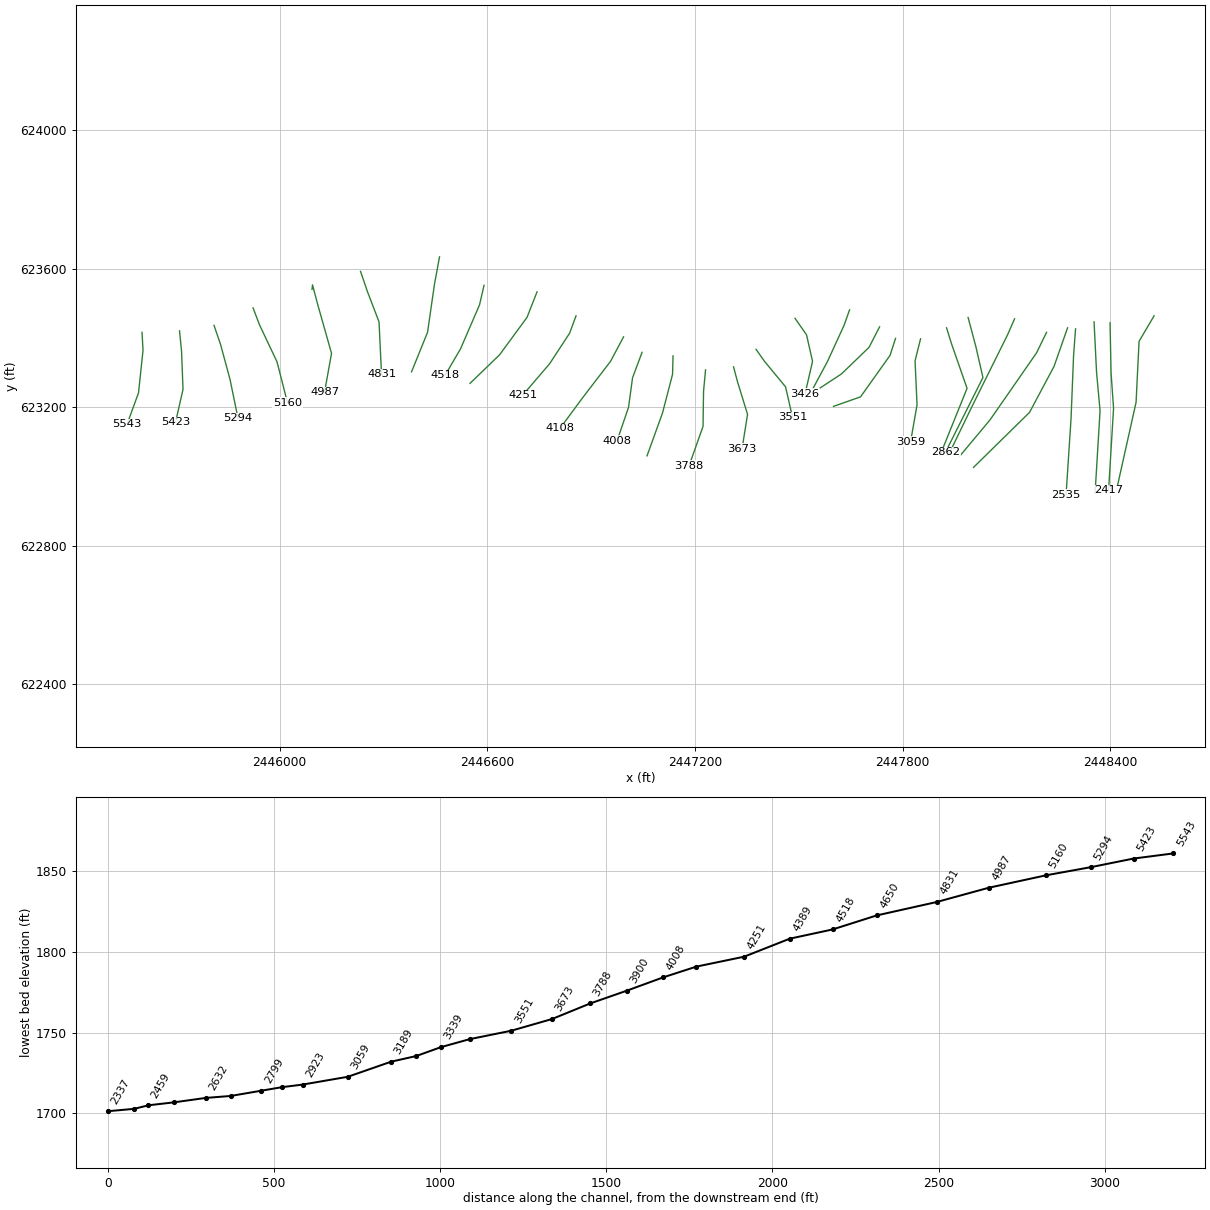
HEC-RAS study PETERSRN.prj: PETERSRN

--- PETERSRN.g01 (geometry) --- (continued)

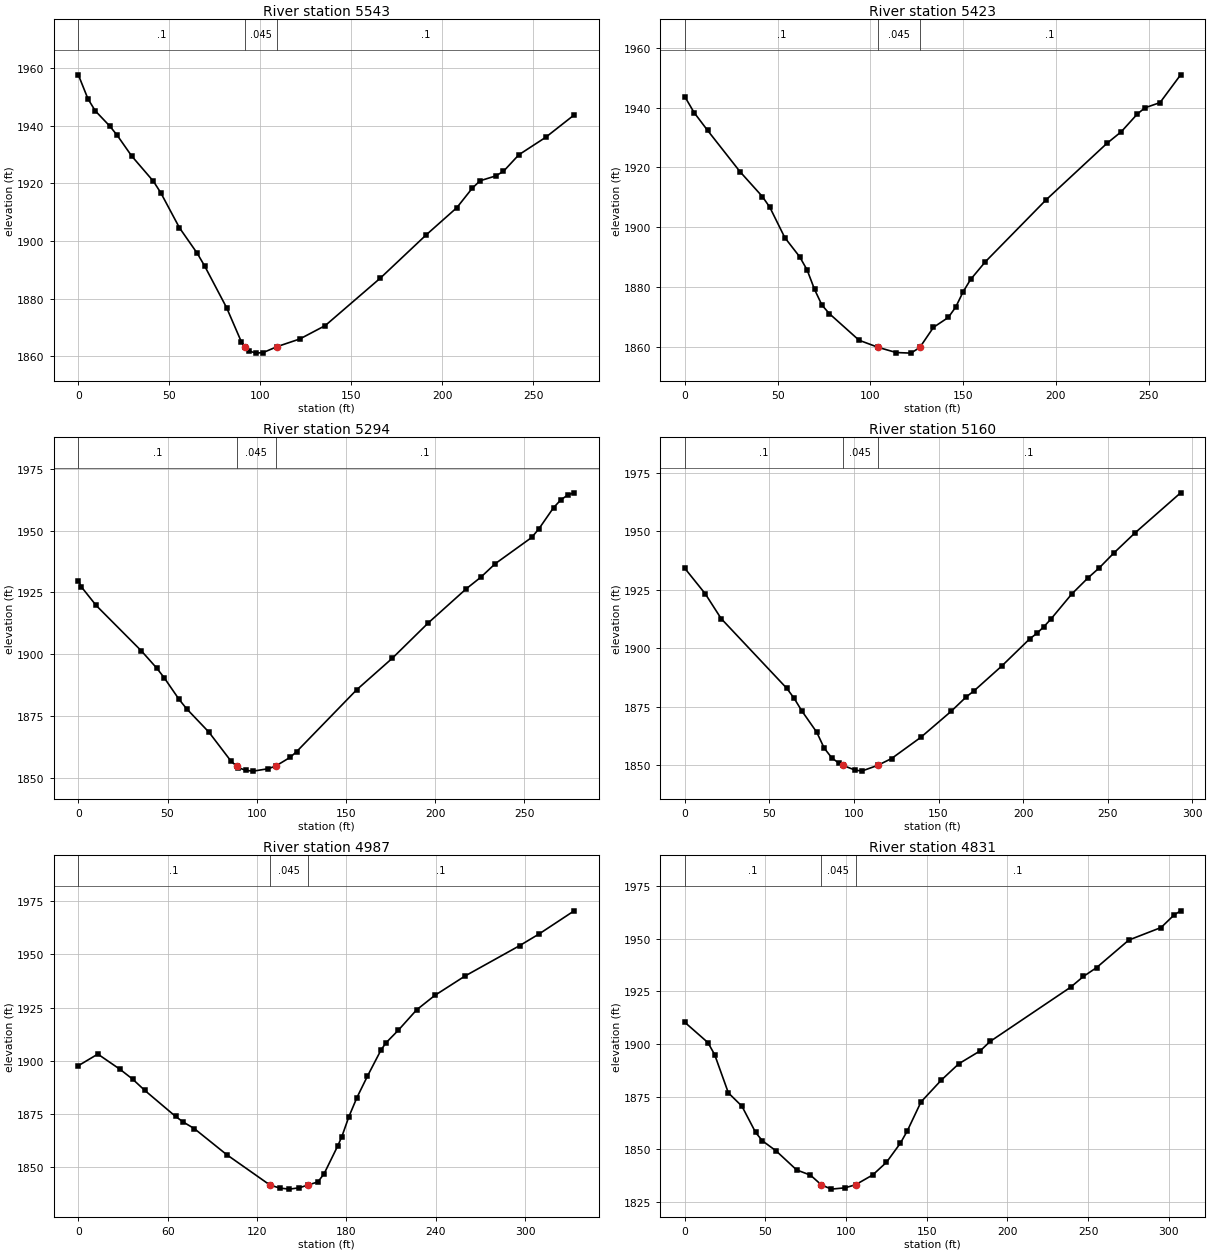
Type RM Length L Ch R = 1 ,5543    ,117.7,119.9,121
XS GIS Cut Line= 4
2445602.48496645623416.1656822852445605.37444926623364.154991618
 2445592.3717766623241.3519719892445559.14272423623150.333263323
#Sta/Elev= 30
       0 1957.64     5.3 1949.29     9.3 1945.16    17.3 1939.85    21.3 1936.72
    29.3 1929.51    41.3  1920.7    45.3 1916.76    55.6 1904.58    65.4 1895.72
    69.5 1891.27    81.5 1876.89    89.6 1865.06   91.651863.438    93.6 1861.94
    97.6 1861.15   101.6 1861.35  109.381863.437   121.7 1866.05   135.7  1870.7
     166 1887.17   191.2 1902.16     208 1911.57   216.5 1918.33   220.8 1920.91
   229.3 1922.57   233.6 1924.15   242.1 1929.92   256.8 1935.95   272.5 1943.73
#Mann= 3 ,-1 , 0
       0      .1       0   91.65    .045       0  109.38      .1       0
Bank Sta=91.65,109.38
XS Rating Curve= 0 ,0
Exp/Cntr(USF)=0,0
Exp/Cntr=0.3,0.1

Type RM Length L Ch R = 1 ,5423    ,124.8,128.7,130
XS GIS Cut Line= 4
  2445710.840572623420.4999065072445716.61953763623362.710250211
2445720.95376186623251.4651618412445699.28264075623156.112228952
#Sta/Elev= 30
       0 1943.65       5 1938.33    12.3 1932.35    29.8 1918.54    41.8 1910.27
    45.8  1906.7    53.9 1896.54    61.9 1890.15    65.9 1885.77    69.9 1879.28
    73.9 1874.01    77.9 1871.15    93.9 1862.27  104.281859.875   113.9 1858.16
   121.9 1857.96  126.66 1859.87     134 1866.57     142 1869.88     146 1873.34
     150 1878.46     154 1882.56     162  1888.5   194.6 1909.11   227.4 1927.99
   235.2 1931.91   243.8 1937.79   247.9  1939.9   256.1 1941.65   267.2 1950.93
#Mann= 3 ,-1 , 0
       0      .1       0  104.28    .045       0  126.66      .1       0
Bank Sta=104.28,126.66
XS Rating Curve= 0 ,0
Exp/Cntr(USF)=0,0
Exp/Cntr=0.3,0.1

Type RM Length L Ch R = 1 ,5294    ,132.8,134.6,136.6
XS GIS Cut Line= 4
2445810.52772912623436.3920619882445829.30936741623381.491888507
2445856.75945415623280.3599899892445879.87531667623167.670160211
#Sta/Elev= 30
       0 1929.82     1.6 1927.34      10 1919.72    35.4 1901.27    43.9 1894.37
    48.1 1890.47    56.5 1881.63    60.7 1877.87    73.2 1868.39    85.6 1856.63
    88.71854.645    89.7 1854.02    93.9 1852.91      98 1852.61   106.3 1853.57
  110.591854.644   118.7 1858.19   122.3 1860.48     156 1885.56   175.9 1898.29
   196.2  1912.7   217.4 1926.46   225.6 1931.17   233.7 1936.66   254.1 1947.27
   258.2 1950.83   266.4 1959.39   270.5 1962.54   274.6 1964.61   277.9 1965.35
#Mann= 3 ,-1 , 0
       0      .1       0    88.7    .045       0  110.59      .1       0
Bank Sta=88.7,110.59
XS Rating Curve= 0 ,0
Exp/Cntr(USF)=0,0
Exp/Cntr=0.3,0.1

Type RM Length L Ch R = 1 ,5160    ,174.1,172.9,171.1
XS GIS Cut Line= 4
2445923.21755889623486.9580112472445941.99919719623437.836803396
2445992.56514645623330.925939248  2446022.904716623212.457143841
#Sta/Elev= 30
       0 1934.27    12.1 1923.37    21.5 1912.76    60.3 1882.96    64.7 1878.63
    69.1  1873.4      78  1864.2    82.4 1857.41    86.8 1853.33    91.2 1850.87
   93.481850.007   100.4 1848.09   104.5 1847.57  113.931850.009   122.2 1852.94
   139.5 1862.01   157.5 1873.17   166.5 1879.39   170.9 1881.83   187.4 1892.52
   203.9 1904.11   208.1 1906.46   212.1 1909.19   216.3 1912.46   228.7 1923.24
   238.4 1930.21     245 1934.44   253.5 1940.72   265.9 1949.25   293.1 1966.53
#Mann= 3 ,-1 , 0
       0      .1       0   93.48    .045       0  113.93      .1       0
Bank Sta=93.48,113.93
XS Rating Curve= 0 ,0
Exp/Cntr(USF)=0,0
Exp/Cntr=0.3,0.1

Type RM Length L Ch R = 1 ,4987    ,154.5,156,157.2
XS GIS Cut Line= 5
2446093.69704497623540.4134433212446095.14178637623553.416115988
2446109.58920045623498.5159425072446150.04195985623355.486543174
2446129.81558015623242.796713396
#Sta/Elev= 30
       0 1897.74    13.1 1903.19    27.9 1896.09    36.4 1891.48    44.6 1886.17
    65.3 1873.94    70.5 1871.28    77.8 1868.27    99.6 1856.02  128.691841.743
   135.3 1840.31   141.8 1839.82   148.4 1840.45   154.21841.742   160.9  1843.2
   165.1  1847.1   174.2 1860.07     177 1864.51   181.7 1873.81   187.1 1882.77
   194.2 1892.88   203.3 1905.13   206.6 1908.46     215 1914.46   227.2 1923.95
   239.4 1930.72   259.7 1939.82   296.3 1954.05   309.3  1959.5     333 1970.42
#Mann= 3 ,-1 , 0
       0      .1       0  128.69    .045       0   154.2      .1       0
Bank Sta=128.69,154.2
XS Rating Curve= 0 ,0
Exp/Cntr(USF)=0,0
Exp/Cntr=0.3,0.1

Type RM Length L Ch R = 1 ,4831    ,187.8,180.8,174.6
XS GIS Cut Line= 4
2446233.83696148623592.4241339882446254.06334119623533.189736284
2446287.29239356 623446.50525184 2446294.5161006623294.807404063
#Sta/Elev= 30
       0  1910.3    14.3 1900.68    18.5 1894.94      27 1876.75    35.4 1870.43
    43.9 1857.93    48.1 1853.96    56.6 1849.17    69.3 1840.13    77.9 1837.64
   84.561833.068    90.8    1831    99.3 1831.62   105.81833.066   116.5 1837.76
     125 1843.76   133.6 1852.82   137.9 1858.69   146.4 1872.45     159 1882.84
   169.8 1890.58   183.1 1896.74   189.2 1901.18   239.1 1926.97   247.1 1932.12
   255.2 1936.29   275.2  1949.4   295.2 1955.36   303.2 1961.29   307.3 1963.29
#Mann= 3 ,-1 , 0
       0      .1       0   84.56    .045       0   105.8      .1       0
Bank Sta=84.56,105.8
XS Rating Curve= 0 ,0
Exp/Cntr(USF)=0,0
Exp/Cntr=0.3,0.1

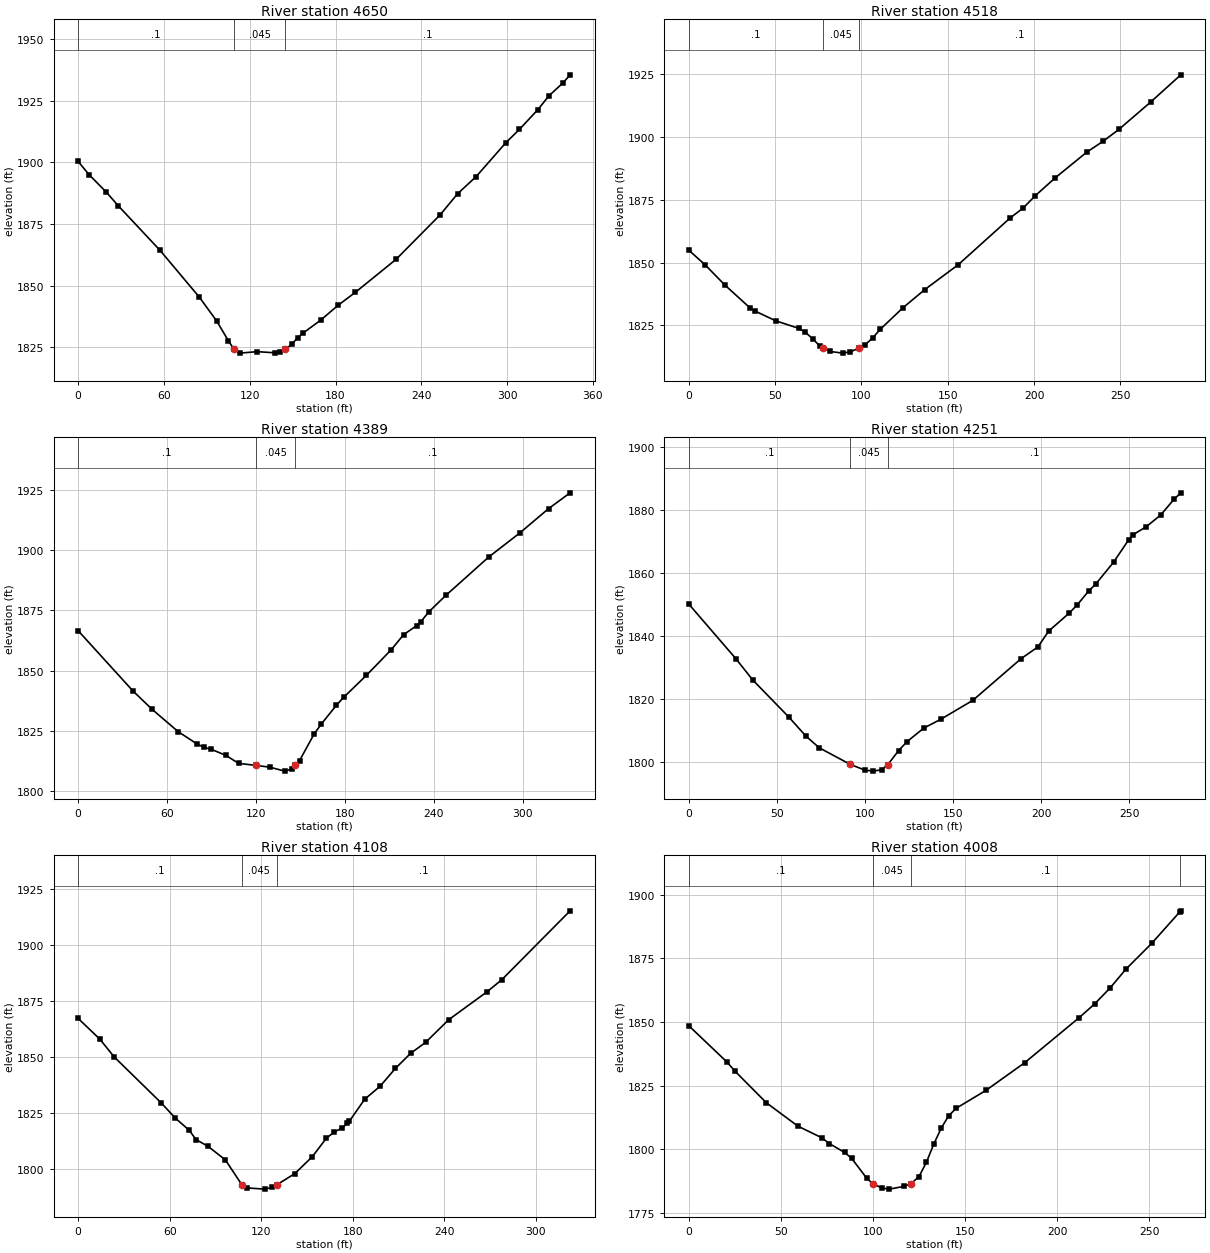
Type RM Length L Ch R = 1 ,4650    ,138.1,132.3,129.8
XS GIS Cut Line= 4
2446462.10610385623634.3216348022446447.65868978623556.305598803
2446427.43231008623416.1656822852446381.20058504  623302.0311111
#Sta/Elev= 30
       0 1900.35     7.6 1895.03    19.8 1887.85    27.9 1882.49    57.3 1864.31
    84.8 1845.32    96.9 1835.68     105 1827.76  108.981824.227   113.1 1822.66
   125.2 1823.26   137.4  1822.8   141.4 1823.29  144.851824.222   149.5  1826.2
   153.5 1828.96   157.6  1830.9   169.7 1836.06   181.8 1842.05   193.9 1847.31
   222.4  1860.7   253.2 1878.73   265.4 1887.27   278.4 1894.25   299.2 1907.99
   308.6 1913.33   321.6  1921.4   329.3 1926.98   339.2 1932.24   344.1 1935.47
#Mann= 3 ,-1 , 0
       0      .1       0  108.98    .045       0  144.85      .1       0
Bank Sta=108.98,144.85
XS Rating Curve= 0 ,0
Exp/Cntr(USF)=0,0
Exp/Cntr=0.3,0.1

Type RM Length L Ch R = 1 ,4518    ,132.5,129,127.1
XS GIS Cut Line= 4
2446590.68808911623551.9713745812446577.68541645623495.626459692
2446522.78524296 623368.489215842446477.99825934623291.917921248
#Sta/Elev= 30
       0 1854.96     9.3 1849.24    20.9 1841.09    35.3 1832.08    38.1 1830.82
    50.4 1826.84    63.7 1823.84    67.3 1822.36    71.7 1819.75    75.8 1816.84
   77.781816.002    81.9 1814.64    89.1 1813.98    93.5 1814.52   98.791816.001
   102.2 1817.33   106.6 1820.12   110.9 1823.48     124 1832.02   136.7  1839.3
   156.1 1849.22   186.3 1867.92   193.7 1871.78   200.4  1876.5   212.2 1883.77
   230.6 1894.08   239.9 1898.32   249.1 1903.08   267.7 1914.09     285 1924.83
#Mann= 3 ,-1 , 0
       0      .1       0   77.78    .045       0   98.79      .1       0
Bank Sta=77.78,98.79
XS Rating Curve= 0 ,0
Exp/Cntr(USF)=0,0
Exp/Cntr=0.3,0.1

Type RM Length L Ch R = 1 ,4389    ,134.4,137.5,137.2
XS GIS Cut Line= 4
 2446743.8306783623533.1897362842446714.93585015623459.507924507
2446635.47507274623351.1523189522446550.23532971 623268.80205873
#Sta/Elev= 30
       0 1866.57    36.8 1841.66    49.7 1834.02    67.4 1824.69    79.9 1819.64
    84.9 1818.08    89.8 1817.32    99.8 1814.75   108.3 1811.45  120.26 1810.61
   129.5 1809.86   139.4 1808.24   144.4 1809.17  146.621810.608   149.4 1812.59
   159.3 1823.72   164.2 1827.89   174.2 1835.53   179.1 1838.84   194.5 1848.01
   211.4 1858.74   219.6  1864.9   228.4 1868.67   231.2 1870.27   236.8 1874.49
   248.2 1881.27   277.2 1897.23     298 1907.14   317.5 1917.29     332 1923.83
#Mann= 3 ,-1 , 0
       0      .1       0  120.26    .045       0  146.62      .1       0
Bank Sta=120.26,146.62
XS Rating Curve= 0 ,0
Exp/Cntr(USF)=0,0
Exp/Cntr=0.3,0.1

Type RM Length L Ch R = 1 ,4251    ,142.9,143.3,141.3
XS GIS Cut Line= 4
2446856.52050807623463.8421487292446837.73886978 623413.27619947
2446779.94921348623325.1469736182446701.93317748623234.128264952
#Sta/Elev= 30
       0 1850.04    26.6 1832.79    36.3 1825.96    56.8 1814.18    66.4 1808.19
      74 1804.47    91.71799.164    99.8 1797.41   104.6 1797.06   109.4 1797.49
     1131799.162     119 1803.55   123.8  1806.4   133.3  1810.7   142.9 1813.48
   161.2 1819.53   188.6 1832.76   198.1 1836.46   204.2 1841.47   215.7 1847.12
   220.3 1849.73     227 1854.26   230.8 1856.33   241.1 1863.39   249.7 1870.52
   251.9    1872   259.5 1874.56   267.7 1878.27   275.3 1883.27   279.2 1885.35
#Mann= 3 ,-1 , 0
       0      .1       0    91.7    .045       0     113      .1       0
Bank Sta=91.7,113
XS Rating Curve= 0 ,0
Exp/Cntr(USF)=0,0
Exp/Cntr=0.3,0.1

Type RM Length L Ch R = 1 ,4108    ,93.9,99.7,104.8
XS GIS Cut Line= 4
2446993.77094178623403.1630096182446956.20766519623332.370680655
2446875.30214637623226.9045579152446810.28878304623138.775332063
#Sta/Elev= 30
       0  1867.2    14.3 1857.88    23.5 1850.09    54.6 1829.36    63.7 1822.66
    72.8 1817.25    77.3 1813.07    85.1 1810.07    96.5 1804.02  107.441792.782
   110.8 1791.46   122.3 1790.92   127.4 1791.71  130.111792.781   142.1 1797.87
   153.6 1805.45   162.7 1813.63   167.7 1816.34   172.8 1818.14   176.4 1820.25
   177.8 1821.22   187.9 1831.09     198 1836.89     208 1844.84   218.1 1851.65
   227.8 1856.46   242.9 1866.57   267.8 1878.94   277.7 1884.42   322.6 1915.27
#Mann= 3 ,-1 , 0
       0      .1       0  107.44    .045       0  130.11      .1       0
Bank Sta=107.44,130.11
XS Rating Curve= 0 ,0
Exp/Cntr(USF)=0,0
Exp/Cntr=0.3,0.1

Type RM Length L Ch R = 1 ,4008    ,109.3,108.6,106
XS GIS Cut Line= 4
2447047.22637385623358.3760259882447019.77628711623284.694214211
2447008.21835585623199.4544711742446974.98930348623102.656796878
#Sta/Elev= 30
       0 1848.52    20.8 1834.17    25.1 1830.62    42.1 1818.22    59.2 1809.03
      72 1804.53    76.3 1802.16    84.5 1798.71    88.3 1796.44    96.6 1788.49
   99.761786.439   104.7 1784.73   108.7 1784.27   116.7 1785.33  120.621786.439
   124.9 1789.19   128.9 1794.78   132.9 1801.91     137 1808.29     141 1813.09
     145 1816.03   161.2 1823.08   182.2 1833.94   211.8 1851.68   220.2 1857.08
   228.7 1863.44   237.1 1870.69   251.3 1880.99  266.371893.233     267 1893.71
#Mann= 4 ,-1 , 0
       0      .1       0   99.76    .045       0  120.62      .1       0
  266.37      .1       0
Bank Sta=99.76,120.62
XS Rating Curve= 0 ,0
Exp/Cntr(USF)=0,0
Exp/Cntr=0.3,0.1

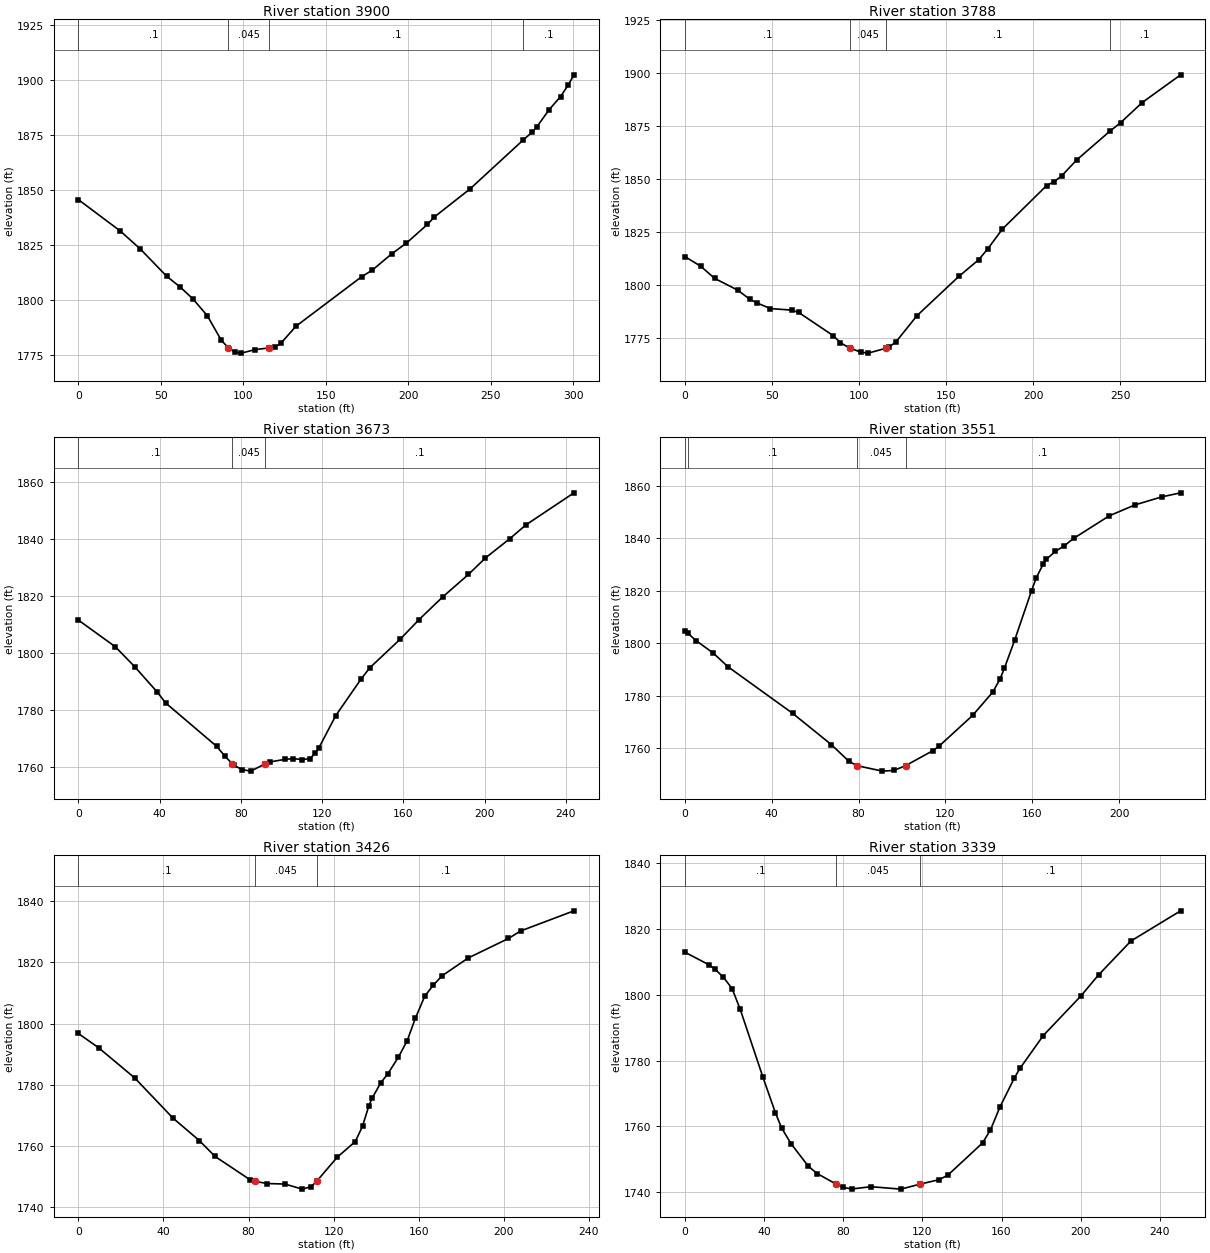
Type RM Length L Ch R = 1 ,3900    ,109.4,111.3,113.4
XS GIS Cut Line= 4
2447136.80034111623348.262836137 2447135.3555997623294.807404063
2447106.46077156623183.5623156932447061.67378793623059.314554656
#Sta/Elev= 30
       0 1845.67    25.4 1831.44    37.4  1823.4    53.5 1810.97    61.7 1806.05
    69.3  1800.8    78.2 1793.04    86.7 1781.86   91.011778.455    94.7 1776.61
    98.8 1776.07   107.1 1777.65  115.861778.453   119.5 1778.94   122.8 1780.54
   131.9 1788.23   171.8 1810.73   178.1 1813.61   189.9 1821.01   198.9 1825.94
   211.6 1834.38   215.9 1837.81   237.5 1850.51  269.781872.727     275 1876.14
   278.1 1878.77   285.5 1886.48   292.4 1892.39   296.9 1897.49   300.5 1902.22
#Mann= 4 ,-1 , 0
       0      .1       0   91.01    .045       0  115.86      .1       0
  269.78      .1       0
Bank Sta=91.01,115.86
XS Rating Curve= 0 ,0
Exp/Cntr(USF)=0,0
Exp/Cntr=0.3,0.1

Type RM Length L Ch R = 1 ,3788    ,112.3,115,118.8
XS GIS Cut Line= 4
2447230.70853259 623307.810076732447224.92956696623245.686196211
2447223.48482556623144.5542976932447183.03206615623030.419726508
#Sta/Elev= 30
       0 1813.55       9 1809.06      17 1803.31    30.2 1797.79    37.1 1793.55
    41.1  1791.8    49.1 1789.06    61.2 1788.34    65.2 1787.27    85.2 1776.25
    89.2 1772.99   94.711770.353   101.2 1768.48   105.2 1768.05   115.41770.353
   117.2 1770.92   121.2 1773.41   133.2  1785.7   157.2  1804.2   168.6 1812.06
   173.8 1817.16   182.3  1826.6   207.7  1847.1     212 1848.93   216.2 1851.57
   224.9 1859.15  243.861872.632   250.2 1876.78   262.5 1886.21   284.6  1899.3
#Mann= 4 ,-1 , 0
       0      .1       0   94.71    .045       0   115.4      .1       0
  243.86      .1       0
Bank Sta=94.71,115.4
XS Rating Curve= 0 ,0
Exp/Cntr(USF)=0,0
Exp/Cntr=0.3,0.1

Type RM Length L Ch R = 1 ,3673    ,117.7,122.3,124.5
XS GIS Cut Line= 4
2447311.61405141623316.4785251742447323.17198267623273.136282952
2447352.06681081623179.2280914712447336.17465533 623079.54093436
#Sta/Elev= 30
       01811.421  18.2021802.062  27.6761795.113  38.9011786.113  43.041  1782.3
  68.1311767.071  72.3171763.526   75.77    1761  76.502 1760.48  80.6871758.897
  84.8721758.385   92.121760.982  94.3171761.608 101.6121762.503 105.7971762.791
 110.319 1762.43 114.1671762.813 116.7191764.778 118.3521766.411 126.7221777.838
 139.1221790.607 143.4511794.621 158.5331804.737 167.7541811.571 179.4951819.594
 192.0581827.419 200.4561833.224  212.311839.905 220.4111844.844 244.0561856.093
#Mann= 3 ,-1 , 0
       0      .1       0   75.77    .045       0   92.12      .1       0
Bank Sta=75.77,92.12
XS Rating Curve= 0 ,0
Exp/Cntr(USF)=0,0
Exp/Cntr=0.3,0.1

Type RM Length L Ch R = 1 ,3551    ,131.4,125.2,118.6
XS GIS Cut Line= 4
2447376.62741474623367.0444744332447401.18801867623332.370680655
2447461.86715778623258.6888688782447482.09353748623170.559643026
#Sta/Elev= 30
       0 1804.79    1.361803.761     5.1 1800.99    13.1 1796.16    19.8    1791
    49.6 1773.21    67.4 1761.29    75.5 1754.93   79.161753.233      91 1751.14
    96.2  1751.4  101.66 1753.23   114.2 1758.94     117 1760.62   132.5 1772.38
   141.8 1781.28   145.2 1786.33   147.2 1790.45   151.9  1801.1   159.7 1820.05
   161.9    1825   165.2 1830.39   166.5    1832   170.6    1835   174.7 1837.13
   179.1    1840   195.5 1848.62   207.5 1852.83   219.8 1855.87   228.4  1857.4
#Mann= 4 ,-1 , 0
       0      .1       0    1.36      .1       0   79.16    .045       0
  101.66      .1       0
Bank Sta=79.16,101.66
XS Rating Curve= 0 ,0
Exp/Cntr(USF)=0,0
Exp/Cntr=0.3,0.1

Type RM Length L Ch R = 1 ,3426    ,102.1,86.3,77.7
XS GIS Cut Line= 4
2447489.31724452623456.6184416922447522.54629689623408.941975248
2447539.88319378623332.3706806552447518.21207267623238.462489174
#Sta/Elev= 30
       0 1796.78     9.5 1792.13    26.5 1782.25    44.5 1769.12    56.9 1761.77
    64.3 1756.58    80.7 1748.99   83.141748.425    88.9 1747.74    97.1 1747.57
   105.3 1745.91   109.4 1746.72  111.981748.428   121.7 1756.33   130.2 1761.47
   133.6 1766.46   136.6 1773.21   138.1 1775.62   142.2 1780.69   145.5  1783.6
   150.5 1789.07   154.6 1794.42   158.4 1801.69   162.8  1808.9   166.9  1812.6
     171 1815.63   183.3 1821.46   202.2 1827.82   207.9 1830.27     233 1836.86
#Mann= 3 ,-1 , 0
       0      .1       0   83.14    .045       0  111.98      .1       0
Bank Sta=83.14,111.98
XS Rating Curve= 0 ,0
Exp/Cntr(USF)=0,0
Exp/Cntr=0.3,0.1

Type RM Length L Ch R = 1 ,3339    ,86.2,74.4,70.1
XS GIS Cut Line= 4
2447646.79405792623481.1790456182447630.90190244623436.392061988
  2447583.225436623332.3706806552447541.32793518623254.354644656
#Sta/Elev= 30
       0 1812.97    12.1 1809.16    15.2 1807.79    19.4 1805.38    23.8 1801.93
    27.9 1795.65    39.4 1774.98    45.7 1764.18    48.8 1759.58    53.6 1754.77
    62.4 1747.88    66.8 1745.71   76.361742.485      80 1741.47    84.4 1741.01
      94  1741.7   109.1 1740.96  118.871742.484   128.4 1743.83   132.8 1745.18
   150.4    1755   154.4 1758.98   159.2 1765.94   166.4 1774.68   169.3 1777.67
   181.1 1787.66     200 1799.61     209 1806.07   225.4 1816.39   250.5 1825.56
#Mann= 3 ,-1 , 0
       0      .1       0   76.36    .045       0  118.87      .1       0
Bank Sta=76.36,118.87
XS Rating Curve= 0 ,0
Exp/Cntr(USF)=0,0
Exp/Cntr=0.3,0.1

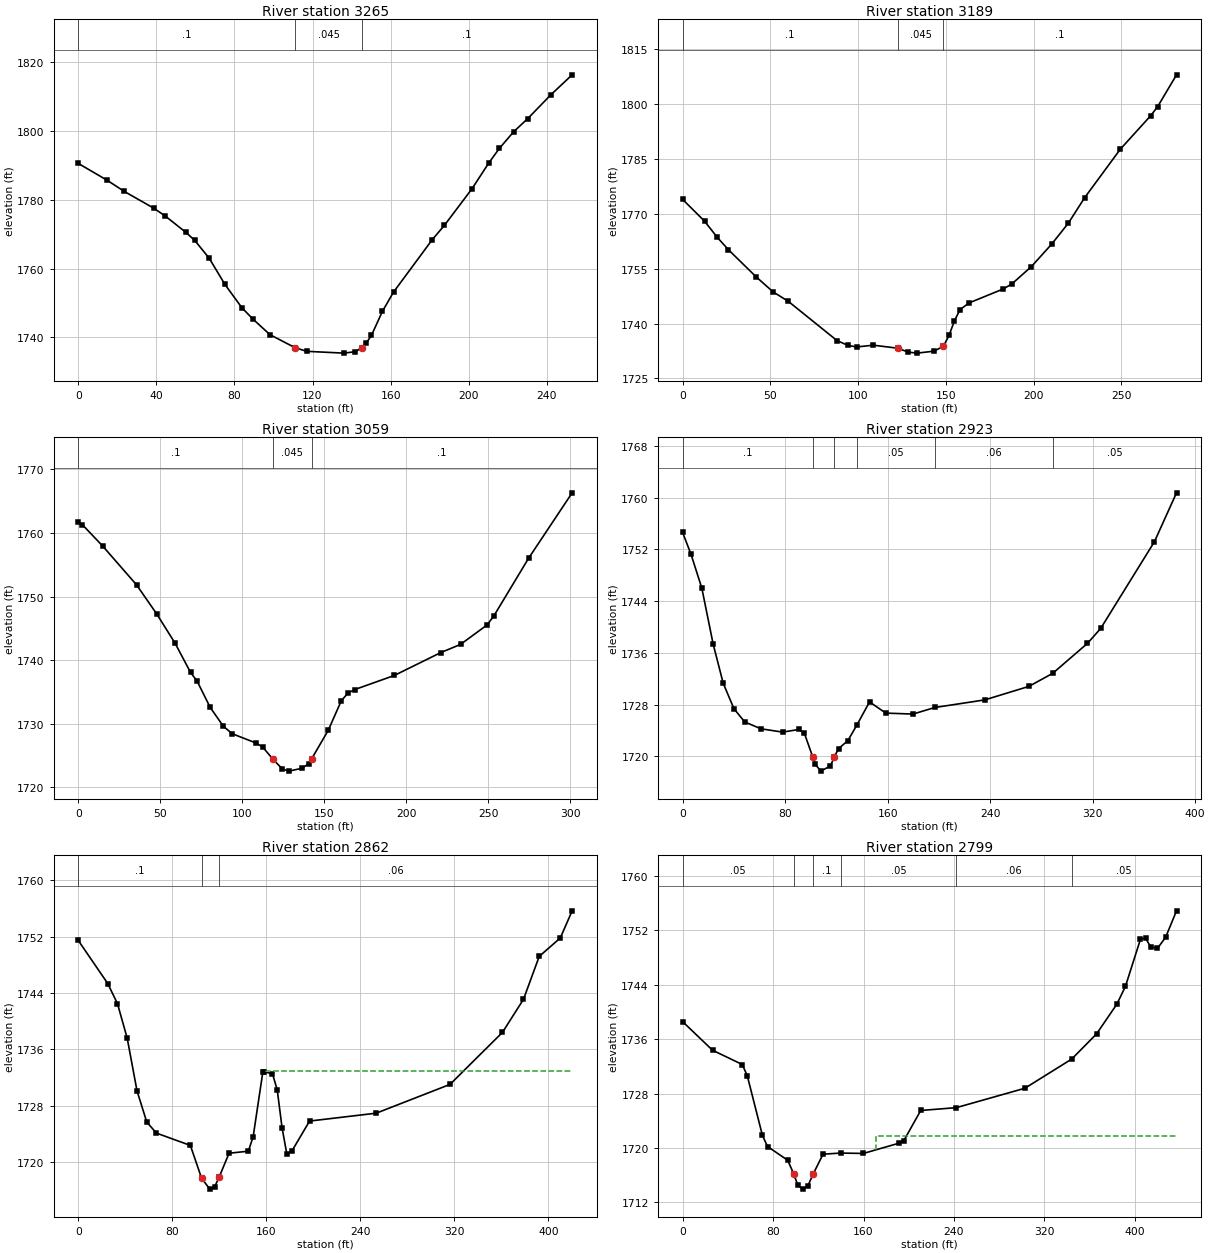
Type RM Length L Ch R = 1 ,3265    ,72.7,75.6,78.3
XS GIS Cut Line= 4
2447733.47854237623432.0578377662447703.13897281623372.823440063
2447623.67819541 623296.252145472447560.10957348623254.354644656
#Sta/Elev= 30
       0 1790.57    14.8 1785.66    23.5 1782.45    38.6 1777.58    44.5 1775.31
    55.2  1770.5    59.7 1768.18    67.1    1763    75.1 1755.43    83.8 1748.65
    89.3 1745.43    98.2 1740.81  111.091737.011   117.1 1735.96   136.1 1735.44
   141.7 1735.84  145.361737.011   147.4 1738.26   150.2 1740.59   155.8 1747.57
   161.5 1753.17   181.4 1768.45   187.6 1772.59   201.7  1783.2   210.3 1790.69
   215.7 1794.91     223 1799.74   230.3 1803.61   242.1 1810.51     253  1816.3
#Mann= 3 ,-1 , 0
       0      .1       0  111.09    .045       0  145.36      .1       0
Bank Sta=111.09,145.36
XS Rating Curve= 0 ,0
Exp/Cntr(USF)=0,0
Exp/Cntr=0.3,0.1

Type RM Length L Ch R = 1 ,3189    ,122.5,130.2,138.1
XS GIS Cut Line= 4
2447779.71026741623398.8287853962447763.81811192623349.707577544
2447678.57836889 623229.794040732447600.56233289623202.343953989
#Sta/Elev= 30
       0 1773.94    12.5 1767.99    19.8 1763.54    26.1 1760.19      42 1752.73
    51.6 1748.65    60.2 1746.09      88 1735.35    94.3 1734.02    99.3 1733.61
   108.7 1734.09   122.5 1733.27   128.7 1732.19   133.6 1731.92   143.2 1732.45
  148.641733.771   151.9 1736.81   154.8  1740.6   158.1 1743.82   163.4 1745.67
   182.7 1749.45   187.6 1750.81   198.8 1755.58   210.3 1761.69   219.8 1767.41
   229.1 1774.38   249.5 1787.68   266.8 1796.83   270.7 1799.26   281.5 1807.99
#Mann= 3 ,-1 , 0
       0      .1       0   122.5    .045       0  148.64      .1       0
Bank Sta=122.5,148.64
XS Rating Curve= 0 ,0
Exp/Cntr(USF)=0,0
Exp/Cntr=0.3,0.1

Type RM Length L Ch R = 1 ,3059    ,131.6,136.3,139
XS GIS Cut Line= 4
2447851.94733778623397.3840439882447836.05518229623333.815422063
2447841.83414792623206.6781782112447823.05250963623099.767314063
#Sta/Elev= 30
       0 1761.67     2.6 1761.27    14.9 1757.94    35.6 1751.83    47.9 1747.26
    59.1 1742.66    68.5 1738.08    72.5 1736.72    80.5 1732.58    88.5 1729.63
    93.9 1728.45   108.5 1726.98   112.5 1726.36  118.661724.473   124.5 1722.91
   128.5 1722.57   136.5 1723.02   140.5 1723.73  142.321724.474   152.5 1728.98
   160.5 1733.64   164.6 1734.84   168.6 1735.38   192.8  1737.6     221 1741.18
   233.2 1742.48   249.4 1745.54   253.5 1746.94   274.7 1756.01   301.3  1766.3
#Mann= 3 ,-1 , 0
       0      .1       0  118.66    .045       0  142.32      .1       0
Bank Sta=118.66,142.32
XS Rating Curve= 0 ,0
Exp/Cntr(USF)=0,0
Exp/Cntr=0.3,0.1

Type RM Length L Ch R = 1 ,2923    ,61.9,61,60
XS GIS Cut Line= 4
2447927.07389096623429.1683549512447941.52130503623382.936629914
2447986.30828866623254.3546446552447911.18173548623067.983003101
#Sta/Elev= 30
       0 1754.61     6.6 1751.21      15    1746    23.9  1737.3    31.7 1731.29
    40.1 1727.35    48.5 1725.31    61.2 1724.25    78.1 1723.74    90.8 1724.15
    95.1 1723.53  101.531719.927   103.5  1718.8   107.8 1717.71   115.4 1718.51
  118.431719.928   121.7 1721.18     129 1722.43  136.251724.911   145.9 1728.41
   158.6 1726.68   179.8 1726.53  196.831727.546   235.8 1728.72   270.3 1730.81
  288.871732.829     316 1737.46   326.3 1739.76   368.3 1753.19   385.5 1760.73
#Mann= 6 ,-1 , 0
       0      .1       0  101.53    .045       0  118.43      .1       0
  136.25     .05       0  196.83     .06       0  288.87     .05       0
Bank Sta=101.53,118.43
XS Rating Curve= 0 ,0
Exp/Cntr(USF)=0,0
Exp/Cntr=0.3,0.1

Type RM Length L Ch R = 1 ,2862    ,68.3,62.6,56.6
XS GIS Cut Line= 4
2447989.29763613623459.1777643882448011.68653303623375.219401007
2448032.20968853623285.6638134012447923.99668684623069.859723822
#Sta/Elev= 30
       0 1751.49    25.1 1745.36    33.4 1742.49    41.7 1737.56      50 1730.11
    58.3 1725.68    66.5 1724.11    95.4 1722.36   104.91717.718   111.9 1716.15
     116 1716.46   120.1 1717.94   128.3 1721.25   144.7 1721.54   148.8 1723.58
     157 1732.74   157.8 1732.82   165.2 1732.56   169.3 1730.25   173.4 1724.88
   177.5 1721.09   181.9  1721.6   196.8 1725.82   253.5 1726.94   316.3 1731.03
   360.9 1738.42   378.8 1743.12   392.2 1749.22   410.1 1751.83   420.2 1755.69
#Mann= 3 , 0 , 0
       0      .1       0   104.9    .045       0   120.1     .06       0
#XS Ineff= 2 , 0
                          159.92         1732.97
Permanent Ineff=
       F       F
Bank Sta=104.9,120.1
XS Rating Curve= 0 ,0
Exp/Cntr(USF)=0,0
Exp/Cntr=0.3,0.1

Type RM Length L Ch R = 1 ,2799    ,93.2,92.6,91.5
XS GIS Cut Line= 4
2448123.55872237623455.1737002842448103.33234266623408.941975248
2448002.20044415623205.2334368042447932.85285659623062.204037471
#Sta/Elev= 30
       0 1738.58    26.5 1734.37    52.8 1732.27    57.2 1730.61    70.6 1721.84
    75.1 1720.21    92.9 1718.19   98.191716.221   101.9  1714.5   106.3 1713.94
   110.8 1714.43  115.641716.221   124.2 1719.08  139.731719.244   159.9 1719.19
   191.2 1720.69   195.7 1721.09   210.6 1725.51  242.041725.925   302.7 1728.78
  344.151733.078   366.1 1736.78     384 1741.14   391.6 1743.75   404.9  1750.7
   409.4 1750.86   413.9 1749.59   419.9 1749.34   427.2    1751   436.8 1754.88
#Mann= 6 ,-1 , 0
       0     .05       0   98.19    .045       0  115.64      .1       0
  139.73     .05       0  242.04     .06       0  344.15     .05       0
#XS Ineff= 2 , 0
                          170.72         1721.72
Permanent Ineff=
       F       F
Bank Sta=98.19,115.64
XS Rating Curve= 0 ,0
Exp/Cntr(USF)=0,0
Exp/Cntr=0.3,0.1

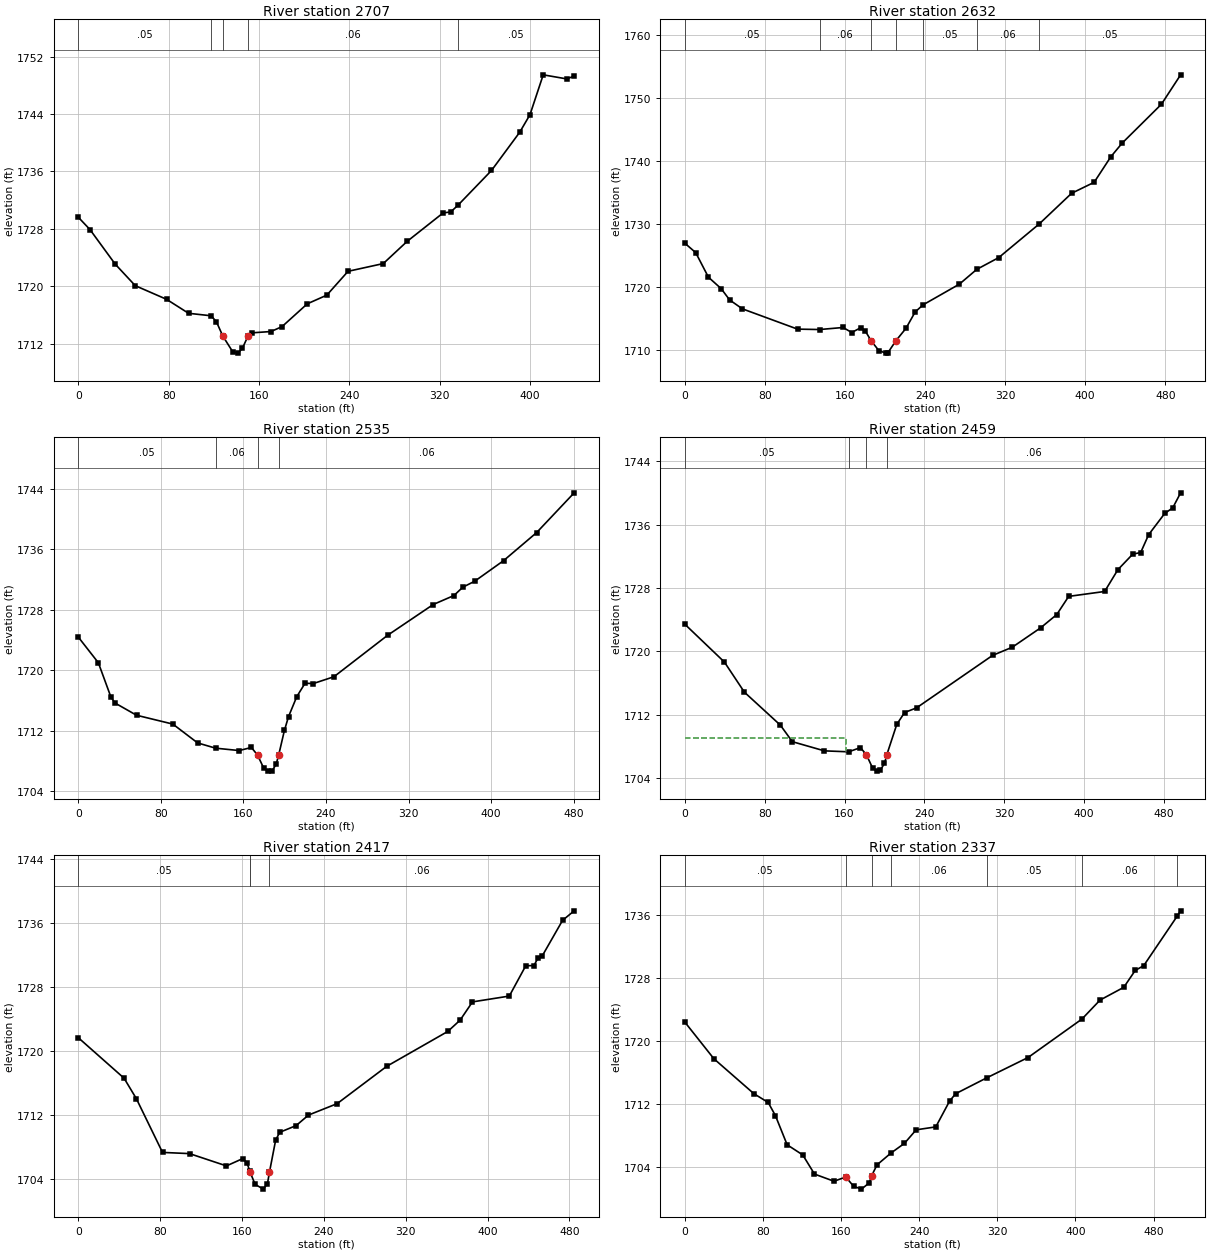
Type RM Length L Ch R = 1 ,2707    ,72.4,74.7,75.6
XS GIS Cut Line= 4
2448216.02217244623416.1656822852448187.12734429623356.931284581
 2448052.7663934623163.3359359892447964.63716755623057.869813249
#Sta/Elev= 30
       0  1729.6    10.3 1727.89    32.6 1723.08    50.4 1720.07    78.1 1718.17
    97.6 1716.22  117.691715.873   122.3 1715.02  128.07 1713.01   136.7 1710.86
   141.4 1710.67   145.3 1711.36  150.131713.012   153.9  1713.5   170.6 1713.68
   180.4 1714.37   202.7 1717.54     220 1718.75   238.8 1722.07     270 1723.15
   291.1 1726.24     323 1730.21   329.7 1730.34  336.241731.297   365.8 1736.12
   390.8 1741.45   399.9  1743.9   411.6 1749.45   432.5 1748.88     439 1749.28
#Mann= 5 ,-1 , 0
       0     .05       0  117.69     .06       0  128.07    .045       0
  150.13     .06       0  336.24     .05       0
Bank Sta=128.07,150.13
XS Rating Curve= 0 ,0
Exp/Cntr(USF)=0,0
Exp/Cntr=0.3,0.1

Type RM Length L Ch R = 1 ,2632    ,89.3,96.8,100.8
XS GIS Cut Line= 4
2448276.70131155623429.1683549512448237.69329355623317.923266581
2448166.90096459  623185.00705712448005.08992696623026.085502286
#Sta/Elev= 30
       0  1726.9    10.9  1725.4    23.6  1721.5    36.3 1719.69    44.8 1717.89
    57.5 1716.48   112.6 1713.26   134.61713.194   158.2 1713.52   166.7 1712.72
   175.7 1713.48   180.2    1713  186.051711.428   193.8 1709.86   200.7 1709.45
   202.9 1709.52  210.951711.428     221  1713.4   230.1 1715.98  237.891717.101
   274.3  1720.4  291.681722.747   313.6 1724.61  354.081729.957   386.4 1734.82
   408.9 1736.56   425.6 1740.62     437  1742.8   476.1 1748.95   495.3 1753.62
#Mann= 7 ,-1 , 0
       0     .05       0   134.6     .06       0  186.05    .045       0
  210.95     .06       0  237.89     .05       0  291.68     .06       0
  354.08     .05       0
Bank Sta=186.05,210.95
XS Rating Curve= 0 ,0
Exp/Cntr(USF)=0,0
Exp/Cntr=0.3,0.1

Type RM Length L Ch R = 1 ,2535    ,74.5,76.4,77.2
XS GIS Cut Line= 4
2448299.81717407623426.2788721362448294.03820844623348.262836137
 2448286.8145014623167.6701602112448272.36708733622946.624724879
#Sta/Elev= 30
       0  1724.4    19.4 1721.01    31.5  1716.5    35.5 1715.69    56.4 1714.07
    91.6  1712.9   115.6 1710.41     1331709.715   155.9  1709.4   167.7 1709.81
  173.661708.806   179.7 1707.06   183.7 1706.68   187.7  1706.7   191.7 1707.59
  194.161708.808   199.7 1712.06   203.7 1713.89   211.7 1716.53   219.7  1718.3
   227.7 1718.26   247.7 1719.16   299.8 1724.65   343.9 1728.71     364  1729.9
   372.6    1731   384.1 1731.79   412.1 1734.51   444.1 1738.22   480.5 1743.48
#Mann= 4 ,-1 , 0
       0     .05       0     133     .06       0  173.66    .045       0
  194.16     .06       0
Bank Sta=173.66,194.16
XS Rating Curve= 0 ,0
Exp/Cntr(USF)=0,0
Exp/Cntr=0.5,0.3

Type RM Length L Ch R = 1 ,2459    ,41.7,42,41.7
XS GIS Cut Line= 4
2448353.27260614 623446.505251842448360.49631318623300.586369692
2448370.60950303623189.3412813222448356.16208896622950.958949101
#Sta/Elev= 30
       0 1723.42    39.7 1718.63    59.7 1714.83    95.7 1710.67   107.7 1708.58
   139.8 1707.42  164.141707.299   175.9 1707.83  181.861706.932     188 1705.28
     192 1704.86     196 1705.02     200 1705.83  202.331706.931   212.3 1710.76
   220.1 1712.26   232.1 1712.85   308.3 1719.48     328 1720.51   356.4 1722.96
   372.5 1724.63   384.5 1726.93   420.5 1727.55   433.8 1730.31   448.6 1732.26
   456.6 1732.47   464.6 1734.73   480.7 1737.41   488.7 1738.11   496.6 1740.01
#Mann= 4 ,-1 , 0
       0     .05       0  164.14     .06       0  181.86    .045       0
  202.33     .06       0
#XS Ineff= 2 , 0
             1611709.025     232        1709.025
Permanent Ineff=
       F       F
Bank Sta=181.86,202.33
XS Rating Curve= 0 ,0
Exp/Cntr(USF)=0,0
Exp/Cntr=0.5,0.3

Type RM Length L Ch R = 1 ,2417    ,83.4,80.1,77.9
XS GIS Cut Line= 4
2448399.50433118623443.615769025  2448402.393814623299.141628285
2448409.61752103623196.5649883592448395.17010696622959.627397545
#Sta/Elev= 30
       0 1721.65    44.7 1716.58    56.7 1714.02    82.3 1707.28   108.7 1707.13
   144.8 1705.59   160.8 1706.51   164.8    1706  167.59 1704.94  167.981704.792
   172.8 1703.28   180.8 1702.68   184.9 1703.38  186.81 1704.79   192.9 1708.83
   196.9  1709.8   212.9 1710.64     225 1711.96     253 1713.39   301.5 1718.07
   361.2 1722.44   373.2 1723.85   385.3 1726.14   421.3 1726.87   437.4 1730.67
   445.4 1730.69   449.4 1731.66   453.4 1731.88   473.4 1736.36   484.7 1737.55
#Mann= 4 ,-1 , 0
       0     .05       0  167.59     .06       0  167.98    .045       0
  186.81     .06       0
Bank Sta=167.98,186.81
XS Rating Curve= 0 ,0
Exp/Cntr(USF)=0,0
Exp/Cntr=0.5,0.3

Type RM Length L Ch R = 1 ,2337    ,96.9,92.7,87.5
XS GIS Cut Line= 4
2448526.64157503623463.8421487292448483.29933281623390.160336951
2448474.63088437623213.9018852482448421.17545229622974.074811619
#Sta/Elev= 30
       0  1722.4    29.8 1717.74    70.7 1713.31    85.4 1712.19    92.8 1710.52
   104.8 1706.82   120.8 1705.53   132.8  1703.1   152.8 1702.19   164.8 1702.73
   172.9 1701.55   180.9 1701.19   188.9 1701.99  191.341702.907   196.9 1704.28
  211.041705.764   224.9    1707   236.9 1708.72     257 1709.09   271.1 1712.36
   277.3  1713.3  308.961715.305   351.5  1717.9   406.71722.785   425.2 1725.19
   449.5 1726.81   461.2 1728.95   469.9 1729.56  504.441735.891   507.7 1736.52
#Mann= 7 ,-1 , 0
       0     .05       0   164.8    .045       0  191.34     .05       0
  211.04     .06       0  308.96     .05       0   406.7     .06       0
  504.44      .1       0
Bank Sta=164.8,191.34
XS Rating Curve= 0 ,0
Exp/Cntr(USF)=0,0
Exp/Cntr=0.3,0.1