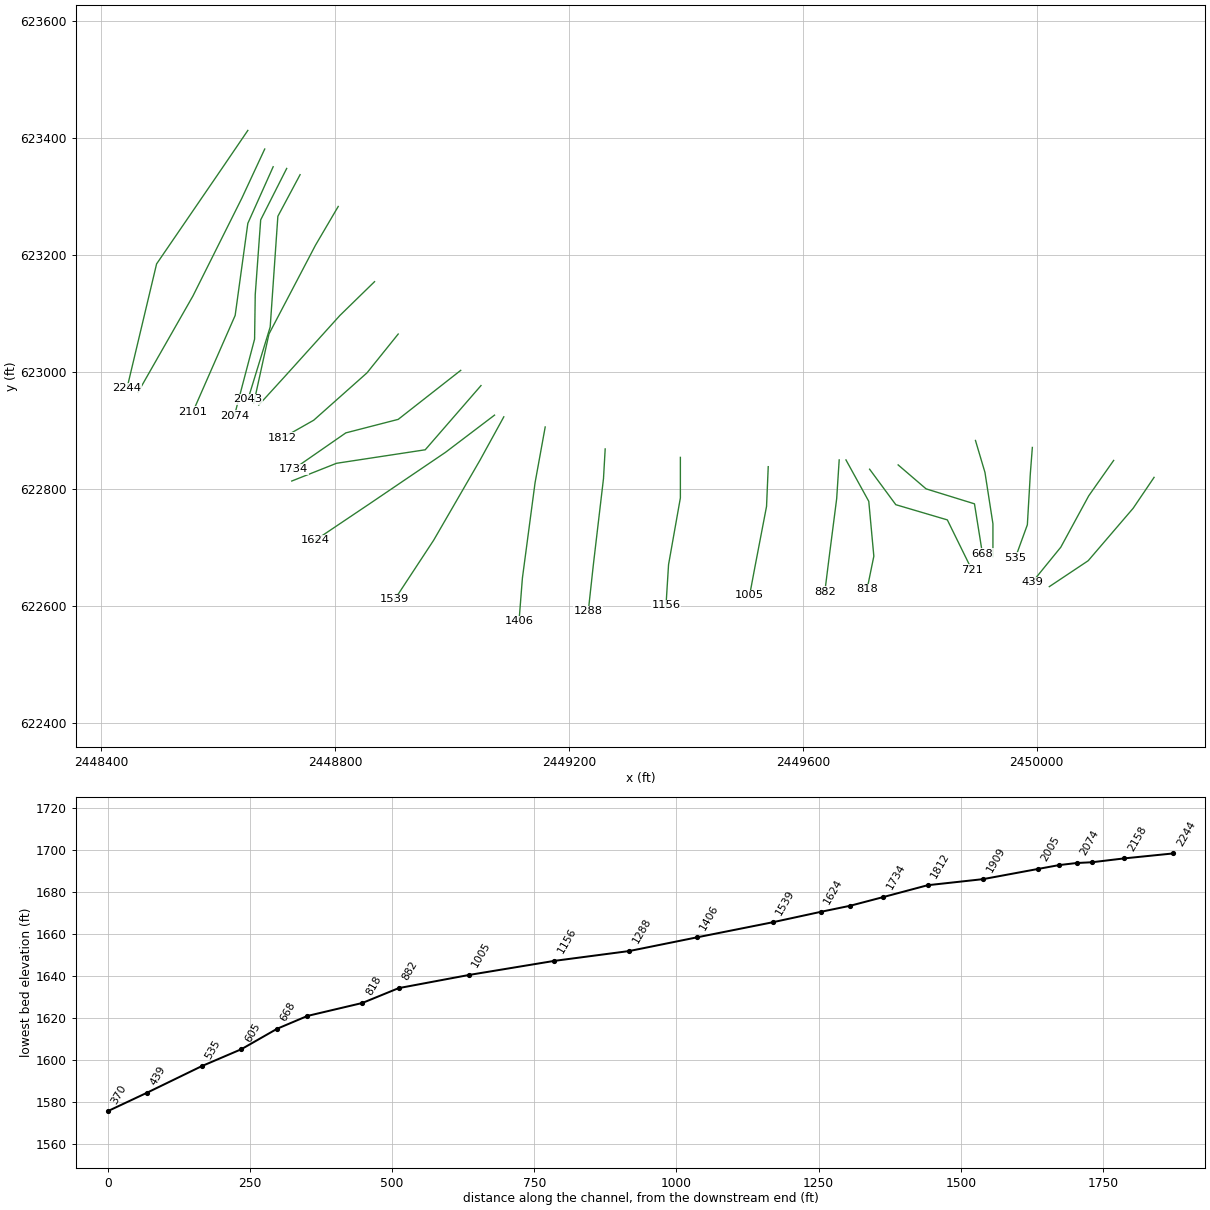
HEC-RAS study PETERSRN.prj: PETERSRN

--- PETERSRN.g01 (geometry) --- (continued)

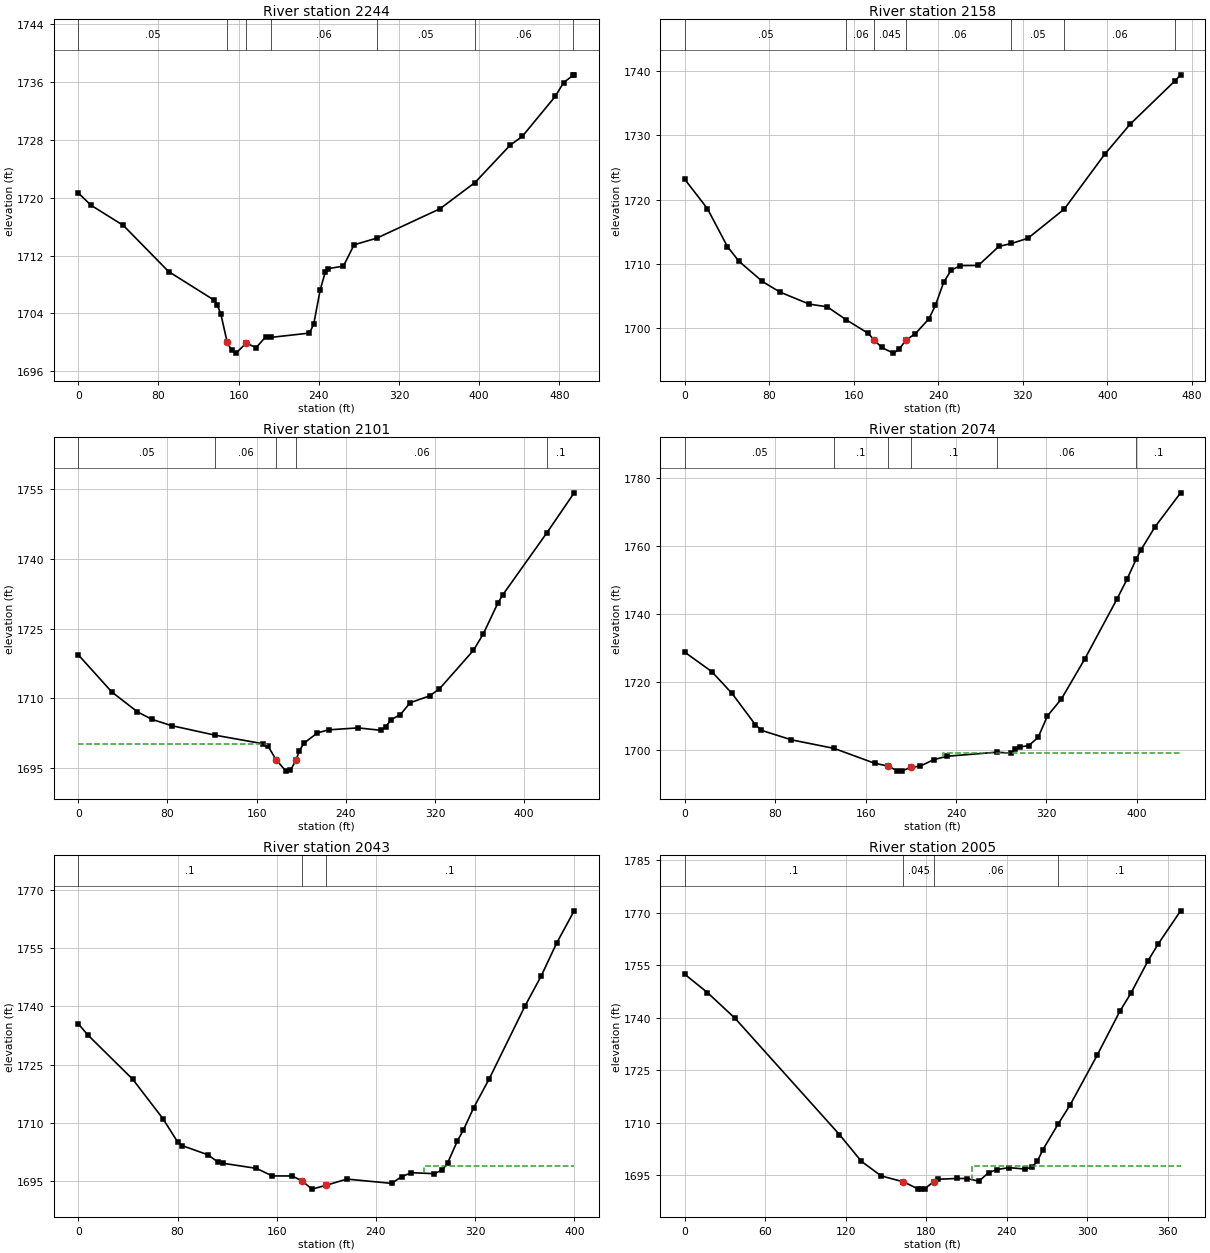
Type RM Length L Ch R = 1 ,2244    ,79.7,86.3,88.8
XS GIS Cut Line= 4
2448650.88933607 623413.276199472448604.65761103623345.373353322
2448494.85726407  623185.00705712448444.29131481622972.630070212
#Sta/Elev= 30
       0 1720.65    12.6 1718.96      45 1716.16      90  1709.8   135.1 1705.88
   138.5 1705.23   142.2 1703.93   148.6    1700     153 1698.91   157.2 1698.52
   167.6  1699.9   177.4 1699.28     187 1700.77  192.161700.694   230.6 1701.29
   234.9 1702.52   241.3 1707.23   246.5 1709.76   249.3  1710.2   264.5 1710.54
   275.2 1713.49  298.02 1714.42   360.9 1718.47  395.861722.098   430.8 1727.24
   443.1 1728.48     476 1734.01   484.2  1735.9  493.71 1736.91   494.8 1736.98
#Mann= 7 ,-1 , 0
       0     .05       0   148.6    .045       0   167.6     .05       0
  192.16     .06       0  298.02     .05       0  395.86     .06       0
  493.71      .1       0
Bank Sta=148.6,167.6
XS Rating Curve= 0 ,0
Exp/Cntr(USF)=0,0
Exp/Cntr=0.3,0.1

Type RM Length L Ch R = 1 ,2158    ,54.9,56.9,58.5
XS GIS Cut Line= 4
2448679.78416422623381.4918885072448640.77614622623297.696886878
2448556.98114459623130.1068836192448463.07295311622965.406363175
#Sta/Elev= 30
       0 1723.15    21.4  1718.6    40.4 1712.69    51.4  1710.4    73.5 1707.28
      90 1705.64   117.9 1703.76   134.8 1703.35  152.981701.315   173.6 1699.23
   179.5 1698.16   186.4 1697.03   197.4 1696.15   202.9 1696.73  209.261698.162
   218.3 1699.17   231.1 1701.48   237.3 1703.59   245.1 1707.16   252.1 1709.03
     261 1709.75   277.9 1709.77   297.3 1712.73  309.261713.186   324.9    1714
  359.281718.535   397.4 1727.02   421.6 1731.72  463.661738.394   469.4 1739.39
#Mann= 7 ,-1 , 0
       0     .05       0  152.98     .06       0   179.5    .045       0
  209.26     .06       0  309.26     .05       0  359.28     .06       0
  463.66      .1       0
Bank Sta=179.5,209.26
XS Rating Curve= 0 ,0
Exp/Cntr(USF)=0,0
Exp/Cntr=0.5,0.3

Type RM Length L Ch R = 1 ,2101    ,26.4,26.9,32
XS GIS Cut Line= 4
2448694.23157829623351.1523189512448650.88933607623254.354644655
2448629.21821496623096.8778312492448556.98114459622932.177310805
#Sta/Elev= 30
       0 1719.34    30.1 1711.33    52.9 1707.09      66 1705.45    83.6  1704.1
  122.461702.052   166.1 1700.18   170.1 1699.72  177.671696.676   186.3  1694.3
   190.3 1694.44  195.27 1696.68   198.4  1698.7   202.4 1700.31   214.5 1702.53
   224.5 1703.19   250.9 1703.61   271.6 1703.09   275.9 1703.85   280.5 1705.35
     289 1706.49   297.8 1709.04   315.2  1710.5     324 1712.01   354.5  1720.3
   363.3 1723.82   376.4 1730.46   380.7 1732.21  420.261745.564   444.9 1754.23
#Mann= 5 ,-1 , 0
       0     .05       0  122.46     .06       0  177.67    .045       0
  195.27     .06       0  420.26      .1       0
#XS Ineff= 2 , 0
           169.2 1700.07  202.45         1700.24
Permanent Ineff=
       F       F
Bank Sta=177.67,195.27
XS Rating Curve= 0 ,0
Exp/Cntr(USF)=0,0
Exp/Cntr=0.5,0.3

Type RM Length L Ch R = 1 ,2074    ,31.4,31.1,30.8
XS GIS Cut Line= 5
2448717.34744081623348.2628361372448672.87401085623260.321742489
2448663.56277025623132.3863315492448662.44726733623056.425071841
2448627.77347355622924.953603768
#Sta/Elev= 30
       01728.791  23.7961723.126  41.6581716.764  62.4961707.531  67.8111705.895
  94.4011703.106 132.0661700.603 168.1621696.226 180.1931695.411 188.2151693.938
 192.2251694.011 200.2461695.073 208.2671695.395 220.2991697.308 232.3171698.306
 276.3221699.491 288.3231699.205 292.3231700.405 296.3241701.008 304.3771701.417
 312.651 1703.84 320.9241710.128 333.3341715.124 354.018 1726.86 382.3651744.329
 391.2491750.134 399.5231756.134  403.661758.779  416.071765.528 438.7571775.512
#Mann= 6 ,-1 , 0
       0     .05       0 132.066      .1       0 180.193    .045       0
 200.246      .1       0 276.322     .06       0 399.523      .1       0
#XS Ineff= 2 , 0
                          228.29         1699.28
Permanent Ineff=
       F       F
Bank Sta=180.193,200.246
XS Rating Curve= 0 ,0
Exp/Cntr(USF)=0,0
Exp/Cntr=0.5,0.3

Type RM Length L Ch R = 1 ,2043    ,45.8,37.4,28.1
XS GIS Cut Line= 4
 2448740.2654726 623337.617886482448702.25962909623266.443306824
 2448689.1303377623077.1051046322448651.12449419622953.413359404
#Sta/Elev= 30
       0 1735.53     7.6 1732.68    43.9 1721.24    68.2 1711.11      80 1705.13
    83.6 1704.17   104.3 1701.81   112.3    1700   116.3 1699.62   143.6 1698.29
   156.4 1696.34   172.5 1696.33   180.5 1695.03   188.5 1692.94   199.8 1693.93
   216.6 1695.53   252.7 1694.42   260.7 1696.15   268.7 1697.18     287 1696.92
   293.7  1697.9   297.9 1699.72   305.8 1705.42   310.5 1708.12   318.8 1713.87
   331.4 1721.36   360.3 1740.16   373.4 1747.91   385.8 1756.35   399.9 1764.65
#Mann= 3 , 0 , 0
       0      .1       0   180.5    .045       0   199.8      .1       0
#XS Ineff= 2 , 0
                          278.54         1698.86
Permanent Ineff=
       F       F
Bank Sta=180.5,199.8
XS Rating Curve= 0 ,0
Exp/Cntr(USF)=0,0
Exp/Cntr=0.5,0.3

Type RM Length L Ch R = 1 ,2005    ,101.5,96.2,94.4
XS GIS Cut Line= 4
2448805.47666666623283.2494728042448766.46864866623216.791368063
2448687.00787125623065.0935202862448661.00252592622946.624724879
#Sta/Elev= 30
       0 1752.38    16.9 1747.16    37.5 1739.81   115.3 1706.64   131.6 1699.02
   146.4 1694.85  163.011693.155     174 1691.12   176.1 1691.08     179 1691.25
  185.441693.155   188.5 1693.89   202.7 1694.12   210.2 1694.11   219.2 1693.35
   226.4 1695.76   232.7 1696.68   241.8 1697.21   253.7  1696.8   258.8 1697.35
   262.9 1699.08   266.9 1702.32  278.351709.688   287.4 1715.21   307.5 1729.37
   324.3 1741.83   332.5 1746.96   345.3 1756.24   352.9 1761.05   369.6 1770.49
#Mann= 4 ,-1 , 0
       0      .1       0  163.01    .045       0  185.44     .06       0
  278.35      .1       0
#XS Ineff= 2 , 0
                           214.3         1697.71
Permanent Ineff=
       F       F
Bank Sta=163.01,185.44
XS Rating Curve= 0 ,0
Exp/Cntr(USF)=0,0
Exp/Cntr=0.3,0.1

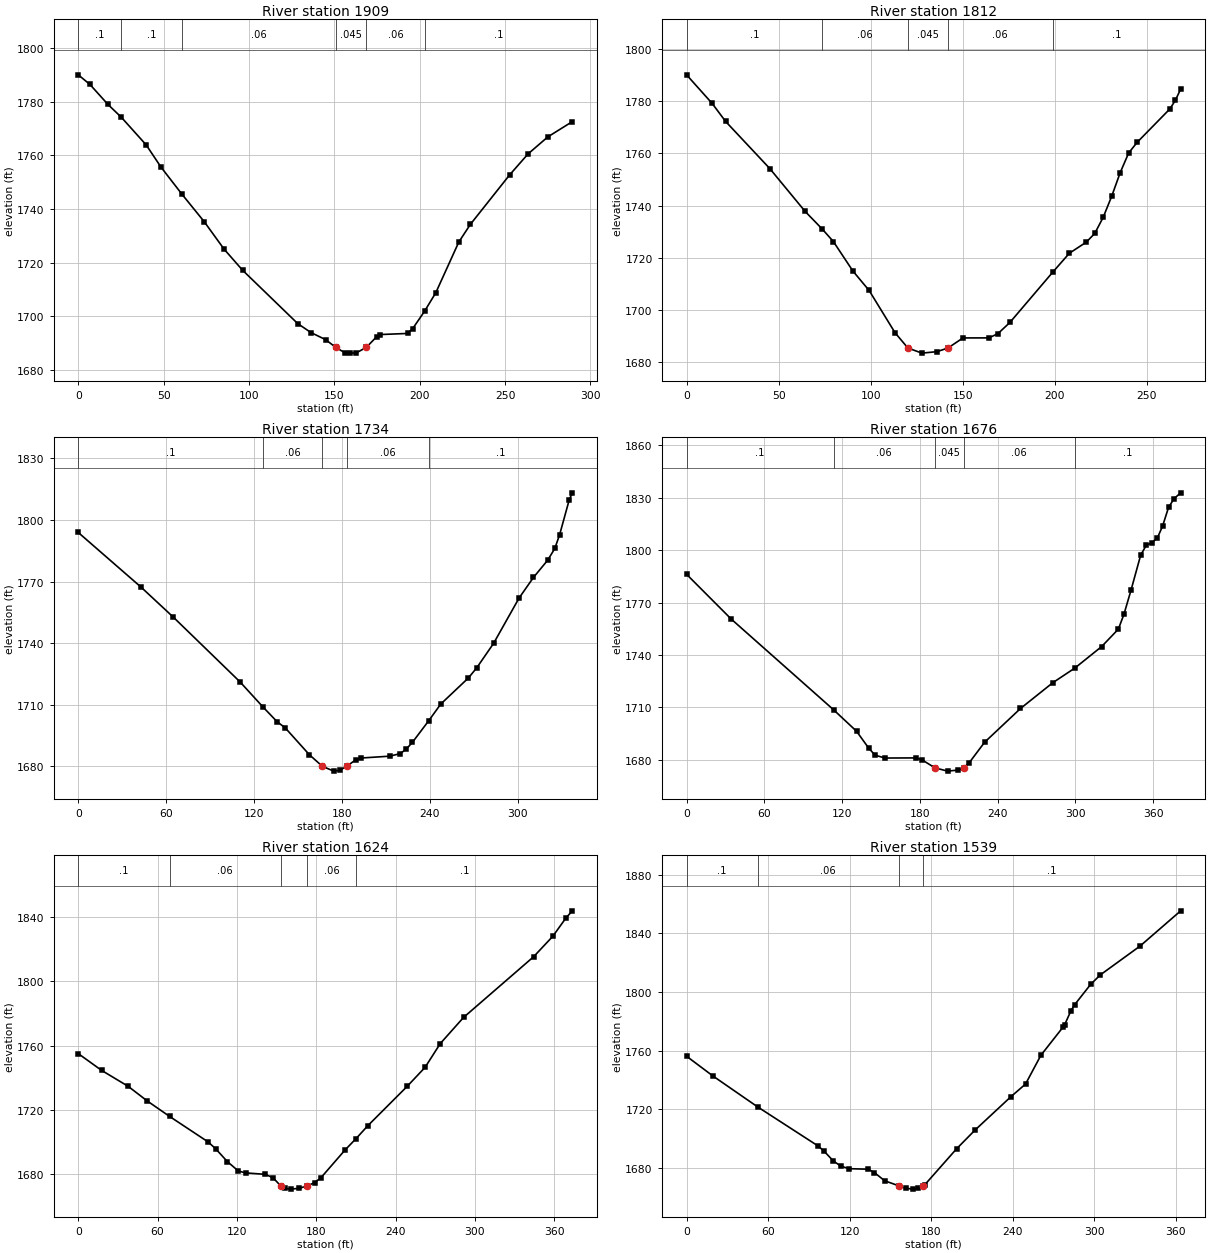
Type RM Length L Ch R = 1 ,1909    ,98.2,97.4,95.8
XS GIS Cut Line= 4
2448867.60054718623154.6674875452448808.36614948623096.877831249
  2448714.457958622992.8564499162448669.67097437622943.735242064
#Sta/Elev= 30
       0 1790.07     6.8 1786.51    17.4 1779.02   25.291774.197    39.8 1763.91
    48.5  1755.6   60.86 1745.43    73.8 1735.26    85.4 1725.04    96.2  1717.2
   128.5 1697.28   136.3 1693.91   144.9 1691.26  150.841688.371   156.1  1686.4
   158.9 1686.24   162.8 1686.33   168.7 1688.37   174.7 1692.32     177 1693.18
   192.9 1693.58   195.8 1695.31  202.791701.835   209.4 1708.77   222.9 1727.71
   229.7 1734.32   252.6  1752.7   263.4 1760.54     275 1766.91   289.4 1772.63
#Mann= 6 ,-1 , 0
       0      .1       0   25.29      .1       0   60.86     .06       0
  150.84    .045       0   168.7     .06       0  202.79      .1       0
Bank Sta=150.84,168.7
XS Rating Curve= 0 ,0
Exp/Cntr(USF)=0,0
Exp/Cntr=0.3,0.1

Type RM Length L Ch R = 1 ,1812    ,81.5,77.7,73.6
XS GIS Cut Line= 4
2448908.05330659623065.0935202862448854.59787451622998.635415545
2448763.57916585622917.7298967312448710.12373377622887.390327175
#Sta/Elev= 30
       0 1790.16    13.9 1779.18    21.2 1772.28    45.2  1754.2    64.4 1737.75
   73.791730.905    79.8 1726.13    90.4 1714.83    99.2 1707.38   113.3 1691.14
  120.281685.294   127.9 1683.34     136  1683.9  142.011685.291   150.2 1689.17
   164.3 1689.19   169.2 1690.83   175.7 1695.12  198.841714.307     208 1721.68
   217.2 1725.94   221.8 1729.29   226.4  1735.5     231 1743.55   235.6 1752.59
   240.2 1760.13   244.8 1764.23   262.6 1777.06   265.6 1780.38   268.5 1784.73
#Mann= 5 ,-1 , 0
       0      .1       0   73.79     .06       0  120.28    .045       0
  142.01     .06       0  198.84      .1       0
Bank Sta=120.28,142.01
XS Rating Curve= 0 ,0
Exp/Cntr(USF)=0,0
Exp/Cntr=0.5,0.3

Type RM Length L Ch R = 1 ,1734    ,60,58.2,56.4
XS GIS Cut Line= 4
2449014.96417073623002.9696397672448908.05330659622919.174638138
2448818.47933933 622896.058775622448728.90537207622833.934895101
#Sta/Elev= 30
       0 1793.89    42.9 1767.27      65 1752.61   110.4  1721.2  126.031709.015
   135.8 1701.75   141.3 1698.79   157.8  1685.7  166.621680.093   174.4 1677.71
   178.5 1678.12  183.411680.093   189.7 1683.34   192.9 1684.08   212.7 1684.99
   219.8 1686.23   223.9 1688.39   228.1 1691.66  239.38 1702.31   247.5 1710.34
   266.4 1723.07   272.1 1728.01   283.6 1739.91     301 1761.97   310.8 1771.98
   320.5 1780.37   325.4 1786.11   328.7 1792.84   335.3 1809.92   337.4 1813.19
#Mann= 5 ,-1 , 0
       0      .1       0  126.03     .06       0  166.62    .045       0
  183.41     .06       0  239.38      .1       0
#XS Ineff= 2 , 0
             151 1682.75     198         1682.75
Permanent Ineff=
       F       F
Bank Sta=166.62,183.41
XS Rating Curve= 0 ,0
Exp/Cntr(USF)=0,0
Exp/Cntr=0.5,0.3

Type RM Length L Ch R = 1 ,1676    ,47.7,52.2,56.8
XS GIS Cut Line= 4
2449049.63796451622976.9642944342448954.28503162622867.163947472
2448802.58718385622844.0480849532448726.01588925622813.708515398
#Sta/Elev= 30
       0 1786.19    34.5 1760.54  113.491708.607   131.1 1696.41   140.5 1686.72
   145.4  1682.7   153.1 1681.05   176.9 1681.13   181.4 1680.13  191.571675.444
   201.4 1673.56   209.7 1674.18  213.791675.443   217.8 1678.12   229.9 1690.07
   257.6  1709.4   282.5 1724.14  299.551732.544   320.2 1744.84   333.1 1754.81
   337.4  1763.3   342.8 1776.94   350.3 1797.11   354.6 1802.77   358.9 1804.24
   363.2 1807.03   367.2 1813.74   371.8 1824.44   376.1 1829.52   381.2 1832.82
#Mann= 5 ,-1 , 0
       0      .1       0  113.49     .06       0  191.57    .045       0
  213.79     .06       0  299.55      .1       0
Bank Sta=191.57,213.79
XS Rating Curve= 0 ,0
Exp/Cntr(USF)=0,0
Exp/Cntr=0.5,0.3

Type RM Length L Ch R = 1 ,1624    ,79.5,84.6,88.3
XS GIS Cut Line= 4
2449072.75382703622926.398345175 2448988.9588254622862.829723249
2448858.93209874622774.7004973982448766.46864866622712.576616879
#Sta/Elev= 30
       0 1755.02    17.6  1744.6    37.7 1734.67    52.1 1725.58   69.041715.914
    98.2 1700.03   103.9 1695.79   112.7 1687.83   121.1  1681.9   126.5 1680.75
   141.3 1679.84   147.1 1677.85  153.111672.694   156.2 1671.03     161 1670.63
   167.2 1671.18   173.31672.693   178.7 1674.68   183.5 1677.69   201.8 1695.03
  210.151702.136     219 1710.13   248.7 1734.58   262.3 1746.46   273.8 1761.28
   291.4 1777.54   344.4 1815.35   358.9 1828.07   368.9 1839.56   373.7 1843.92
#Mann= 5 ,-1 , 0
       0      .1       0   69.04     .06       0  153.11    .045       0
   173.3     .06       0  210.15      .1       0
Bank Sta=153.11,173.3
XS Rating Curve= 0 ,0
Exp/Cntr(USF)=0,0
Exp/Cntr=0.3,0.1

Type RM Length L Ch R = 1 ,1539    ,128.7,133.2,136
XS GIS Cut Line= 4
2449088.64598251 622923.508862362449048.19322311622849.827050583
 2448968.7324457 622712.576616882448902.27434096622611.444718361
#Sta/Elev= 30
       0 1756.21    19.5 1742.68    52.41721.638    96.7 1695.12   101.3 1691.43
   107.8 1685.05   113.6 1681.24   119.8 1679.58   133.7 1679.22   138.3  1676.9
   145.8 1671.34  156.161667.936   161.4 1666.29   166.3 1665.65   170.6 1666.25
  174.241667.938   175.3 1668.58   198.7  1693.1   212.2 1705.79   238.6 1728.54
   249.5 1737.27   260.8 1756.88   277.1 1776.06   278.2 1777.55     283 1787.35
   285.7 1791.41   297.4 1805.16   304.5 1811.62   333.7 1831.23   363.7  1855.3
#Mann= 4 ,-1 , 0
       0      .1       0    52.4     .06       0  156.16    .045       0
  174.24      .1       0
Bank Sta=156.16,174.24
XS Rating Curve= 0 ,0
Exp/Cntr(USF)=0,0
Exp/Cntr=0.3,0.1

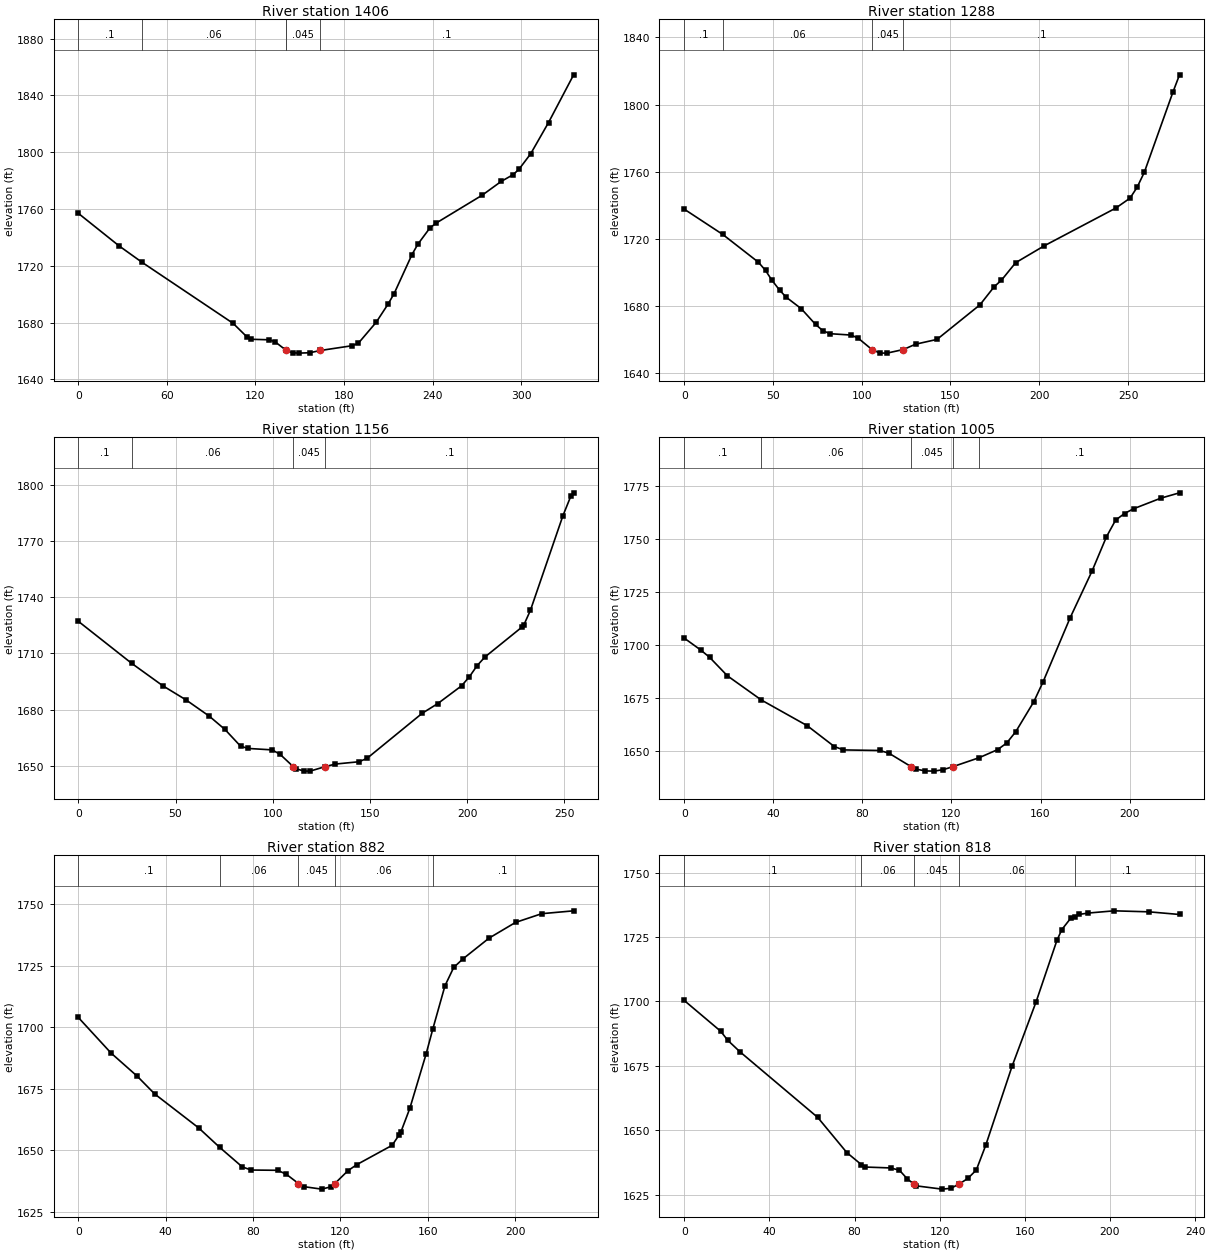
Type RM Length L Ch R = 1 ,1406    ,118.1,118.5,119
XS GIS Cut Line= 4
2449159.43831147622906.1719654712449142.10141459622810.819032583
2449120.43029348622647.5632535462449114.65132785622573.881441769
#Sta/Elev= 30
       0  1756.9    27.7  1733.9   43.011722.516   104.9 1679.39   114.1 1669.99
     117 1668.21   129.1 1667.84   133.2 1666.48  140.571660.607  140.981660.303
   145.3 1658.69   149.3 1658.45   156.8 1658.72  163.941660.306   185.6 1663.69
   189.7 1665.43   201.8 1680.22   209.8 1692.96   213.9 1700.32     226 1727.83
     230 1735.17   238.1 1746.51   242.1 1749.84   273.6 1769.68   286.4 1779.33
   294.4 1784.05   298.4 1787.79   306.4 1798.79   318.5 1820.81   335.5 1854.42
#Mann= 5 ,-1 , 0
       0      .1       0   43.01     .06       0  140.57      .1       0
  140.98    .045       0  163.94      .1       0
Bank Sta=140.98,163.94
XS Rating Curve= 0 ,0
Exp/Cntr(USF)=0,0
Exp/Cntr=0.3,0.1

Type RM Length L Ch R = 1 ,1288    ,132.2,131.8,131.2
XS GIS Cut Line= 4
 2449262.0149514622868.6086888792449259.12546859 622818.04273962
 2449241.7885717622670.6791160652449233.12012325622591.218338658
#Sta/Elev= 30
       0  1737.7   21.721722.617    41.8 1706.08    45.8 1701.22    49.3 1695.51
    53.8 1689.38    57.4  1685.3    65.9 1678.44      74 1669.03      78 1665.41
      82 1663.53    94.1  1662.7    98.1 1660.77  105.741654.095   110.2 1651.99
   114.2 1651.95  123.471654.097   130.3 1657.26   142.4 1660.12   166.6 1680.72
   174.6 1691.49   178.7 1695.38   186.7  1705.8   202.8 1715.85   243.1 1738.32
   251.1 1744.21   255.1 1750.66   259.2  1759.7   275.3  1807.4     279 1817.68
#Mann= 4 ,-1 , 0
       0      .1       0   21.72     .06       0  105.74    .045       0
  123.47      .1       0
Bank Sta=105.74,123.47
XS Rating Curve= 0 ,0
Exp/Cntr(USF)=0,0
Exp/Cntr=0.3,0.1

Type RM Length L Ch R = 1 ,1156    ,151,150.7,150.3
XS GIS Cut Line= 4
2449390.59693666622854.1612748052449390.59693666 622784.81368725
2449370.37055696622670.6791160652449366.03633273 622601.33152851
#Sta/Elev= 30
       0 1727.18   27.41 1704.77    43.4 1692.82    55.4 1685.24    67.3  1676.6
    75.4 1669.49    83.5 1660.49    87.5 1659.34    99.7 1658.58   103.8 1656.18
  110.561649.615   111.9 1648.55     116 1647.29   119.2 1647.25  126.811649.615
   132.2 1651.02   144.4 1652.26   148.5 1654.09   176.9 1678.16   184.8 1683.24
   197.1 1692.77   201.1 1697.58   205.1 1703.55   209.1 1708.12   228.2 1724.14
   229.1  1725.2   232.5 1733.06   249.2 1783.49   253.2 1793.75   254.7  1795.7
#Mann= 4 ,-1 , 0
       0      .1       0   27.41     .06       0  110.56    .045       0
  126.81      .1       0
Bank Sta=110.56,126.81
XS Rating Curve= 0 ,0
Exp/Cntr(USF)=0,0
Exp/Cntr=0.3,0.1

Type RM Length L Ch R = 1 ,1005    ,122.6,123.2,124.3
XS GIS Cut Line= 4
2449540.85004303622838.2691193242449537.96056021622770.366273176
2449517.73418051622664.9001504352449509.06573207622618.668425398
#Sta/Elev= 30
       0 1703.17     7.4 1697.57    11.4 1694.12    19.4  1685.4   34.661673.995
    55.2 1661.93    67.4 1652.09    71.5 1650.49    87.8 1650.22    91.9 1648.96
  101.871642.613   104.1 1641.44   108.2  1640.6   112.2  1640.5   116.3 1641.19
  120.691642.612  132.441646.825   140.7 1650.61   144.8 1653.73   148.9 1659.12
     157 1673.24   161.1 1682.47   173.3 1712.76   183.1 1734.69   189.6 1750.91
   193.7 1758.74   197.7 1761.87   201.8 1764.11     214 1769.09   222.4 1771.61
#Mann= 5 ,-1 , 0
       0      .1       0   34.66     .06       0  101.87    .045       0
  120.69     .06       0  132.44      .1       0
Bank Sta=101.87,120.69
XS Rating Curve= 0 ,0
Exp/Cntr(USF)=0,0
Exp/Cntr=0.3,0.1

Type RM Length L Ch R = 1 ,882     ,61.9,63.9,66
XS GIS Cut Line= 4
2449662.20832125622849.8270505832449657.87409703622783.368945842
2449644.87142436622682.2370473242449637.64771733622624.447391028
#Sta/Elev= 30
       0 1703.91      15 1689.46      27 1680.05      35 1672.85    55.1  1659.1
   64.741651.188    75.1 1643.25    79.2 1641.99    91.3 1641.88    95.3 1640.24
  100.811636.524   103.4 1635.23   111.4 1634.24   115.5 1635.13  117.491636.519
   123.5 1641.75   127.6 1644.22   143.7 1652.02   146.8 1656.11   147.7 1657.41
   151.8 1667.01   159.2 1688.91  162.321699.199   167.9 1716.78   171.9 1724.21
     176 1727.59   188.1 1736.12   200.2 1742.48   212.2 1746.03 226.803 1747.19
#Mann= 5 ,-1 , 0
       0      .1       0   64.74     .06       0  100.81    .045       0
  117.49     .06       0  162.32      .1       0
Bank Sta=100.81,117.49
XS Rating Curve= 0 ,0
Exp/Cntr(USF)=0,0
Exp/Cntr=0.3,0.1

Type RM Length L Ch R = 1 ,818     ,89.6,96.5,109
XS GIS Cut Line= 4
2449673.76625251622849.8270505832449712.77427051 622779.03472162
2449721.44271896622685.126530139 2449709.8847877 622628.78161525
#Sta/Elev= 30
       0 1700.37    17.1 1688.45    20.5 1684.87    26.2 1680.44    62.7 1654.99
    76.4 1641.32    83.21636.678      85 1635.72      97 1635.37   101.1 1634.48
   104.8 1631.12  107.771629.198   109.1 1628.41   121.1 1627.15   125.2 1627.45
  129.291629.194   133.2 1631.29   137.2 1634.55   141.6 1644.09     154 1674.82
   165.3 1699.86   175.1 1723.74   177.4  1727.9   181.5 1732.22  183.511732.937
   185.6 1733.76   189.7 1734.28   201.9 1735.15   218.3 1734.76232.6536 1733.73
#Mann= 5 ,-1 , 0
       0      .1       0    83.2     .06       0  107.77    .045       0
  129.29     .06       0  183.51      .1       0
Bank Sta=107.77,129.29
XS Rating Curve= 0 ,0
Exp/Cntr(USF)=0,0
Exp/Cntr=0.5,0.3

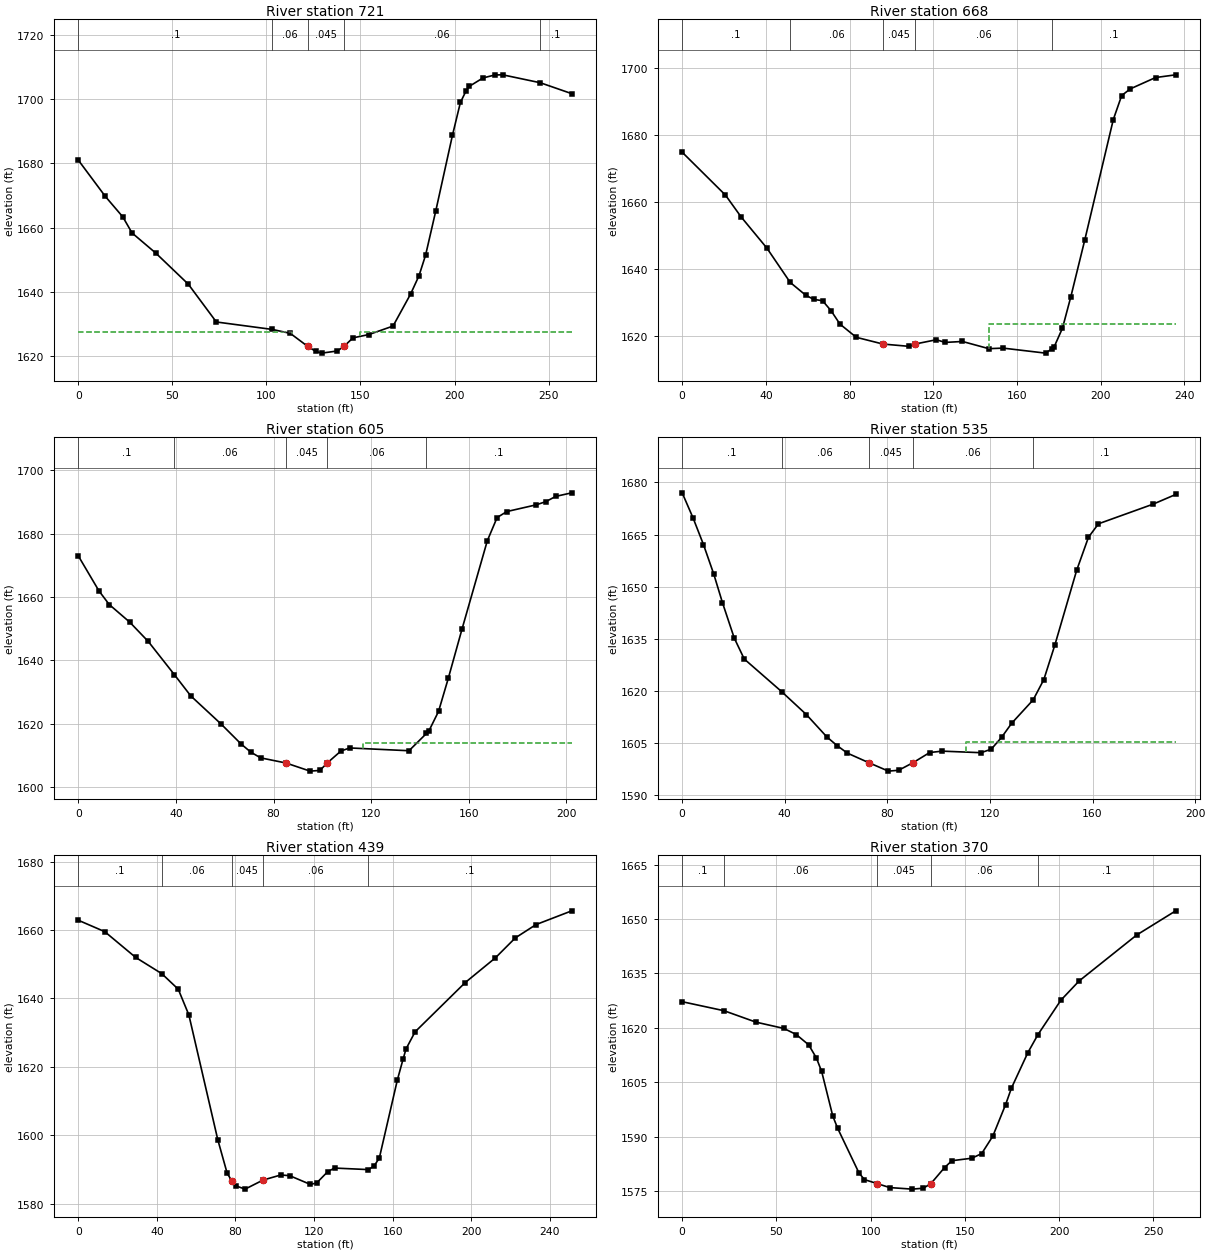
Type RM Length L Ch R = 1 ,721     ,49.3,53.3,47.1
XS GIS Cut Line= 4
2449714.21901192622833.9348951012449759.00599555622773.255755991
 2449847.1352214622747.2504106572449889.03272221 622662.01066762
#Sta/Elev= 30
       0 1681.05    14.4 1669.73    23.7 1663.35    28.6 1658.36    41.3 1652.05
    58.5 1642.42    73.4 1630.66  103.221628.335   112.7 1627.12     1221623.047
   126.2 1621.52   129.4 1620.97   137.7 1621.64  141.211623.046     146 1625.72
   154.4 1626.74   167.3 1629.39   176.6 1639.31   181.1 1645.05   184.6 1651.45
     190 1665.18   198.9  1688.8   203.1 1698.95   206.1 1702.54   207.8 1703.96
   215.1 1706.58   221.5 1707.52   225.6 1707.55  245.571705.086262.2838 1701.69
#Mann= 5 ,-1 , 0
       0      .1       0  103.22     .06       0     122    .045       0
  141.21     .06       0  245.57      .1       0
#XS Ineff= 2 , 0
          113.84 1627.49  149.88         1627.45
Permanent Ineff=
       F       F
Bank Sta=122,141.21
XS Rating Curve= 0 ,0
Exp/Cntr(USF)=0,0
Exp/Cntr=0.5,0.3

Type RM Length L Ch R = 1 ,668     ,75.4,62.9,62
XS GIS Cut Line= 4
2449763.02127866 622841.271450892449810.79517846622800.322393914
2449893.54639777622774.7292333042449907.19608342622689.418697939
#Sta/Elev= 30
       0 1674.87    20.7 1662.05    28.2 1655.52    40.5 1646.22   51.641635.976
      59 1632.18    62.9  1630.9    67.1 1630.51    71.2  1627.5    75.4 1623.54
    83.2 1619.58      96 1617.56   108.4 1616.88  111.45 1617.58   121.5 1618.85
   125.7 1618.05     134 1618.33   146.6 1616.18   153.4 1616.35   173.7 1614.85
  176.641616.099   177.7 1616.55   181.8 1622.32   185.8 1631.71   192.4 1648.51
   206.1 1684.64   210.1  1691.8   214.2 1693.79   226.3 1697.18235.9361 1697.99
#Mann= 5 ,-1 , 0
       0      .1       0   51.64     .06       0      96    .045       0
  111.45     .06       0  176.64      .1       0
#XS Ineff= 2 , 0
                          146.67         1623.66
Permanent Ineff=
       F       F
Bank Sta=96,111.45
XS Rating Curve= 0 ,0
Exp/Cntr(USF)=0,0
Exp/Cntr=0.5,0.3

Type RM Length L Ch R = 1 ,605     ,71.8,70,68.2
XS GIS Cut Line= 4
2449895.25260847622883.0736132192449911.46161019622828.474870585
2449925.11129585622740.6050191582449925.11129585622684.300065817
#Sta/Elev= 30
       0 1673.01     8.5 1661.92    12.7 1657.63    21.1 1652.07    28.7 1645.97
   39.371635.534    46.1 1628.82    58.6 1619.89    66.7 1613.66    70.7 1611.08
    74.7 1609.28   85.091607.657      95 1605.09      99 1605.31  102.01 1607.66
   107.6 1611.42   111.2  1612.4   135.5 1611.52  142.64 1616.96   143.6 1617.68
   147.6 1623.91   151.6 1634.35   157.2 1649.82   167.6 1677.77   171.6 1685.06
   175.6 1686.95   187.6 1689.06   191.6 1690.08   195.6 1691.73202.1826 1692.85
#Mann= 5 ,-1 , 0
       0      .1       0   39.37     .06       0   85.09    .045       0
  102.01     .06       0  142.64      .1       0
#XS Ineff= 2 , 0
                          116.73         1614.02
Permanent Ineff=
       F       F
Bank Sta=85.09,102.01
XS Rating Curve= 0 ,0
Exp/Cntr(USF)=0,0
Exp/Cntr=0.3,0.1

Type RM Length L Ch R = 1 ,535     ,100.8,96.5,93.9
XS GIS Cut Line= 4
2449992.50661879622871.1301382682449989.09419738622826.768659878
2449983.97556525622738.8988084512449963.50103677 622682.59385511
#Sta/Elev= 30
       0 1677.02     4.3 1669.69     8.3 1662.14    12.3 1653.68    15.7 1645.44
    20.3 1635.25    24.2 1629.22   38.821619.808    48.4 1613.25    56.4 1606.81
    60.4 1604.31    64.4 1602.15   72.651599.437    80.4 1596.97    84.4 1597.22
   90.111599.438    96.5 1602.32   101.4 1602.72   116.5 1602.27   120.5 1603.28
   124.5 1606.66   128.5 1610.77  136.861617.484     141 1623.31   145.3 1633.25
   153.8 1654.73   158.4 1664.24   162.3 1668.11   183.6 1673.76192.4234 1676.55
#Mann= 5 ,-1 , 0
       0      .1       0   38.82     .06       0   72.65    .045       0
   90.11     .06       0  136.86      .1       0
#XS Ineff= 2 , 0
                          110.66         1605.28
Permanent Ineff=
       F       F
Bank Sta=72.65,90.11
XS Rating Curve= 0 ,0
Exp/Cntr(USF)=0,0
Exp/Cntr=0.3,0.1

Type RM Length L Ch R = 1 ,439     ,70.7,68.6,69.2
XS GIS Cut Line= 4
2450131.56279144622848.9493990732450088.90752375622788.378918963
2450041.13362395622700.5090675362449992.50661879 622640.79169278
#Sta/Elev= 30
       0 1662.86    13.5 1659.51    29.2 1651.99   42.541647.223    50.9 1642.68
    56.3 1635.16      71 1598.72    75.8 1588.85   78.15 1586.67    80.3 1585.19
    84.9 1584.25      94 1586.89   103.1 1588.39   107.6 1588.18   118.1 1585.63
   121.3 1586.04   126.9 1589.33   130.4 1590.41  147.651589.958   150.5 1590.99
   153.2 1593.34   162.4 1616.22   165.3 1622.28   166.8 1625.25   171.4 1630.23
   196.9 1644.63   212.3 1651.88   222.4 1657.69   232.9 1661.57251.1114  1665.6
#Mann= 5 ,-1 , 0
       0      .1       0   42.54     .06       0   78.15    .045       0
      94     .06       0  147.65      .1       0
Bank Sta=78.15,94
XS Rating Curve= 0 ,0
Exp/Cntr(USF)=0,0
Exp/Cntr=0.3,0.1

Type RM Length L Ch R = 1 ,370     ,64.6,63.4,62.6
XS GIS Cut Line= 4
2450200.66432508622819.9438170482450164.83390023622767.051285122
 2450088.0544184622677.4752229882450021.51220081622633.113744597
#Sta/Elev= 30
       0  1627.2    22.21624.714    39.1 1621.57      54 1619.82    60.5 1618.15
    67.1 1615.31    71.2 1611.69      74 1607.95    79.9 1595.66    82.5 1592.26
    93.8 1579.96    96.7 1578.13  103.471577.023   110.1 1575.93     122  1575.5
   127.9 1575.75  131.961577.024   139.2 1581.45   143.1 1583.34   153.7 1584.03
   158.9 1585.31   164.8 1590.12   171.6 1598.84   174.7  1603.4   183.4 1613.16
  188.731618.116   200.9 1627.61   210.6 1632.93   241.1 1645.59261.8386 1652.27
#Mann= 5 ,-1 , 0
       0      .1       0    22.2     .06       0  103.47    .045       0
  131.96     .06       0  188.73      .1       0
Bank Sta=103.47,131.96
XS Rating Curve= 0 ,0
Exp/Cntr(USF)=0,0
Exp/Cntr=0.5,0.3