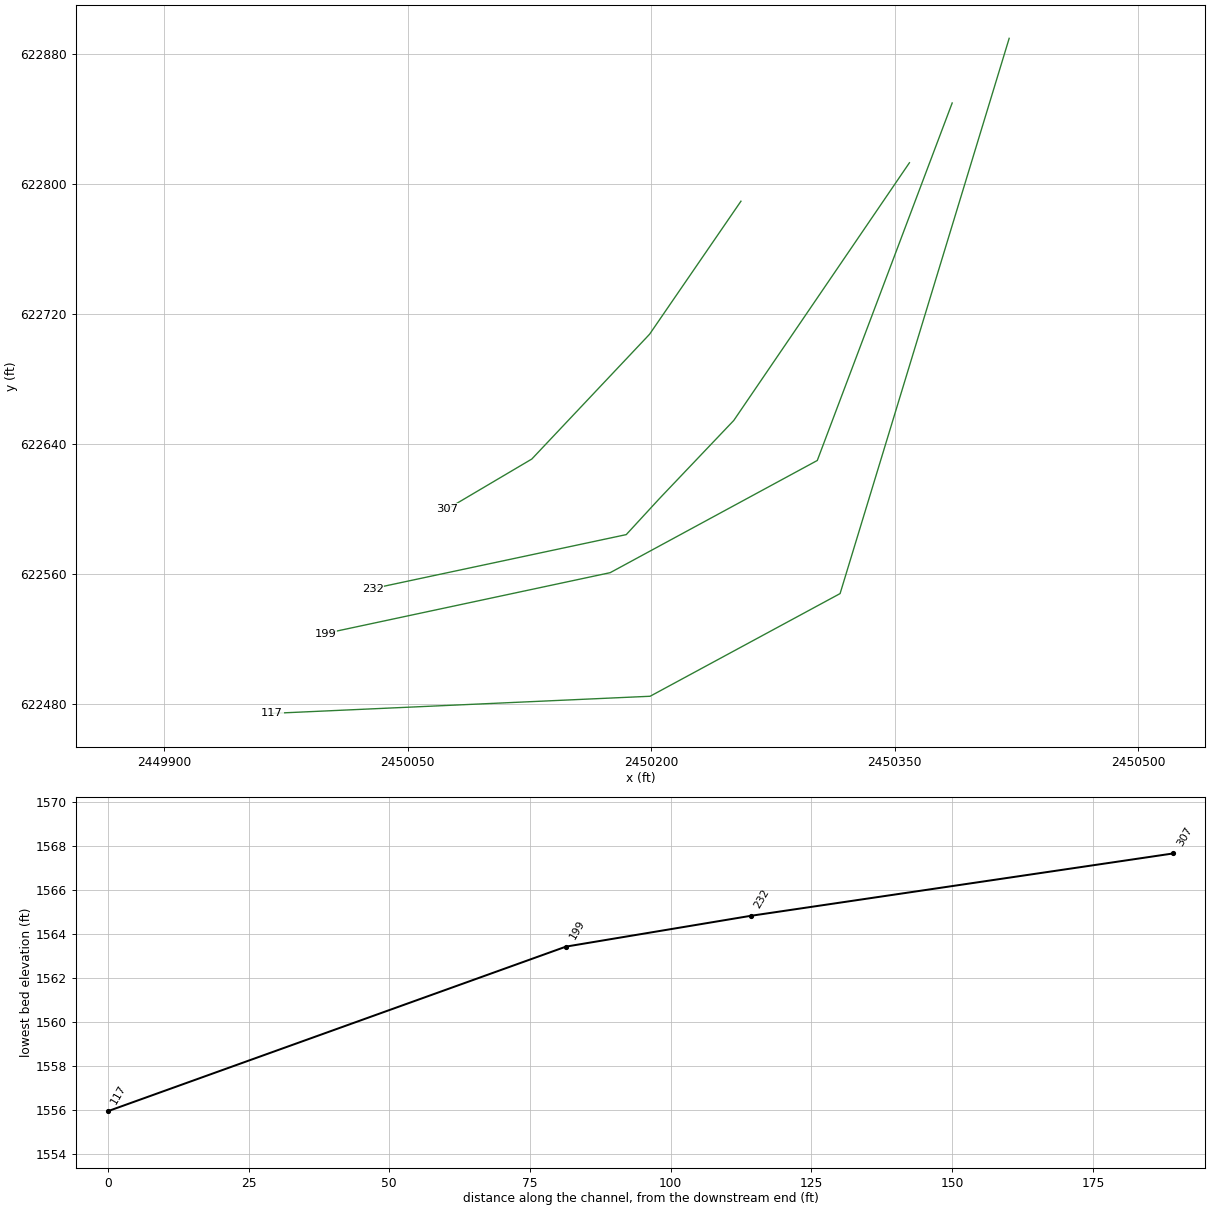
HEC-RAS study PETERSRN.prj: PETERSRN

--- PETERSRN.g01 (geometry) --- (continued)

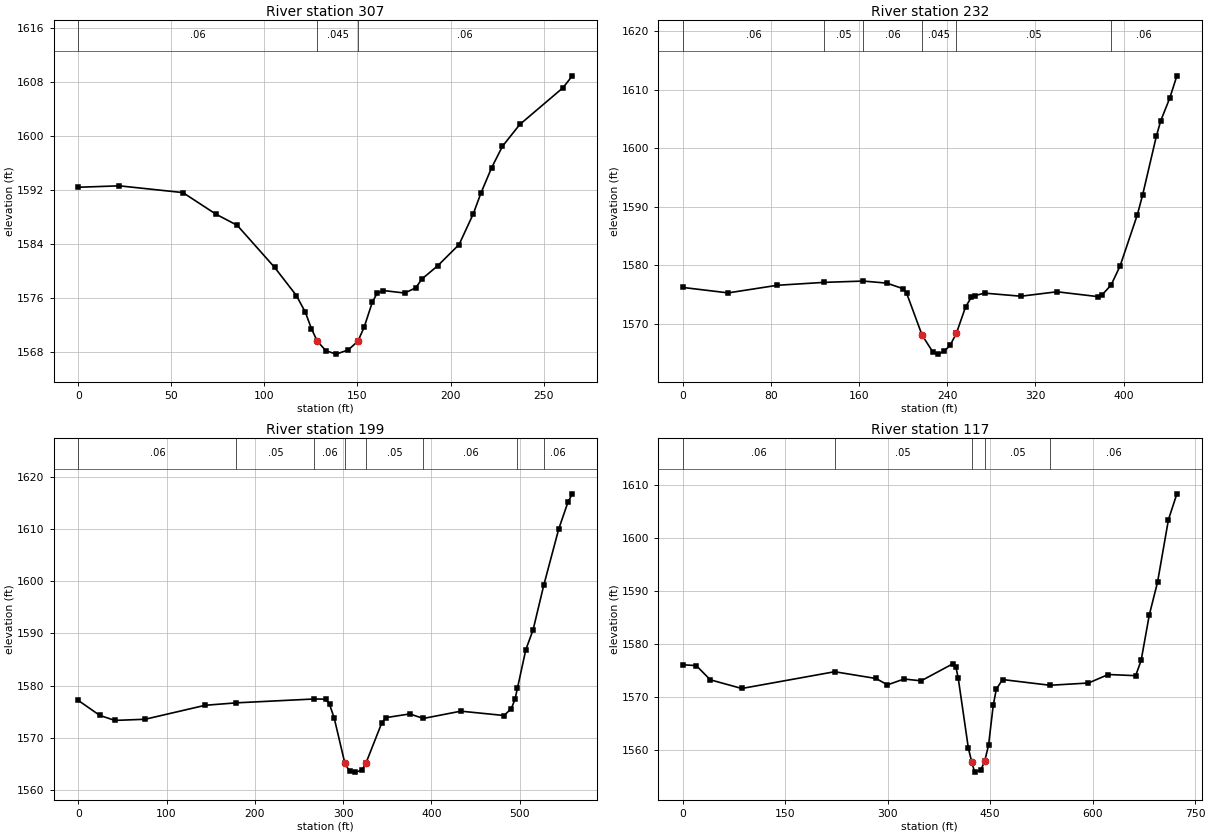
Type RM Length L Ch R = 1 ,307     ,74.6,75.1,75.1
XS GIS Cut Line= 4
2450255.26306772622789.2320243172450198.95811438622707.333910366
2450126.44415932622630.5544285362450074.40473274622599.842635805
#Sta/Elev= 30
       0 1592.43    22.1 1592.64    56.2 1591.64      74 1588.43    85.4 1586.78
   105.5 1580.53   117.2 1576.35     122 1573.88   125.3 1571.41   128.41569.596
     133 1568.17   138.5 1567.66   145.1 1568.29  150.261569.594   153.6 1571.67
     158 1575.39   160.5 1576.67   163.8  1577.1   175.4 1576.73   181.3  1577.5
   184.7 1578.83   193.2  1580.8   204.6 1583.93   212.2 1588.48   216.4 1591.62
   222.1 1595.35   227.9 1598.52   237.2 1601.75   260.4  1607.2265.4214 1608.97
#Mann= 3 ,-1 , 0
       0     .06       0   128.4    .045       0  150.26     .06       0
#XS Ineff= 2 , 0
             103 1576.66     175         1576.66
Permanent Ineff=
       F       F
Bank Sta=128.4,150.26
XS Rating Curve= 0 ,0
Exp/Cntr(USF)=0,0
Exp/Cntr=0.5,0.3

Type RM Length L Ch R = 1 ,232     ,37.4,32.8,30.9
XS GIS Cut Line= 5
2450359.04142236622812.896778716 2450250.8564518622654.314800515
2450205.07738842622606.2429058782450184.60152745622584.037261619
2450028.36283659 622550.78851215
#Sta/Elev= 30
       0 1576.22    41.2 1575.29    85.7 1576.59   128.3 1577.09   163.8 1577.31
   185.1 1576.96   200.1 1575.99     203 1575.27   217.1 1568.07   226.9 1565.17
   231.3 1564.82   236.9 1565.27   242.6 1566.34   248.2 1568.37   256.7 1572.96
   261.8 1574.52   265.2 1574.83   273.8 1575.25   306.8 1574.72   339.5 1575.48
   376.3 1574.66   380.4 1574.94   388.6 1576.63   396.8 1579.91   412.5 1588.69
   417.2 1592.03   429.7  1602.1   433.6 1604.69   441.8 1608.58   448.3  1612.4
#Mann= 6 ,-1 , 0
       0     .06       0   128.3     .05       0   163.8     .06       0
   217.1    .045       0   248.2     .05       0   388.6     .06       0
Bank Sta=217.1,248.2
XS Rating Curve= 0 ,0
Exp/Cntr(USF)=0,0
Exp/Cntr=0.3,0.1

Type RM Length L Ch R = 1 ,199     ,81.4,81.4,83.1
XS GIS Cut Line= 4
2450385.36924071622849.6714374862450302.28216237622629.666215967
2450174.72594351622560.6220241072449999.18986251622523.174326827
#Sta/Elev= 30
       0 1577.15    24.4 1574.28    41.5 1573.32    75.7 1573.54   143.9 1576.22
  179.161576.685  267.391577.425   280.1 1577.39   284.7 1576.38     290 1573.74
  302.081565.073   307.4 1563.58   313.6 1563.42   321.1 1563.76  325.761565.076
   343.8 1572.83   348.4 1573.85   375.6 1574.56  390.911573.696   433.4 1575.09
   482.4 1574.26   490.6 1575.59   494.7 1577.34  497.47 1579.45     507 1586.86
   515.2 1590.63  527.411599.247   544.3 1609.97   554.7 1615.09559.7016  1616.7
#Mann= 8 ,-1 , 0
       0     .06       0  179.16     .05       0  267.39     .06       0
  302.08    .045       0  325.76     .05       0  390.91     .06       0
  497.47      .1       0  527.41     .06       0
Bank Sta=302.08,325.76
XS Rating Curve= 0 ,0
Exp/Cntr(USF)=0,0
Exp/Cntr=0.3,0.1

Type RM Length L Ch R = 1 ,117     ,,,
XS GIS Cut Line= 4
2450420.47645691622889.4596158462450316.32504885622547.749378167
2450199.30099485622484.5563890072449966.42312739622474.024224147
#Sta/Elev= 30
       0 1576.13    19.7 1575.98    40.3  1573.3    86.3 1571.67  222.281574.823
   282.9 1573.55   299.6 1572.35   323.9 1573.45   348.9 1573.11   395.4 1576.32
   399.9 1575.67   403.3 1573.57   418.1 1560.39  422.891557.929   427.2 1555.93
   436.3 1556.34  441.851557.932   447.6 1560.98   454.5 1568.52     459 1571.54
   468.1 1573.35  537.631572.274   593.9  1572.7   622.9  1574.3     663 1574.08
     671 1576.95     683 1585.54     695 1591.66     711 1603.45723.3423  1608.3
#Mann= 5 ,-1 , 0
       0     .06       0  222.28     .05       0  422.89    .045       0
  441.85     .05       0  537.63     .06       0
Bank Sta=422.89,441.85
XS Rating Curve= 0 ,0
Exp/Cntr(USF)=0,0
Exp/Cntr=0.3,0.1
LCMann Table=0

Chan Stop Cuts=-1
Use User Specified Reach Order=0
Composite Channel Slope=5